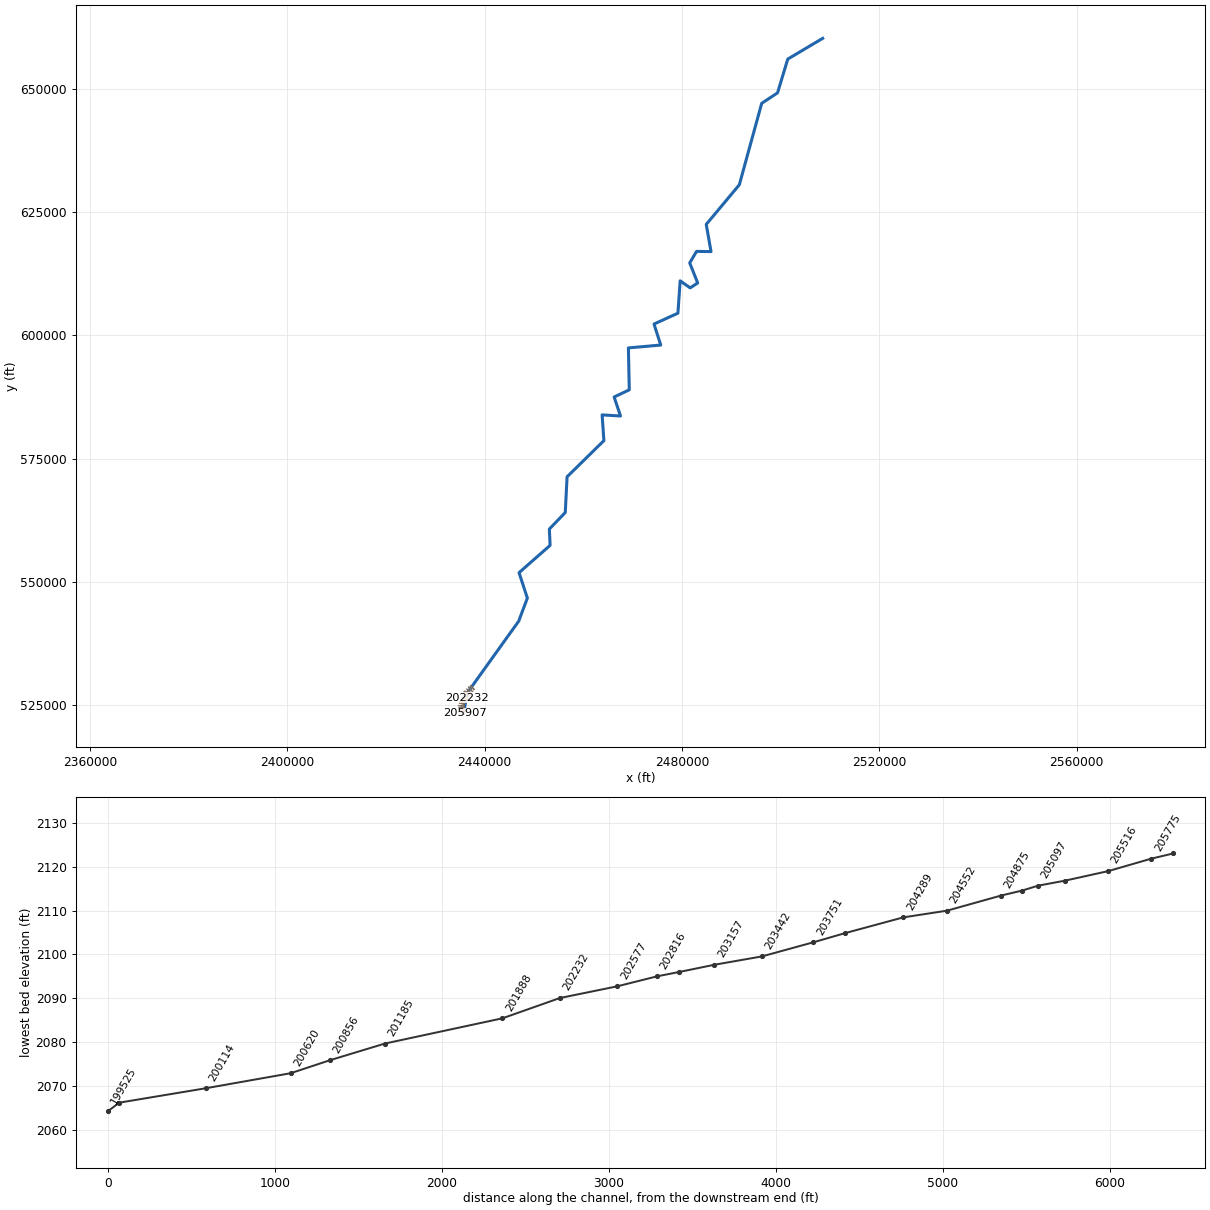
--- SFSBPOTOMC.prj (project) ---

Proj Title=SFSBPOTOMC
Current Plan=p01
Default Exp/Contr=0,0
English Units
Geom File=g01
Flow File=f01
Plan File=p01
Background Map Layer=QC
BEGIN DESCRIPTION:
Stream Name: South Fork South Branch Potomac River
Flood Zone: Zone A
Pendleton County, WV
WVDHSEM Flood Warning & Analysis Mapping
HEC-RAS Version: 5.0.7
Hydrology Method:
Regression with Gage Weighting and Regulation
Model Notes:
Model extends beyond county boundary in the downstream portion and normal depth used as boundary condition.
END DESCRIPTION:
DSS Export Rating Curves= 0
DSS Export Rating Curve Sorted= 0
DSS Export Volume Flow Curves= 0
DXF OffsetX= 0
DXF OffsetY= 0
DXF ScaleX= 0
DXF ScaleY= 0

--- SFSBPOTOMC.p01 (plan) ---

Plan Title=Floodplain
Program Version=5.07
Short Identifier=Floodplain
Geom File=g01
Flow File=f01
Subcritical Flow
K Sum by GR= 0
Std Step Tol= 0.01
Critical Tol= 0.01
Num of Std Step Trials= 20
Max Error Tol= 0.3
Flow Tol Ratio= 0.001
Split Flow NTrial= 30
Split Flow Tol= 0.02
Split Flow Ratio= 0.02
Log Output Level= 0
Friction Slope Method= 1
Unsteady Friction Slope Method= 2
Unsteady Bridges Friction Slope Method= 1
Parabolic Critical Depth
Global Vel Dist= 0 , 0 , 0
Global Log Level= 0
CheckData=True
Encroach Param=-1 ,0,0, 0
Mapping Interval=1HOUR
Computation Time Step Use Courant=        0
Computation Time Step Use Time Series=    0
Computation Time Step Count To Double=0
Computation Time Step Max Doubling=0
Computation Time Step Max Halving=0
Computation Time Step Residence Courant=0
Run HTab= 0
Run UNet= 0
Run Sediment= 0
Run PostProcess= 0
Run WQNet= 0
Run RASMapper= 0
UNET Theta= 0
UNET Theta Warmup= 0
UNET ZTol= 0
UNET ZSATol= 0
UNET MxIter= 0
UNET Max Iter WO Improvement= 0
UNET MaxInSteps= 0
UNET DtIC= 0
UNET DtMin= 0
UNET MaxCRTS= 0
UNET WFStab= 0
UNET SFStab= 0
UNET WFX= 1
UNET SFX= 1
UNET 1D Methodology=Finite Difference
UNET DSS MLevel= 1
UNET Pardiso=0
UNET DZMax Abort= 0
UNET Use Existing IB Tables= 0
UNET Froude Reduction=False
UNET Froude Limit= 0
UNET Froude Power= 0
UNET D1 Cores= 0
UNET D2 Coriolis=0
UNET D2 Cores= 0
UNET D2 Theta= 1
UNET D2 Theta Warmup= 1
UNET D2 Z Tol= 0.01
UNET D2 Volume Tol= 0.01
UNET D2 Max Iterations= 20
UNET D2 Equation= 0
UNET D2 RampUpFraction=0.1
UNET D2 TimeSlices= 1
UNET D2 BCVolumeCheck=0
UNET D1D2 MaxIter= 0
UNET D1D2 ZTol=0.01
UNET D1D2 QTol=0.1
UNET D1D2 MinQTol=1
Write IC File= 0
Write IC File at Fixed DateTime=0
Write IC File at Sim End=0
Echo Input=False
Echo Parameters=False
Echo Output=False
Write Detailed= 0
HDF Write Warmup=0
HDF Write Time Slices=0
HDF Flush=0
HDF Face Node Velocities=0
HDF Compression= 1
HDF Chunk Size= 1
HDF Spatial Parts= 1
HDF Use Max Rows=0
HDF Fixed Rows= 1
Calibration Method= 0
Calibration Iterations= 20
Calibration Max Change=0.05
Calibration Tolerance=0.2
Calibration Maximum=1.5
Calibration Minimum=0.5
Calibration Optimization Method= 1
WQ AD Non Conservative
WQ ULTIMATE=-1
WQ Max Comp Step=1HOUR
WQ Output Interval=15MIN
WQ Output Selected Increments= 0
WQ Output face flow=0
WQ Output face velocity=0
WQ Output face area=0
WQ Output face dispersion=0
WQ Output cell volume=0
WQ Output cell surface area=0
WQ Output cell continuity=0
WQ Output cumulative cell continuity=0
WQ Output face conc=0
WQ Output face dconc_dx=0
WQ Output face courant=0
WQ Output face peclet=0
WQ Output face adv mass=0
WQ Output face disp mass=0
WQ Output cell mass=0
WQ Output cell source sink temp=0
WQ Output nsm pathways=0
WQ Output nsm derived pathways=0
WQ Output MaxMinRange=-1
WQ Daily Max Min Mean=-1
WQ Daily Range=0
WQ Daily Time=0
WQ Create Restart=0
WQ Fixed Restart=0
WQ System Summary=0
WQ Write To DSS=0
WQ Use Fixed Temperature=0
Sorting and Armoring Iterations= 10
XS Update Threshold= 0.02
Bed Roughness Predictor= 0
Hydraulics Update Threshold= 0.02
Energy Slope Method= 1
Volume Change Method= 1
Sediment Retention Method= 0
XS Weighting Method= 0
Number of US Weighted Cross Sections= 1
Number of DS Weighted Cross Sections= 1
Upstream XS Weight=0
Main XS Weight=1
Downstream XS Weight=0
Number of DS XS's Weighted with US Boundary= 1
Upstream Boundary Weight= 1
Weight of XSs Associated with US Boundary= 0
Number of US XS's Weighted with DS Boundary= 1
Downstream Boundary Weight= 0.5
Weight of XSs Associated with DS Boundary= 0.5
Percentile Method= 0
Sediment Output Level= 3
Mass or Volume Output= 0
Output Increment Type= 1
Profile and TS Output Increment= 1
XS Output Flag= 0
XS Output Increment= 10
Write Gradation File= 0
Read Gradation Hotstart= 0
Write HDF5 File= 1
Write Binary Output= 1
Write DSS Sediment File= 0
SV Curve= 0
Specific Gage Flag= 0

--- SFSBPOTOMC.f01 (steady flow) ---

Flow Title=Flows
Program Version=5.07
Number of Profiles= 6
Profile Names=P100yr,P10yr,P25yr,P50yr,P500yr,P101yr
River Rch & RM=SFSBPOTOMC,Main            ,205907
    1930     886    1263    1587    2865    2477
River Rch & RM=SFSBPOTOMC,Main            ,202816
    2150     986    1406    1767    3195    2760
River Rch & RM=SFSBPOTOMC,Main            ,199525
    2469    1130    1613    2028    3675    3169
River Rch & RM=SFSBPOTOMC,Main            ,194465
    6851    1756    3078    4206   17074    8794
River Rch & RM=SFSBPOTOMC,Main            ,190555
    7482    1923    3366    4623   18600    9603
River Rch & RM=SFSBPOTOMC,Main            ,188989
    8204    2114    3695    5102   20340   10530
River Rch & RM=SFSBPOTOMC,Main            ,181626
   12761    3330    5784    8191   31243   16379
River Rch & RM=SFSBPOTOMC,Main            ,181192
   13940    3647    6326    9004   34042   17893
River Rch & RM=SFSBPOTOMC,Main            ,170385
   16256    4272    7394   10616   39525   20865
River Rch & RM=SFSBPOTOMC,Main            ,164599
   18275    4818    8326   12035   44286   23457
River Rch & RM=SFSBPOTOMC,Main            ,134676
   24147    6417   11045   16222   58051   30994
River Rch & RM=SFSBPOTOMC,Main            ,117420
   27211    7256   12467   18436   65193   34926
River Rch & RM=SFSBPOTOMC,Main            ,102251
   31916    8550   14657   21872   76119   40965
River Rch & RM=SFSBPOTOMC,Main            ,74293
   33260   10478   17007   23950   70112   42690
River Rch & RM=SFSBPOTOMC,Main            ,44708
   35902   12101   19228   26512   70988   46081
River Rch & RM=SFSBPOTOMC,Main            ,0
   37621   13157   20675   28179   71558   48287
Boundary for River Rch & Prof#=SFSBPOTOMC,Main            , 1
Up Type= 0
Dn Type= 1
Dn Known WS=1214.82
Boundary for River Rch & Prof#=SFSBPOTOMC,Main            , 2
Up Type= 0
Dn Type= 1
Dn Known WS=1211.01
Boundary for River Rch & Prof#=SFSBPOTOMC,Main            , 3
Up Type= 0
Dn Type= 1
Dn Known WS=1212.33
Boundary for River Rch & Prof#=SFSBPOTOMC,Main            , 4
Up Type= 0
Dn Type= 1
Dn Known WS=1213.46
Boundary for River Rch & Prof#=SFSBPOTOMC,Main            , 5
Up Type= 0
Dn Type= 1
Dn Known WS=1219.2
Boundary for River Rch & Prof#=SFSBPOTOMC,Main            , 6
Up Type= 0
Dn Type= 1
Dn Known WS=1216.27
DSS Import GetInterval= 0
DSS Import GetPeak= 0
DSS Import FillOption= 0

--- SFSBPOTOMC.g01 (geometry) ---

Geom Title=Geometry
Program Version=5.07

River Reach=SFSBPOTOMC      ,Main
Reach XY= 30
     2435717.092      523358.256     2436437.408       527477.58
     2446877.035      542043.488     2448639.539      546729.443
     2446950.696      551878.967     2453246.479      557415.932
     2453095.992      560720.628      2456321.35      564071.068
     2456687.268      571312.778     2464150.529      578642.849
     2463793.896      583862.667      2467519.71      583634.479
     2466228.563      587485.138     2469298.738      588946.006
     2469118.623      597437.803     2475675.202      598019.027
     2474308.109      602274.791      2479159.79      604479.593
     2479608.177       611033.72     2481645.036      609606.835
      2483163.22      610608.908     2481547.291      614671.942
     2482936.461        617004.1      2485869.27       616961.46
     2484895.189      622474.552      2491602.27      630501.866
     2496140.377        647023.4     2499350.119      649134.967
     2501425.104      655986.4012508507.98722932660191.104992652

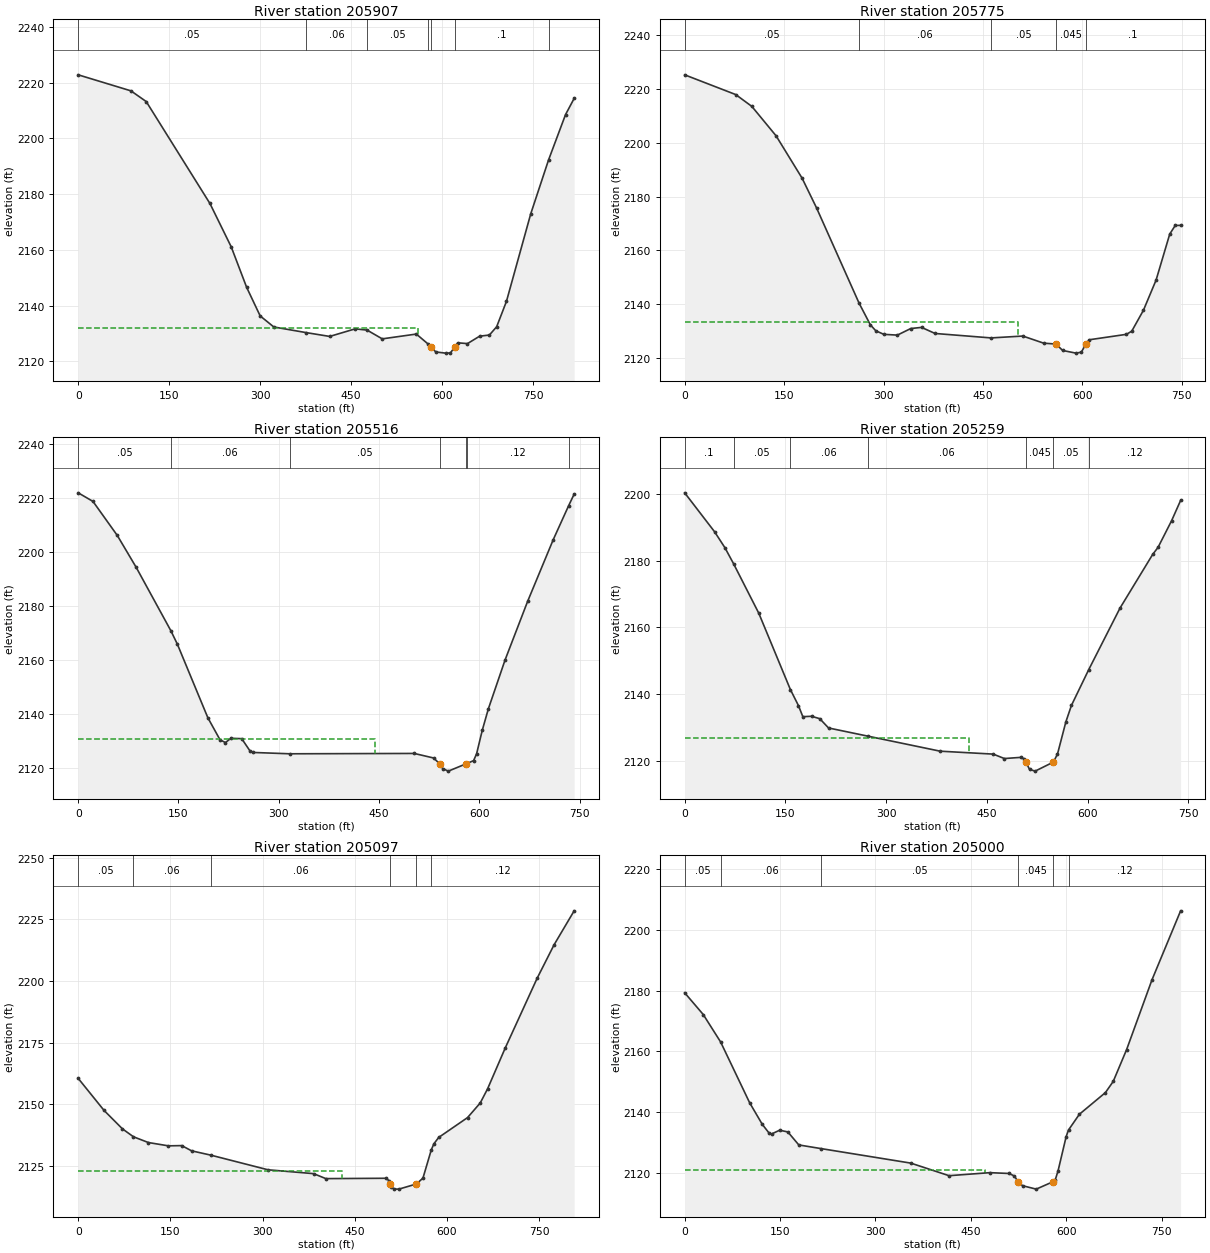
Type RM Length L Ch R = 1 ,205907  ,132.5,132.4,133.2
XS GIS Cut Line= 4
2435144.03247031 523561.37426793 2435587.3366412523419.137635558
2435878.92173756523395.4315301632435938.18700105523393.060919623
#Sta/Elev= 30
       0 2222.84    86.9 2217.09   112.1 2213.25   217.1 2176.68   252.2 2161.12
   277.6 2146.61   299.9 2136.35   322.4 2132.38  375.822130.357   414.5 2128.99
   456.5 2131.71  476.182131.252   501.1 2128.12   557.3 2129.84  575.812126.429
  581.042125.242   589.4 2123.42   605.4    2123   613.5 2123.06  620.59 2125.24
   625.5  2126.7   641.6 2126.42   661.6 2129.08   677.7 2129.49   689.7 2132.47
   705.8 2141.56   745.9 2173.01  775.152192.267   803.2 2208.57   817.4 2214.38
#Mann= 7 ,-1 , 0
       0     .05       0  375.82     .06       0  476.18     .05       0
  575.81      .1       0  581.04    .045       0  620.59      .1       0
  775.15     .12       0
#XS Ineff= 2 , 0
          559.67 2131.96
Permanent Ineff=
       F       F
Bank Sta=581.04,620.59
XS Rating Curve= 0 ,0
Exp/Cntr(USF)=0,0
Exp/Cntr=0.3,0.1

Type RM Length L Ch R = 1 ,205775  ,249.4,258.2,267.2
XS GIS Cut Line= 4
2435162.99735462523620.6395314192435547.03626203523551.891825772
2435845.73319001523532.9269414562435902.62784296523518.703278219
#Sta/Elev= 30
       0 2225.31      77 2217.97   101.3 2213.57   137.9 2202.62   177.1 2186.88
   198.9 2175.83   263.12140.381   280.1 2132.34   288.3 2130.12   300.4  2128.8
   320.8 2128.51   341.1 2130.96   357.3 2131.38   377.7 2129.12   462.12127.468
   510.1 2128.16   541.6 2125.51   560.1 2125.19   570.2 2122.79   590.3 2121.81
   598.3 2122.16  605.18 2125.15   610.3 2126.78   666.4  2128.8   674.4 2129.98
     692 2137.75   711.1 2148.98   731.7  2166.1     740 2169.29   748.1 2169.33
#Mann= 5 ,-1 , 0
       0     .05       0   263.1     .06       0   462.1     .05       0
   560.1    .045       0  605.18      .1       0
#XS Ineff= 2 , 0
          502.96 2133.27
Permanent Ineff=
       F       F
Bank Sta=560.1,605.18
XS Rating Curve= 0 ,0
Exp/Cntr(USF)=0,0
Exp/Cntr=0.3,0.1

Type RM Length L Ch R = 1 ,205516  ,257.8,257.2,255.2
XS GIS Cut Line= 4
2435200.92712325523656.1986895122435423.76451397523689.387237066
2435800.69158976523817.4002062012435912.11028512523857.700585373
#Sta/Elev= 30
       0  2221.9    22.1 2218.72    58.5 2206.12    86.8 2194.31  138.55 2170.92
   148.3 2165.94     194 2138.67   212.1 2130.58   220.2 2129.53   228.4 2131.11
   244.6 2130.98   257.2 2126.35   262.2 2125.87  316.492125.383   502.7 2125.51
   531.6 2123.83  540.972121.639   545.3 2119.91   553.7 2118.97  579.93 2121.64
  581.532121.787   591.5 2122.86     596 2125.41   604.4 2134.04   613.5 2141.96
   638.6 2160.11   672.3 2181.76   710.6 2204.57  733.532217.075   741.9 2221.43
#Mann= 7 ,-1 , 0
       0     .05       0  138.55     .06       0  316.49     .05       0
  540.97    .045       0  579.93     .05       0  581.53     .12       0
  733.53      .1       0
#XS Ineff= 2 , 0
          443.37 2130.97
Permanent Ineff=
       F       F
Bank Sta=540.97,579.93
XS Rating Curve= 0 ,0
Exp/Cntr(USF)=0,0
Exp/Cntr=0.3,0.1

Type RM Length L Ch R = 1 ,205259  ,160.7,162.3,164.4
XS GIS Cut Line= 4
2435151.14430192 523819.77081674 2435293.3809343523928.818901559
2435696.38472602524044.9788179962435836.25074785524052.090649615
#Sta/Elev= 30
       0 2200.38    44.6 2188.67      60 2183.88   72.982179.027   110.4 2164.22
  157.452141.308   169.5 2136.47     176 2133.16     189 2133.28   201.2 2132.56
   214.3 2129.77  272.552127.327   380.5  2122.8   459.6 2121.92   476.2 2120.59
   501.2 2120.95   505.3 2120.54  508.142119.532   513.7 2117.33     522 2116.81
  549.242119.535   555.3 2121.94   567.8 2131.62   576.1 2136.56  601.832147.287
   648.4 2165.76   697.1 2181.89   705.1 2184.01   725.2 2191.98   738.7  2198.1
#Mann= 7 ,-1 , 0
       0      .1       0   72.98     .05       0  157.45     .06       0
  272.55     .06       0  508.14    .045       0  549.24     .05       0
  601.83     .12       0
#XS Ineff= 2 , 0
           424.1 2126.82
Permanent Ineff=
       F       F
Bank Sta=508.14,549.24
XS Rating Curve= 0 ,0
Exp/Cntr(USF)=0,0
Exp/Cntr=0.3,0.1

Type RM Length L Ch R = 1 ,205097  ,95.1,97.3,98.5
XS GIS Cut Line= 4
2435141.66185977523902.7421856242435357.38741886524097.132249866
2435686.90228386524220.4039979222435850.47441109524239.368882238
#Sta/Elev= 30
       0 2160.54      42 2147.57    71.9  2140.1   89.952136.865   114.2 2134.54
   146.8  2133.2   168.4  2133.3   184.5 2131.18  215.712129.434   308.9 2123.49
   382.9 2121.94   402.9 2119.92   501.1 2120.06   505.4 2119.12  507.61 2117.76
   509.6 2116.48   513.9 2115.69   521.7 2115.66  550.382117.758   560.9 2120.13
  574.552131.647   578.7 2134.03   586.5 2136.61   633.5 2144.66   654.1 2150.58
     666 2156.28   694.8 2172.88   746.7 2201.13   774.2 2214.67   806.9 2228.45
#Mann= 6 ,-1 , 0
       0     .05       0   89.95     .06       0  215.71     .06       0
  507.61    .045       0  550.38     .05       0  574.55     .12       0
#XS Ineff= 2 , 0
          429.36 2122.99
Permanent Ineff=
       F       F
Bank Sta=507.61,550.38
XS Rating Curve= 0 ,0
Exp/Cntr(USF)=0,0
Exp/Cntr=0.3,0.1

Type RM Length L Ch R = 1 ,205000  ,127.9,124.7,115.6
XS GIS Cut Line= 4
2435051.57865926 524075.796755012435378.72291372524203.809724145
2435618.15457821524296.2635351872435786.46792652 524331.82269328
#Sta/Elev= 30
       0 2179.27    29.2  2172.1   56.492163.066   102.2    2143   122.1 2135.87
   132.3 2133.13   136.6 2132.71   149.4 2133.96   162.3 2133.38   179.5  2129.1
  213.972127.912   355.6 2123.11   415.8 2118.96     480 2119.96     510 2119.69
   518.5 2118.87  524.152117.031   531.4 2115.66   552.9 2114.53  579.982117.032
   582.9 2117.65   587.2 2120.52     600 2131.86  603.672134.025   620.8 2139.22
   661.7 2146.35     674 2150.04   695.1 2160.56   734.9 2183.51     780 2206.29
#Mann= 6 ,-1 , 0
       0     .05       0   56.49     .06       0  213.97     .05       0
  524.15    .045       0  579.98     .05       0  603.67     .12       0
#XS Ineff= 2 , 0
          471.91 2120.95
Permanent Ineff=
       F       F
Bank Sta=524.15,579.98
XS Rating Curve= 0 ,0
Exp/Cntr(USF)=0,0
Exp/Cntr=0.3,0.1

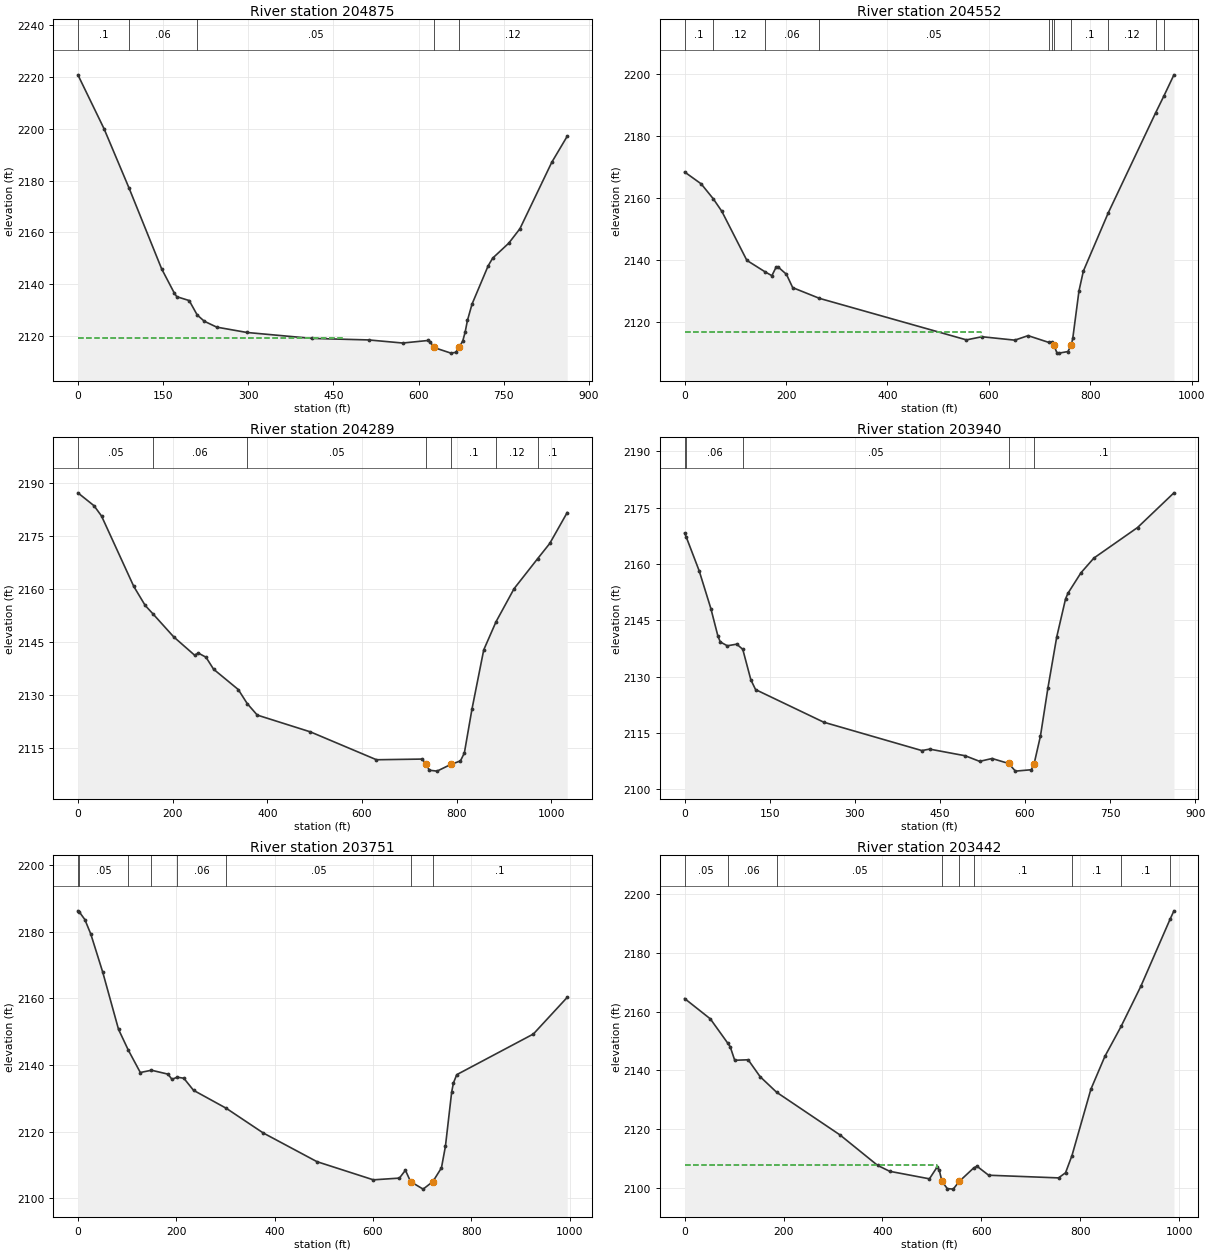
Type RM Length L Ch R = 1 ,204875  ,321.5,323.3,329.3
XS GIS Cut Line= 4
2434944.90118498524201.4391136062435236.48628135 524336.56391436
2435625.26640983524410.0528410852435769.87365274524412.423451625
#Sta/Elev= 30
       0  2220.8    46.1 2199.98   90.22 2177.04   147.5 2145.93   169.6 2136.67
   174.2 2135.18     196  2133.7  210.122128.136   222.6 2125.72   244.5 2123.44
   297.7 2121.38   411.6  2119.1     512  2118.5     572 2117.31   616.8 2118.29
   620.8  2117.7  626.682115.602   656.9 2113.41   665.6 2113.72  671.262115.601
   677.8 2118.13   681.9 2121.47     686 2126.03   694.1 2132.34   722.5  2147.1
   730.5 2150.08   758.7 2155.82   778.4 2161.41   834.5 2187.05   861.7  2197.1
#Mann= 5 ,-1 , 0
       0      .1       0   90.22     .06       0  210.12     .05       0
  626.68    .045       0  671.26     .12       0
#XS Ineff= 2 , 0
          469.08 2119.09
Permanent Ineff=
       F       F
Bank Sta=626.68,671.26
XS Rating Curve= 0 ,0
Exp/Cntr(USF)=0,0
Exp/Cntr=0.3,0.1

Type RM Length L Ch R = 1 ,204552  ,268.1,262.2,258.6
XS GIS Cut Line= 4
2434819.25882639524495.3948205092435272.04543944524602.072294788
 2435599.1896939 524744.308927162435736.68510519524784.609306332
#Sta/Elev= 30
       0 2168.31    32.7 2164.48   56.492159.682    73.4 2155.64   122.8 2139.84
  158.522136.169   172.1 2134.91   180.3 2137.59   184.4 2137.71   200.8 2135.37
   213.2 2131.06     2662127.609     556 2114.23   586.4 2115.25   651.3 2114.15
   677.5  2115.6  718.572113.407  724.92 2113.53  728.042112.592   734.2 2110.15
   738.6 2109.97     756 2110.48  762.782112.589   765.8 2114.93   777.9 2130.03
   786.5 2136.38  835.622155.141  929.282187.434   945.7  2192.9   965.2  2199.6
#Mann= 11 ,-1 , 0
       0      .1       0   56.49     .12       0  158.52     .06       0
     266     .05       0  718.57     .12       0  724.92      .1       0
  728.04    .045       0  762.78      .1       0  835.62     .12       0
  929.28      .1       0   945.7     .12       0
#XS Ineff= 2 , 0
          585.56 2116.86
Permanent Ineff=
       F       F
Bank Sta=728.04,762.78
XS Rating Curve= 0 ,0
Exp/Cntr(USF)=0,0
Exp/Cntr=0.3,0.1

Type RM Length L Ch R = 1 ,204289  ,362.8,349.2,343.1
XS GIS Cut Line= 4
2434677.02219402524929.2165492442435170.10918624524891.286780612
2435513.84771447524974.2581494952435698.75533656524986.111202193
#Sta/Elev= 30
       0 2187.19    34.1 2183.54    49.9 2180.64   118.1 2160.69   142.1 2155.33
  158.252152.985   202.3 2146.44   246.4 2141.26   254.5 2141.83   270.5 2140.68
   286.6 2137.28   338.7 2131.53  357.592127.558   378.8  2124.3   491.2 2119.54
   630.6 2111.66   726.8 2111.85  735.932110.345   742.1  2108.7   758.5 2108.44
  787.772110.346   807.9 2111.33   816.2 2113.58   832.2 2125.94   857.1 2142.75
  883.132150.723   921.2 2160.07  970.992168.567   996.5 2172.86  1033.4 2181.61
#Mann= 7 ,-1 , 0
       0     .05       0  158.25     .06       0  357.59     .05       0
  735.93    .045       0  787.77      .1       0  883.13     .12       0
  970.99      .1       0
Bank Sta=735.93,787.77
XS Rating Curve= 0 ,0
Exp/Cntr(USF)=0,0
Exp/Cntr=0.3,0.1

Type RM Length L Ch R = 1 ,203940  ,192.1,189.4,187.7
XS GIS Cut Line= 4
2434914.08324797525422.3035414682435279.15727106525322.737898807
2435601.56030444525289.5493512542435746.16754735525220.801645607
#Sta/Elev= 30
       0 2168.17    2.63 2167.26    25.6 2158.19    46.3 2148.11    58.7 2140.79
    62.9 2139.23    75.3 2138.21    91.9 2138.64  102.512137.271   116.8 2129.14
   125.1 2126.55   245.3 2117.87   418.2 2110.32   431.9 2110.71   494.6 2108.94
   520.1 2107.45     542 2108.21  571.362106.881   583.1 2104.85   611.2 2105.22
  616.222106.879   627.3 2114.22   640.4 2126.95     656 2140.58   671.5 2150.67
   675.6 2152.15   698.7 2157.64   721.5 2161.56   798.5 2169.69   862.6 2178.92
#Mann= 5 ,-1 , 0
       0      .1       0    2.63     .06       0  102.51     .05       0
  571.36    .045       0  616.22      .1       0
Bank Sta=571.36,616.22
XS Rating Curve= 0 ,0
Exp/Cntr(USF)=0,0
Exp/Cntr=0.3,0.1

Type RM Length L Ch R = 1 ,203751  ,305,308.5,311.9
XS GIS Cut Line= 4
2434840.59432124525592.9875003152435174.85040732525555.057731682
2435620.52518875525469.715752259 2435791.2091476525355.926446361
#Sta/Elev= 30
       0 2186.32    3.172185.935    14.2 2183.69    26.3 2179.33    50.5 2167.93
    82.7 2150.73   102.62144.494     127 2137.78  149.682138.465   183.3 2137.29
   191.4 2135.73  202.032136.379   215.5 2136.06   235.2 2132.44  301.462127.071
     377 2119.63   486.2 2111.02     601 2105.56     654 2106.08   666.2 2108.44
  676.712105.029   702.2 2102.77  722.032105.029   739.5 2109.16   747.6 2115.64
   760.3 2131.92   763.9 2134.65   770.6 2137.13   926.5 2149.34   995.3 2160.34
#Mann= 8 ,-1 , 0
       0      .1       0    3.17     .05       0   102.6     .06       0
  149.68     .05       0  202.03     .06       0  301.46     .05       0
  676.71    .045       0  722.03      .1       0
#XS Ineff= 2 , 0
          662.42 2106.84
Permanent Ineff=
       F       F
Bank Sta=676.71,722.03
XS Rating Curve= 0 ,0
Exp/Cntr(USF)=0,0
Exp/Cntr=0.3,0.1

Type RM Length L Ch R = 1 ,203442  ,298.4,284.9,274.5
XS GIS Cut Line= 4
2434999.42522739525853.7546596642435362.12863994525803.971838334
2435584.96603066525789.7481750972435980.85799076525732.853522148
#Sta/Elev= 30
       0  2164.5      52 2157.57   86.782149.401    92.2 2148.07   101.3 2143.46
   128.5 2143.63   152.7 2137.87  186.132132.549   314.1 2118.03   390.3 2107.63
   414.8 2105.62     495 2103.06     511 2107.19     515 2105.91  520.382102.183
   531.1 2099.73   543.1 2099.55  555.332102.182  584.482106.769   591.2 2107.35
   614.7 2104.29     756 2103.38   770.2 2105.12  783.182110.969   821.5 2133.61
   849.8 2144.81  882.512154.989   922.6 2168.72  981.842191.635   989.4 2194.39
#Mann= 9 ,-1 , 0
       0     .05       0   86.78     .06       0  186.13     .05       0
  520.38    .045       0  555.33     .05       0  584.48      .1       0
  783.18      .1       0  882.51      .1       0  981.84      .1       0
#XS Ineff= 2 , 0
          509.59 2107.68
Permanent Ineff=
       F       F
Bank Sta=520.38,555.33
XS Rating Curve= 0 ,0
Exp/Cntr(USF)=0,0
Exp/Cntr=0.3,0.1

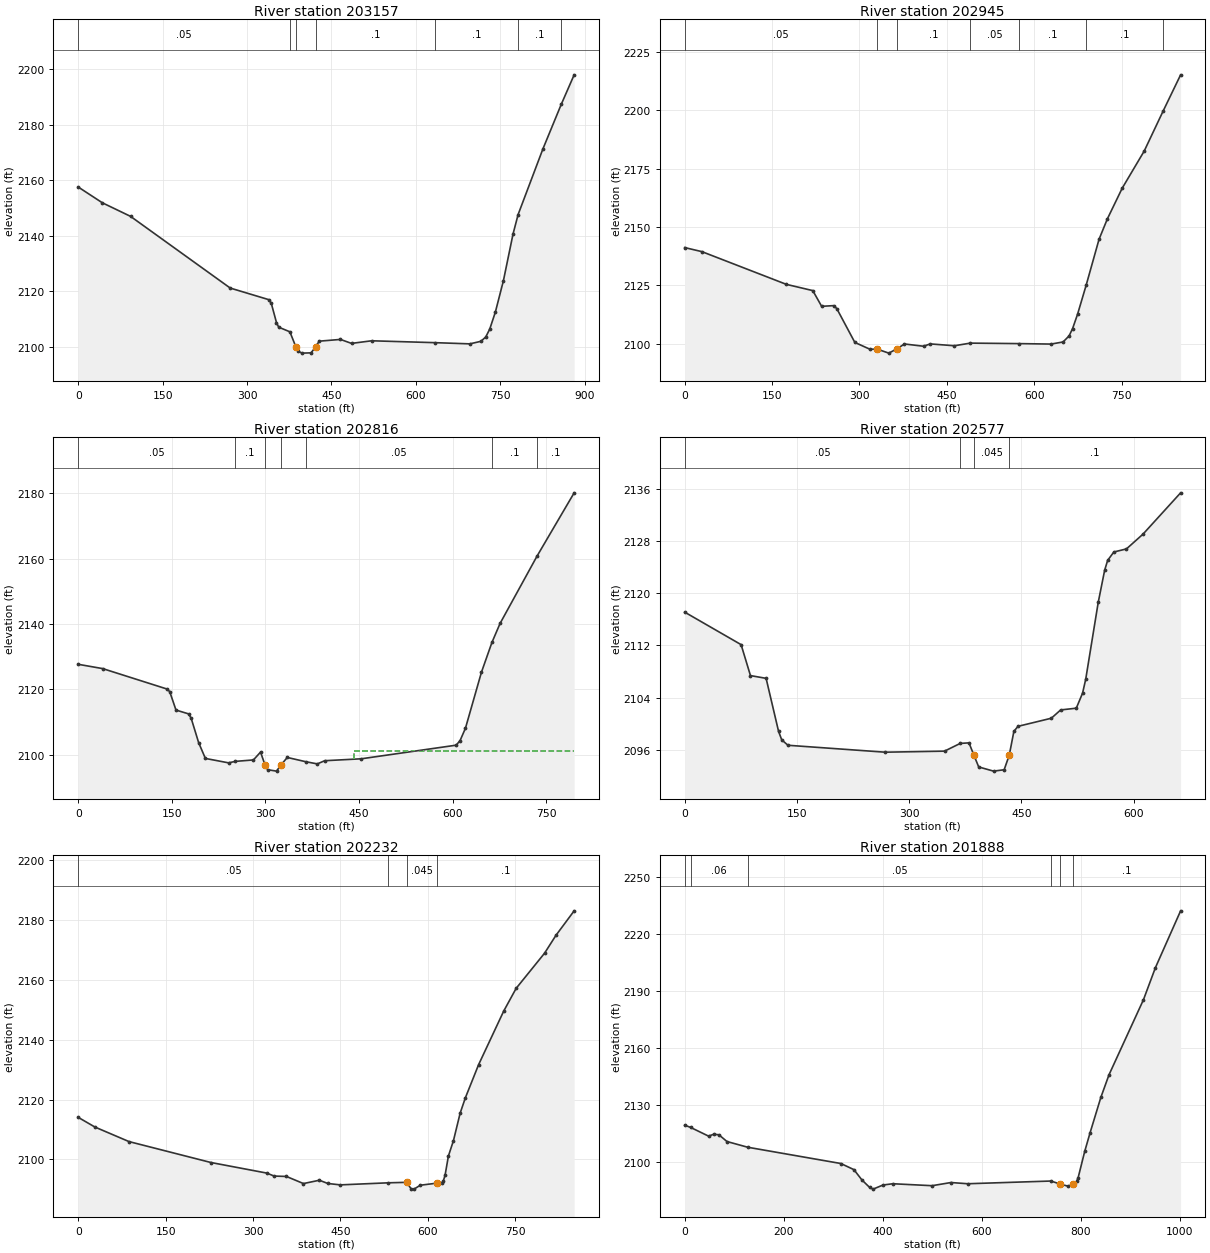
Type RM Length L Ch R = 1 ,203157  ,213.2,212.5,211.9
XS GIS Cut Line= 4
2435250.70994458526216.458072213 2435575.4835885526090.815713618
2435907.36906404525834.7897753482435999.82287508525768.412680241
#Sta/Elev= 30
       0 2157.54    42.9 2151.85      93 2146.96   270.1 2121.11   338.9 2116.91
   343.1 2115.57   352.3 2108.66   356.2 2107.01   376.1 2105.34  386.612099.966
   390.4 2098.34   397.8 2097.65   413.6 2097.75  422.272099.964   428.1 2101.96
     466 2102.59   485.6 2101.16   521.4  2102.1  634.012101.422   695.9 2100.99
   715.5 2101.91   724.1 2103.47   731.2 2106.31   741.2 2112.44   755.5 2123.76
   772.6 2140.59  781.64 2147.62   825.7 2171.28  858.272187.339   881.2 2197.99
#Mann= 7 ,-1 , 0
       0     .05       0   376.1      .1       0  386.61    .045       0
  422.27      .1       0  634.01      .1       0  781.64      .1       0
  858.27      .1       0
Bank Sta=386.61,422.27
XS Rating Curve= 0 ,0
Exp/Cntr(USF)=0,0
Exp/Cntr=0.3,0.1

Type RM Length L Ch R = 1 ,202945  ,127.6,128.9,129.7
XS GIS Cut Line= 4
2435480.65916692526436.9248523912435667.93739954526292.317609479
2436056.71752803525972.2851866412436118.35340206525879.831375599
#Sta/Elev= 30
       0 2141.22    29.5 2139.48   174.5 2125.46   219.9 2122.78   235.1 2116.05
   255.8 2116.34     261 2115.11   292.1 2100.57     318 2097.66   330.6 2097.69
   350.4 2095.99   363.9 2097.77   377.3 2099.91   410.1 2098.94   421.5 2099.94
     463 2099.15  490.222100.279  574.192100.067   628.8 2099.87   649.5 2100.77
   659.9 2103.38   665.9 2106.54   674.4 2112.65  689.162125.095   711.3 2144.79
   725.5 2153.48     751 2166.65   788.8 2182.58  821.342199.749   851.3 2215.24
#Mann= 7 ,-1 , 0
       0     .05       0   330.6    .045       0   363.9      .1       0
  490.22     .05       0  574.19      .1       0  689.16      .1       0
  821.34      .1       0
Bank Sta=330.6,363.9
XS Rating Curve= 0 ,0
Exp/Cntr(USF)=0,0
Exp/Cntr=0.3,0.1

Type RM Length L Ch R = 1 ,202816  ,236.4,239.2,237.4
XS GIS Cut Line= 4
2435566.00114634526508.043168577 2435689.2728944526432.183631312
2436021.15836993526178.5283035812436158.65378123525991.250070957
#Sta/Elev= 30
       0 2127.67    39.2 2126.36   141.8 2120.15   146.6 2119.35   156.7 2113.69
   176.8 2112.53     181  2111.2     193 2103.74   203.8 2098.91   240.9 2097.56
  251.732098.008   280.8 2098.45   292.2 2100.84  299.142097.055   303.7 2095.46
   317.8 2095.03  325.532097.055   335.1 2099.21   364.42097.918   383.2 2097.24
     395 2098.21   453.7  2098.8   605.7 2102.96     612 2104.37   620.6 2108.14
   646.3 2125.29  663.062134.364   676.1 2140.17  735.442160.772   794.8 2180.07
#Mann= 7 ,-1 , 0
       0     .05       0  251.73      .1       0  299.14    .045       0
  325.53      .1       0   364.4     .05       0  663.06      .1       0
  735.44      .1       0
#XS Ineff= 2 , 0
                          441.64         2101.25
Permanent Ineff=
       F       F
Bank Sta=299.14,325.53
XS Rating Curve= 0 ,0
Exp/Cntr(USF)=0,0
Exp/Cntr=0.3,0.1

Type RM Length L Ch R = 1 ,202577  ,334.2,344.5,345
XS GIS Cut Line= 4
2435646.60190469526588.6439269212435976.11676968 526489.07828426
2436066.19997019526391.8832521392436243.99576065 526337.35920973
#Sta/Elev= 30
       0  2117.1    75.4 2112.12    87.9 2107.38   108.8 2106.96   125.5 2098.82
   129.7 2097.54     138 2096.71   267.9 2095.65   347.2 2095.81   368.22096.995
   379.9 2097.08  386.422095.202   392.9 2093.39   412.7 2092.75   426.9 2092.96
  433.73  2095.2   439.9 2098.84   445.4 2099.61   489.9 2100.85   502.4 2102.12
   523.3 2102.39   531.7  2104.7   535.9 2106.83   552.6 2118.59   561.2 2123.52
   565.2 2125.03   573.5 2126.31   590.3 2126.78   612.5 2129.05   662.7 2135.37
#Mann= 4 ,-1 , 0
       0     .05       0   368.2      .1       0  386.42    .045       0
  433.73      .1       0
Bank Sta=386.42,433.73
XS Rating Curve= 0 ,0
Exp/Cntr(USF)=0,0
Exp/Cntr=0.3,0.1

Type RM Length L Ch R = 1 ,202232  ,353.3,344.2,341
XS GIS Cut Line= 4
2435641.86068361527046.1717610522435883.66295864526894.452686521
2436229.77209741526655.0210220282436348.30262439526572.049653144
#Sta/Elev= 30
       02114.072  28.7512110.827  87.1682105.972 227.7092098.978 323.2542095.453
 336.2342094.447 357.3012094.313 386.4842091.938 413.8592093.051 428.2342091.965
 449.7142091.498 532.3992092.192 563.3582092.348  571.312090.169 576.1742090.077
 587.018 2091.38 615.0852092.062 623.733 2092.08 626.6082092.891 629.483 2094.69
 635.2332101.151 643.8582106.265 655.358 2115.47 664.358 2120.62 686.9822131.665
 730.0842149.588 751.4462157.201 800.2722168.969 819.8022174.938 850.9992183.123
#Mann= 4 ,-1 , 0
       0     .05       0 532.399      .1       0 563.358    .045       0
 615.085      .1       0
Bank Sta=563.358,615.085
XS Rating Curve= 0 ,0
Exp/Cntr(USF)=0,0
Exp/Cntr=0.3,0.1

Type RM Length L Ch R = 1 ,201888  ,692.1,703,694.3
XS GIS Cut Line= 4
2435833.88013731527418.3576157592436042.49386479527242.932435834
2436454.98009867526884.9702443632436587.73428888526759.327885768
#Sta/Elev= 30
       0  2119.2   11.762118.033    48.2 2113.42    58.6  2114.4    69.1 2114.13
    85.4 2110.57  127.452107.546   315.4 2098.97   341.8 2095.73   357.8 2090.34
   373.5 2086.35   380.5 2085.46   400.4 2087.62   420.2  2088.3   499.6 2087.27
   537.7 2088.94   571.7  2088.3   739.6 2089.73   757.6 2088.19   774.7 2086.97
  785.082088.195   791.7 2089.61   794.5 2091.42   807.8 2105.33   818.7 2115.22
   840.4 2133.83   856.9 2145.78   926.5 2185.39   950.6 2202.27  1001.5 2232.25
#Mann= 6 ,-1 , 0
       0     .12       0   11.76     .06       0  127.45     .05       0
   739.6      .1       0   757.6    .045       0  785.08      .1       0
Bank Sta=757.6,785.08
XS Rating Curve= 0 ,0
Exp/Cntr(USF)=0,0
Exp/Cntr=0.3,0.1

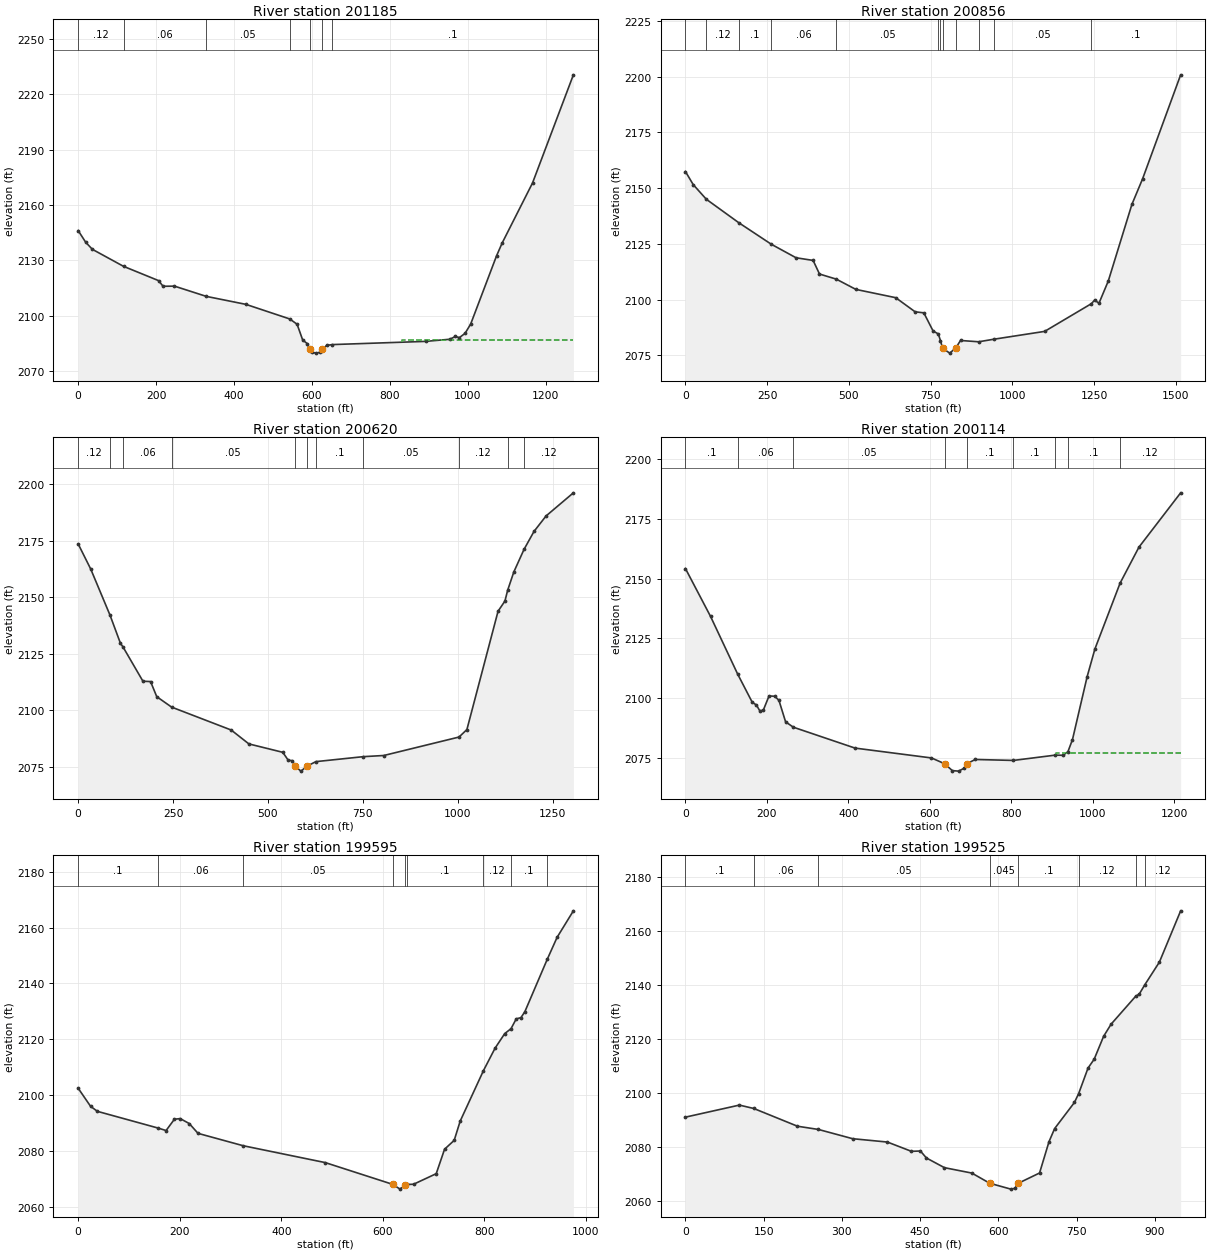
Type RM Length L Ch R = 1 ,201185  ,333.3,329.6,324.9
XS GIS Cut Line= 4
2435886.03356918527736.0194280572436296.14919252527498.958374104
2436763.15946881527183.6671723452436910.13732226527001.130160801
#Sta/Elev= 30
       0 2146.11    19.3 2139.78    36.5 2135.95  116.382126.746   206.3 2119.01
     218 2115.94   247.3 2116.01  328.892110.468   430.5 2106.15  543.422098.218
   562.1 2095.36   576.5 2086.81     588 2084.92  594.622081.831   599.5 2080.12
     611 2079.72   621.6  2080.2  627.052081.831   638.2 2083.92  652.84 2084.35
   891.9 2086.08   954.6 2087.24   968.3 2088.75   978.8 2088.13   993.2  2090.4
  1007.7 2095.42  1074.1 2132.36  1088.6 2139.37  1166.6  2171.9  1271.5 2230.49
#Mann= 7 ,-1 , 0
       0     .12       0  116.38     .06       0  328.89     .05       0
  543.42     .07       0  594.62    .045       0  627.05     .07       0
  652.84      .1       0
#XS Ineff= 2 , 0
                          832.33          2086.9
Permanent Ineff=
       F       F
Bank Sta=594.62,627.05
XS Rating Curve= 0 ,0
Exp/Cntr(USF)=0,0
Exp/Cntr=0.3,0.1

Type RM Length L Ch R = 1 ,200856  ,235.5,235.4,234.6
XS GIS Cut Line= 4
2435847.10832353527836.8631567752436544.45298765527750.146721858
 2436866.0264338527421.3469061312437032.23293406527110.613014346
#Sta/Elev= 30
       0 2157.47    23.8 2151.58   64.072144.994  163.462134.448  262.852124.798
   338.4 2118.74   390.6 2117.55   410.1 2111.44  461.622109.138   521.3 2104.54
   643.2 2100.82   702.7 2094.47   729.3 2094.01   757.6 2085.86  773.592084.545
  780.142081.553  786.692078.133   808.5 2075.92  826.412078.134   841.6  2081.6
  897.022081.017  942.922082.149  1098.9 2085.68    12422098.133  1251.6 2099.71
  1265.2 2098.35  1293.7 2108.34  1365.9 2142.73  1398.5 2154.17    1515 2200.89
#Mann= 12 ,-1 , 0
       0      .1       0   64.07     .12       0  163.46      .1       0
  262.85     .06       0  461.62     .05       0  773.59      .1       0
  780.14     .07       0  786.69    .045       0  826.41     .07       0
  897.02      .1       0  942.92     .05       0    1242      .1       0
Bank Sta=786.69,826.41
XS Rating Curve= 0 ,0
Exp/Cntr(USF)=0,0
Exp/Cntr=0.3,0.1

Type RM Length L Ch R = 1 ,200620  ,508.2,506.7,504.5
XS GIS Cut Line= 4
2436392.69922655528274.0585161472436699.81993355527930.805961268
2437035.84611885527573.1006672362437270.70313008527309.338177697
#Sta/Elev= 30
       0 2173.56    33.1 2162.43   83.862142.033   111.3 2129.59  118.392127.865
   170.6 2112.77   190.7 2112.62     207 2105.93  246.142101.311   403.1 2091.16
   449.7 2085.01     539 2081.29   553.2 2077.81   564.5 2077.57  570.782075.238
   586.7 2072.96  603.652075.238  626.172077.167  751.492079.372     805 2079.88
 1003.212088.051    1024 2091.36  1106.1 2143.78  1124.2 2148.28  1131.22152.969
  1147.6 2161.16 1174.542171.172  1200.7 2179.09  1232.6 2185.97  1304.5  2196.2
#Mann= 11 ,-1 , 0
       0     .12       0   83.86      .1       0  118.39     .06       0
  246.14     .05       0  570.78    .045       0  603.65     .05       0
  626.17      .1       0  751.49     .05       0 1003.21     .12       0
  1131.2      .1       0 1174.54     .12       0
Bank Sta=570.78,603.65
XS Rating Curve= 0 ,0
Exp/Cntr(USF)=0,0
Exp/Cntr=0.3,0.1

Type RM Length L Ch R = 1 ,200114  ,514.1,518.1,514.8
XS GIS Cut Line= 4
2436761.24407495528693.1879515782437068.36478194528292.124440088
2437342.96682585527948.8718852092437523.62606526527746.533537069
#Sta/Elev= 30
       0 2154.22    61.7 2134.19   128.32110.074   164.1  2098.3   174.2 2097.21
   182.5 2094.77     191 2094.96   205.3 2100.99   219.4 2100.83   229.6 2099.12
   245.9 2090.16  264.872087.912   416.4 2079.18   604.1 2075.06  636.122072.672
   655.3 2069.77   670.6 2069.55   684.2 2070.74  691.342072.672   711.6 2074.42
  805.21 2074.02  908.062076.237   926.8 2076.17  939.12 2077.63   950.4 2082.76
   986.4 2109.05  1005.5 2120.64 1067.232148.109  1113.6 2163.17    1216 2185.87
#Mann= 9 ,-1 , 0
       0      .1       0   128.3     .06       0  264.87     .05       0
  636.12    .045       0  691.34      .1       0  805.21      .1       0
  908.06     .12       0  939.12      .1       0 1067.23     .12       0
#XS Ineff= 2 , 0
                          910.74         2077.23
Permanent Ineff=
       F       F
Bank Sta=636.12,691.34
XS Rating Curve= 0 ,0
Exp/Cntr(USF)=0,0
Exp/Cntr=0.5,0.3

Type RM Length L Ch R = 1 ,199595  ,70.2,70.1,74.4
XS GIS Cut Line= 4
 2437111.7229994528891.9131149292437444.13599992528566.726483991
2437653.70071763528339.095842334 2437754.8698917528165.662972501
#Sta/Elev= 30
       0 2102.43    24.3 2095.98    37.8 2094.15  157.232088.167   173.1 2087.27
   189.5 2091.32   200.9 2091.55   218.8 2089.77     236 2086.26  325.012081.822
   486.6 2075.78   619.6 2067.97   633.8 2066.27   644.2 2067.74  647.462067.941
   660.5 2068.02   705.1 2071.81   721.5 2080.57   740.5 2083.76   752.3 2090.66
  798.162108.767     821  2116.8     840 2122.02  852.362123.774   862.7 2127.31
   871.9 2127.73   879.7 2129.89  923.812148.678   943.2 2156.54   975.2 2166.02
#Mann= 9 ,-1 , 0
       0      .1       0  157.23     .06       0  325.01     .05       0
   619.6    .045       0   644.2     .05       0  647.46      .1       0
  798.16     .12       0  852.36      .1       0  923.81      .1       0
#XS Ineff= 2 , 0
             590 2068.67     674         2068.67
Permanent Ineff=
       F       F
Bank Sta=619.6,644.2
XS Rating Curve= 0 ,0
Exp/Cntr(USF)=0,0
Exp/Cntr=0.5,0.3

Type RM Length L Ch R = 1 ,199525  ,254.2,251.3,248.5
XS GIS Cut Line= 4
 2437189.4033626528925.1269525892437575.51447371528526.515841484
2437646.34780705528451.5158414842437842.18114036528236.238063693
#Sta/Elev= 30
       0 2090.95   103.4 2095.41  131.042094.149   214.7 2087.59  254.91 2086.39
   320.5 2082.97   387.1 2081.73   433.1  2078.3   450.4 2078.42   461.9 2075.83
   496.4 2072.25   548.9 2070.25  583.222066.484   623.7 2064.31   631.5 2064.61
     6382066.485   678.7 2070.28   696.8 2081.86   707.6 2086.72   745.5 2096.37
  753.68 2099.68   771.6 2109.11   783.4 2112.39   801.4 2120.83   815.8 2125.35
  862.652135.622   869.8  2136.5  880.582139.978   908.4 2148.33 949.139  2167.3
#Mann= 8 ,-1 , 0
       0      .1       0  131.04     .06       0  254.91     .05       0
  583.22    .045       0     638      .1       0  753.68     .12       0
  862.65      .1       0  880.58     .12       0
Bank Sta=583.22,638
XS Rating Curve= 0 ,0
Exp/Cntr(USF)=0,0
Exp/Cntr=0.5,0.3