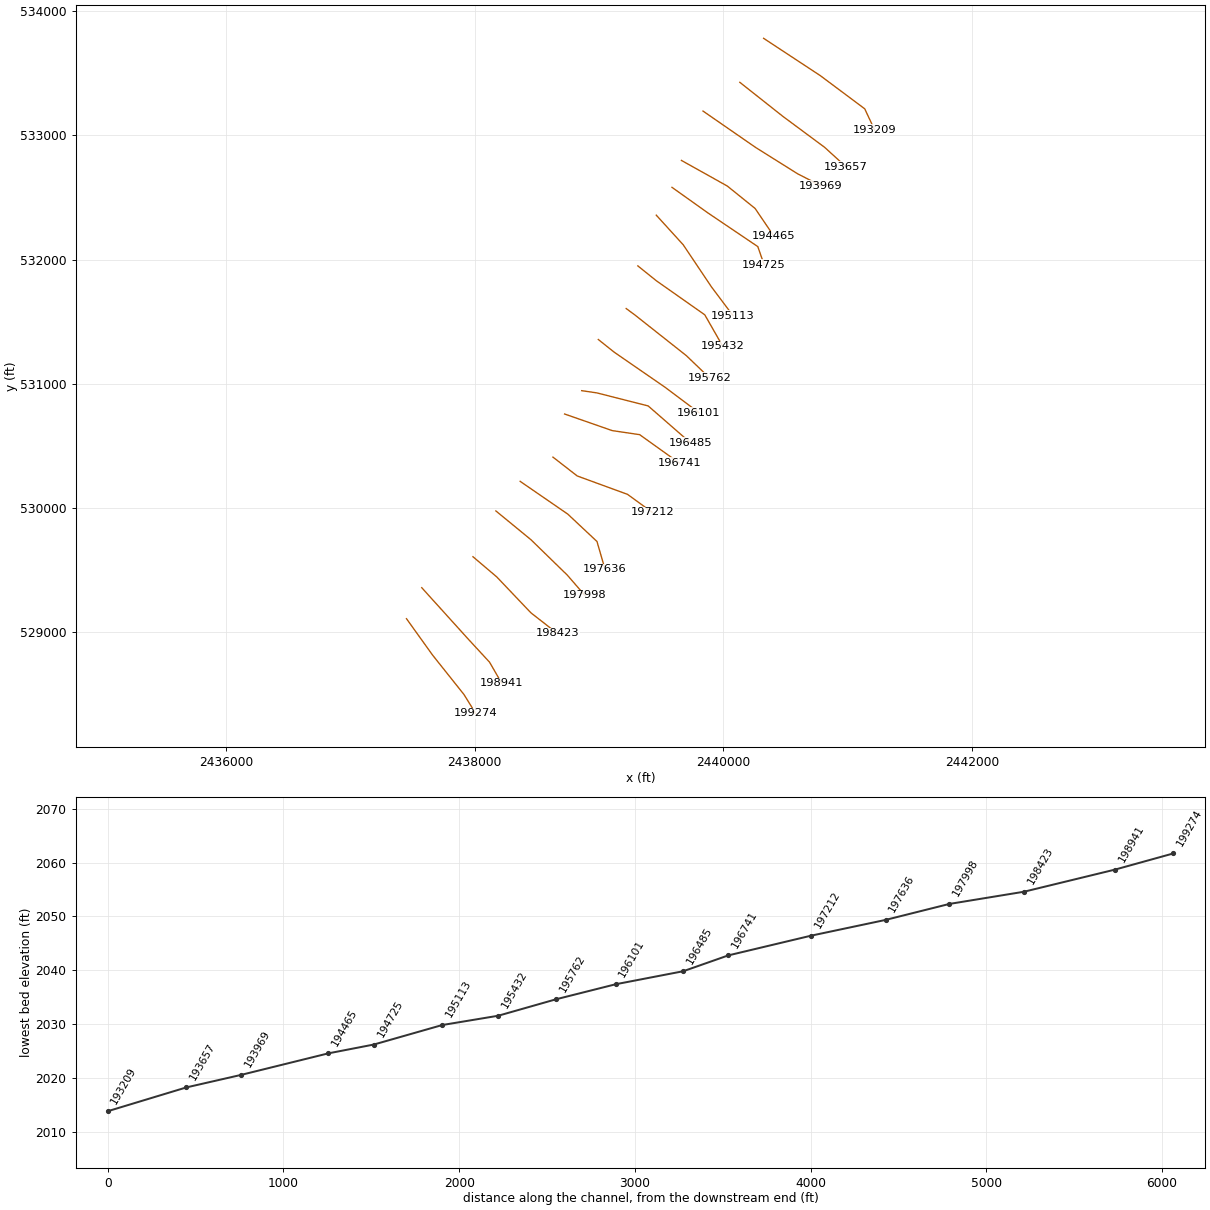
HEC-RAS study SFSBPOTOMC.prj: SFSBPOTOMC

--- SFSBPOTOMC.g01 (geometry) --- (continued)

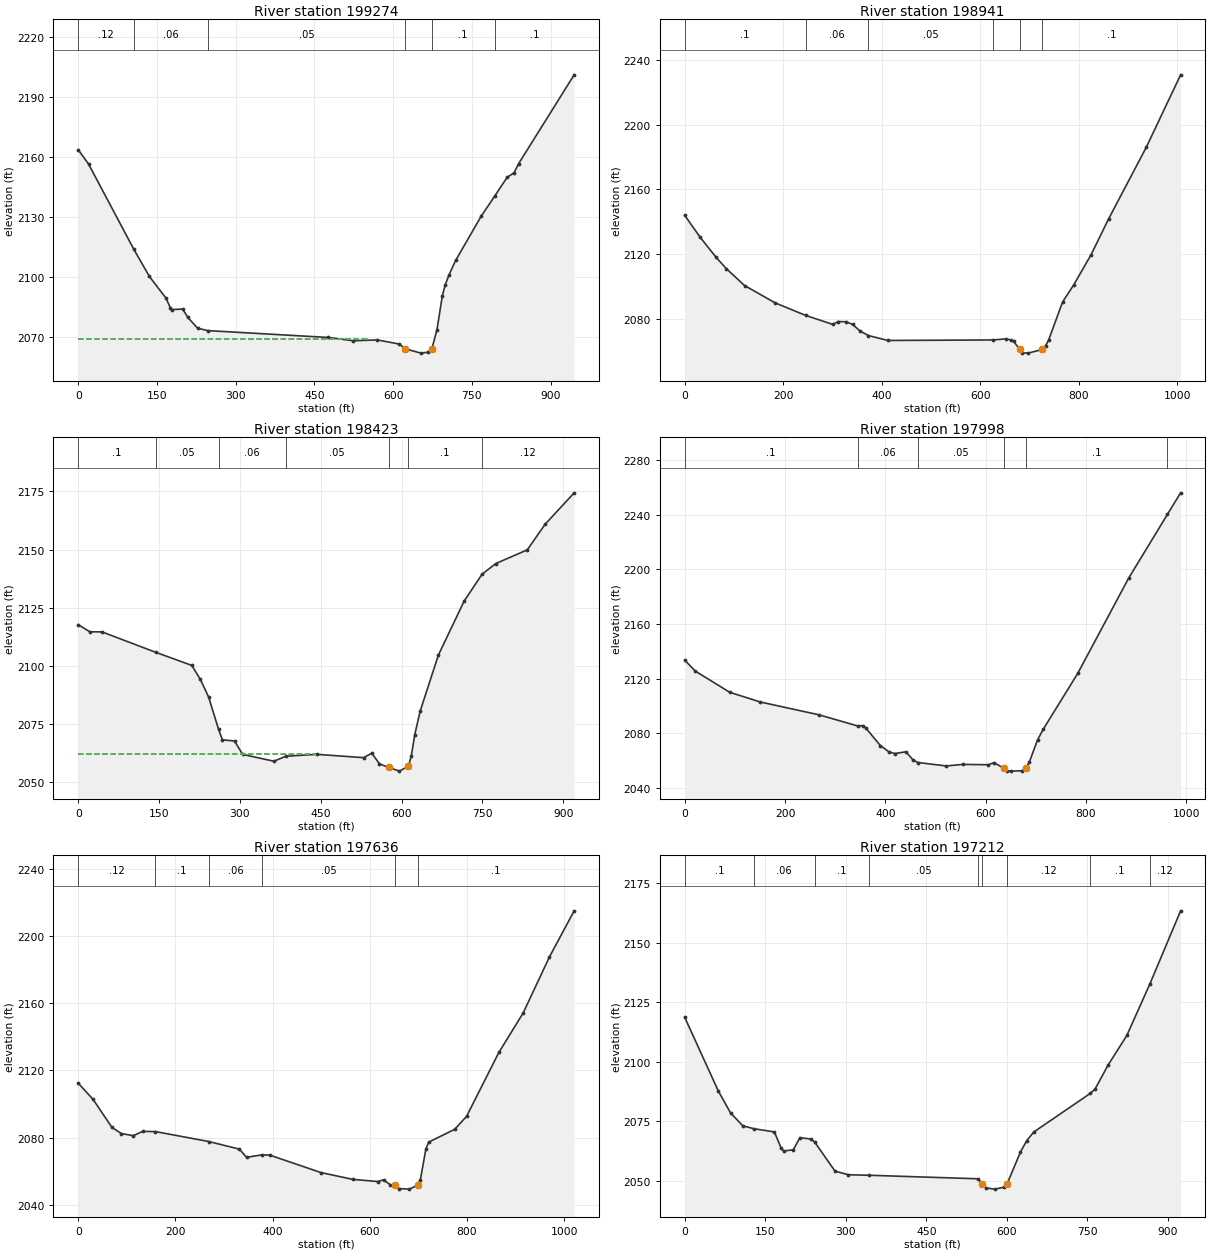
Type RM Length L Ch R = 1 ,199274  ,329.5,332.5,332.1
XS GIS Cut Line= 4
2437451.36236949529108.7042022212437660.92708721528816.036234377
2437913.85002238528498.0759730152438007.79282688528346.322211911
#Sta/Elev= 30
       0 2163.53    19.6 2156.43   105.72113.809   135.6 2100.09   167.1 2089.27
   175.7 2084.34   179.3 2083.54     199 2083.77   208.9 2079.56   227.3 2074.22
  246.612072.993   475.9 2069.57   524.3 2067.89   569.9 2068.33   611.9 2066.25
   622.92063.899   652.8 2061.72   666.7 2062.19   673.72063.895   683.4 2073.44
   693.6 2090.39   698.8  2095.6   706.5 2101.04   719.2 2108.24   767.9 2130.39
  793.11 2140.23     817 2149.71   830.2 2151.98   838.9 2156.55   944.7 2201.04
#Mann= 6 ,-1 , 0
       0     .12       0   105.7     .06       0  246.61     .05       0
   622.9    .045       0   673.7      .1       0  793.11      .1       0
#XS Ineff= 2 , 0
          549.22 2069.03
Permanent Ineff=
       F       F
Bank Sta=622.9,673.7
XS Rating Curve= 0 ,0
Exp/Cntr(USF)=0,0
Exp/Cntr=0.3,0.1

Type RM Length L Ch R = 1 ,198941  ,517.7,518.5,518.7
XS GIS Cut Line= 4
2437574.21065229529358.0139526072437946.36868548528946.110886752
2438119.80155531528758.2252777662438217.35754459 528588.40559272
#Sta/Elev= 30
       0 2143.97    31.2 2130.47    63.5 2118.07    84.3 2111.03   121.5 2100.53
   183.8 2089.77  245.712082.026   300.7 2076.48   311.5 2078.23   328.3 2078.12
   340.9 2076.42   356.6 2072.26  372.952069.583   412.5 2066.54  626.832066.869
   652.1 2067.54   662.4 2066.84   668.1 2065.91   680.1 2060.99   685.4 2058.89
   697.2 2058.71  726.012060.988   732.6 2063.27   738.8 2066.83   767.1 2090.34
   789.8 2100.96   824.8  2119.5   860.8  2141.9   937.2 2186.14  1006.7 2230.84
#Mann= 6 ,-1 , 0
       0      .1       0  245.71     .06       0  372.95     .05       0
  626.83      .1       0   680.1    .045       0  726.01      .1       0
Bank Sta=680.1,726.01
XS Rating Curve= 0 ,0
Exp/Cntr(USF)=0,0
Exp/Cntr=0.3,0.1

Type RM Length L Ch R = 1 ,198423  ,424.1,424.5,424.6
XS GIS Cut Line= 4
2437986.11371815529607.3237029932438177.61251192529444.730387524
2438452.21455582529155.6756044682438665.39245833 528989.46910421
#Sta/Elev= 30
       0 2117.65    21.8 2114.56    43.9 2114.56  143.742105.759   210.8  2100.1
   226.5 2094.11     242 2086.48   260.4 2072.57   267.5 2068.09   290.1 2067.55
   305.1 2061.79   363.2 2058.85  385.192061.005   442.9 2061.81   529.6 2060.39
   544.7 2062.33   558.9 2057.73   575.9 2056.23   595.7 2054.59   612.4 2056.64
   617.9 2060.91   624.5 2070.34   634.4 2080.38   668.3 2104.55   716.2 2127.85
  749.422139.386   774.8 2143.96   833.3 2149.87   866.1 2160.81   920.2 2174.41
#Mann= 7 ,-1 , 0
       0      .1       0  143.74     .05       0   260.4     .06       0
  385.19     .05       0   575.9    .045       0   612.4      .1       0
  749.42     .12       0
#XS Ineff= 2 , 0
          440.39 2061.91
Permanent Ineff=
       F       F
Bank Sta=575.9,612.4
XS Rating Curve= 0 ,0
Exp/Cntr(USF)=0,0
Exp/Cntr=0.3,0.1

Type RM Length L Ch R = 1 ,197998  ,361.9,362.7,362.6
XS GIS Cut Line= 4
2438170.38614234529975.8685513892438452.21455582529744.624724944
2438744.88252367529459.1831266762438885.79673041529296.589811207
#Sta/Elev= 30
       0 2133.55    20.8 2125.58    89.8 2109.98   150.5  2102.9   268.1 2093.48
  344.772085.358   354.7 2085.58     361 2083.88     390 2071.01   407.1 2066.45
   418.5 2065.16   441.1 2066.47   455.3  2060.4     4652058.622   521.7 2056.09
   554.3 2057.25   605.2 2056.99   616.5 2058.52  636.182054.419   641.9 2052.51
   650.4 2052.32   673.1 2052.64   679.8 2054.42   687.2 2059.17   703.3 2075.15
   714.5 2082.84   783.4 2123.78   884.9 2193.45  962.182240.076   988.5 2255.86
#Mann= 6 ,-1 , 0
       0      .1       0  344.77     .06       0     465     .05       0
  636.18    .045       0   679.8      .1       0  962.18      .1       0
Bank Sta=636.18,679.8
XS Rating Curve= 0 ,0
Exp/Cntr(USF)=0,0
Exp/Cntr=0.3,0.1

Type RM Length L Ch R = 1 ,197636  ,412.1,423.8,433.2
XS GIS Cut Line= 4
2438365.49812091 530214.338747412438748.49570846529950.576257872
2438983.35271969529730.1719857922439048.39004588529506.154528923
#Sta/Elev= 30
       0 2112.43    30.7 2102.73    69.5 2086.06    88.9 2082.43   113.2 2081.18
   132.6 2083.71  158.982083.599  268.872077.672   331.8 2073.14   346.3 2068.28
  378.772069.778   394.5 2069.56   499.6 2059.19   565.4 2055.13   616.2 2053.87
   628.2 2054.89   641.9 2051.96  652.332051.684   660.1 2049.68   681.5 2049.35
  698.372051.684   704.1 2055.06   715.4 2073.36   721.1 2077.32   774.4 2084.92
     799 2092.64   865.5 2130.72   915.5 2154.21   969.6  2187.6  1020.4 2215.02
#Mann= 6 ,-1 , 0
       0     .12       0  158.98      .1       0  268.87     .06       0
  378.77     .05       0  652.33    .045       0  698.37      .1       0
Bank Sta=652.33,698.37
XS Rating Curve= 0 ,0
Exp/Cntr(USF)=0,0
Exp/Cntr=0.3,0.1

Type RM Length L Ch R = 1 ,197212  ,466.1,471.3,476.8
XS GIS Cut Line= 4
2438629.26061045530409.4507259732438824.37258901530257.696964869
2439229.04928529530109.5563885532439427.77444864529965.028997025
#Sta/Elev= 30
       0 2118.72    62.7 2087.67    85.5 2078.46   108.3 2073.06  128.992071.823
   167.1 2070.48   179.2 2063.92   184.3 2062.43   202.4    2063   214.7 2068.06
     235  2067.5  242.18 2066.22     280    2054   305.1 2052.46  343.85 2052.25
  546.14 2050.77  554.432048.771   560.7 2046.95   577.7 2046.42   594.2 2047.18
  600.89 2048.77   625.4    2062   637.3 2066.85   650.3 2070.45  755.472086.673
   764.3 2088.46     789 2098.71   823.6 2111.05  866.762132.848   923.8 2163.48
#Mann= 9 ,-1 , 0
       0      .1       0  128.99     .06       0  242.18      .1       0
  343.85     .05       0  546.14     .12       0  554.43    .045       0
  600.89     .12       0  755.47      .1       0  866.76     .12       0
Bank Sta=554.43,600.89
XS Rating Curve= 0 ,0
Exp/Cntr(USF)=0,0
Exp/Cntr=0.3,0.1

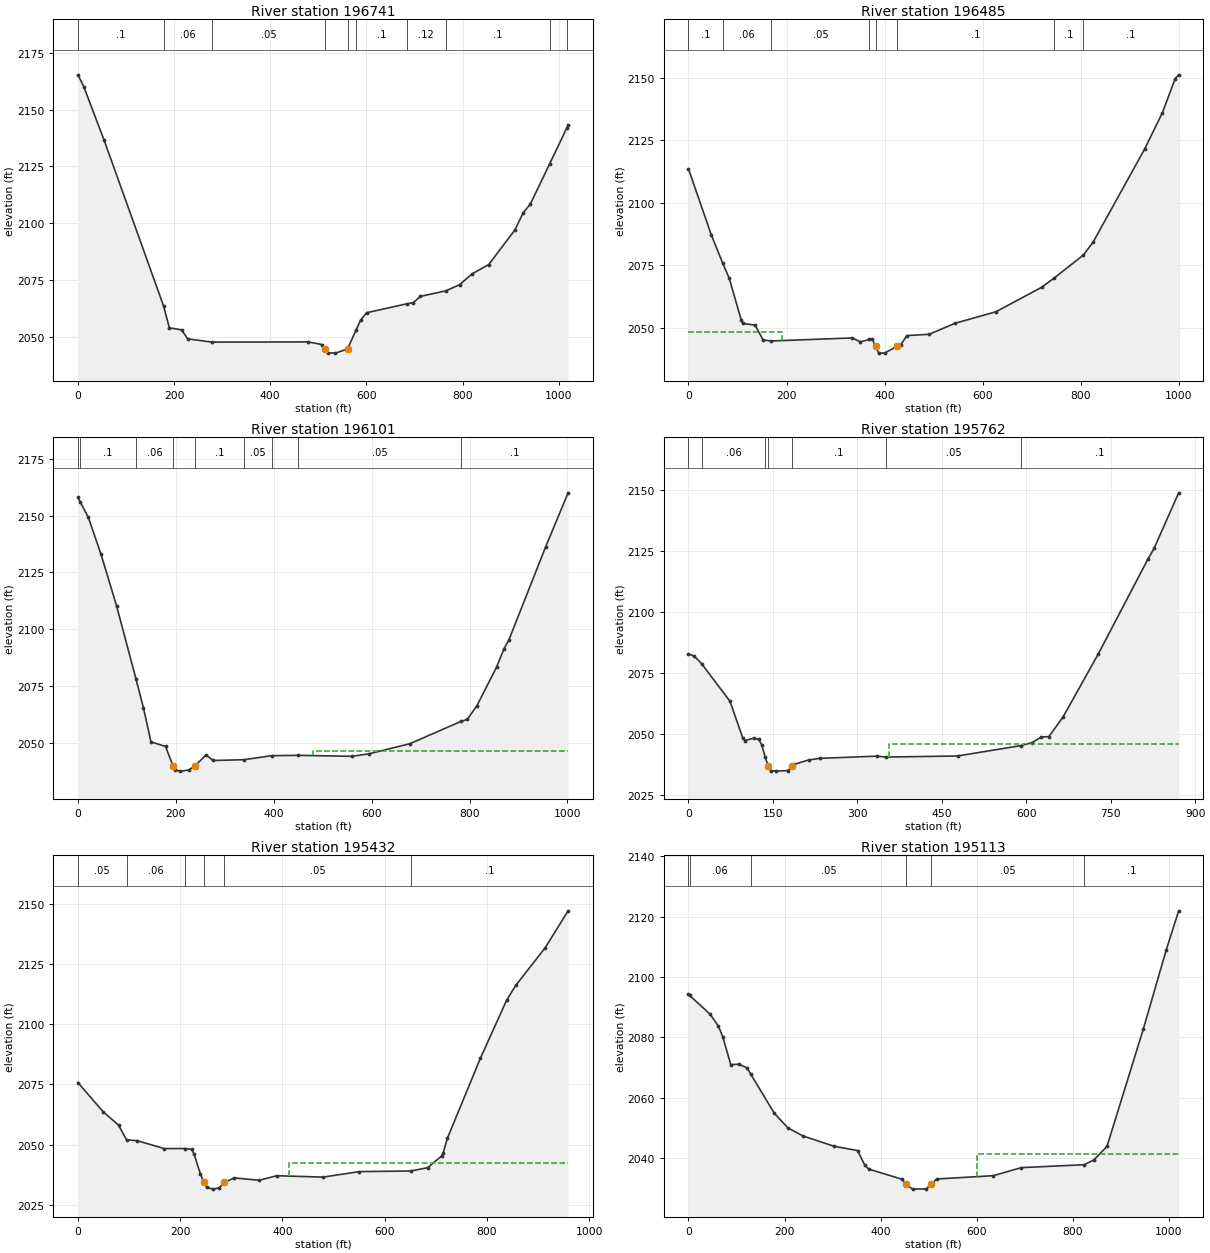
Type RM Length L Ch R = 1 ,196741  ,257.2,255.8,252.4
XS GIS Cut Line= 4
2438723.20341494 530756.316465642439106.20100249530622.628628477
2439326.60527457530590.1099653832439644.56553593530362.479323727
#Sta/Elev= 30
       0 2165.28    12.2 2160.08    54.6 2136.42  178.012063.595   190.2 2053.88
   215.6 2053.01   228.3 2049.03  278.872047.599     479 2047.69   507.3 2046.54
   514.72044.605   519.4 2042.93   535.6 2042.75   560.82044.602  578.782053.057
   588.2 2057.33   600.3 2060.53  683.882064.466   697.5 2064.98   712.3 2067.75
  764.812070.151   794.3 2072.93   819.5 2077.61   854.5 2081.77     909 2097.05
   926.2 2104.64   940.5  2108.2  981.332126.172 1016.492141.774  1019.5 2143.22
#Mann= 10 ,-1 , 0
       0      .1       0  178.01     .06       0  278.87     .05       0
   514.7    .045       0   560.8     .05       0  578.78      .1       0
  683.88     .12       0  764.81      .1       0  981.33      .1       0
 1016.49     .12       0
Bank Sta=514.7,560.8
XS Rating Curve= 0 ,0
Exp/Cntr(USF)=0,0
Exp/Cntr=0.3,0.1

Type RM Length L Ch R = 1 ,196485  ,398.1,384,380.7
XS GIS Cut Line= 4
2438860.50443689530944.2020746272438983.35271969530926.136150686
2439395.25578554530821.3537918282439734.89515564530525.072639196
#Sta/Elev= 30
       0 2113.52    46.7 2087.04   69.852075.795    83.1 2069.82   107.4 2053.18
   111.4 2051.67   135.9 2051.01   152.4 2045.04  169.342044.687     334 2045.88
   350.5 2044.32  368.76 2045.28   375.3 2045.29  381.572042.492   387.7 2039.89
   400.1 2039.81  424.742042.492   433.1  2043.2   445.6 2046.82   490.9 2047.35
   544.5  2051.8   627.1 2056.36   720.7 2066.18  746.612069.957   805.4 2079.02
   825.6  2084.3   930.5 2121.47   966.7 2135.97   992.8 2149.65   999.9 2151.16
#Mann= 8 ,-1 , 0
       0      .1       0   69.85     .06       0  169.34     .05       0
  368.76      .1       0  381.57    .045       0  424.74      .1       0
  746.61      .1       0   805.4      .1       0
#XS Ineff= 2 , 0
          190.41 2048.41
Permanent Ineff=
       F       F
Bank Sta=381.57,424.74
XS Rating Curve= 0 ,0
Exp/Cntr(USF)=0,0
Exp/Cntr=0.3,0.1

Type RM Length L Ch R = 1 ,196101  ,339.5,339.1,337.3
XS GIS Cut Line= 4
2438994.19227405531356.1051404822439120.65374164531254.935966412
2439528.94362271530973.1075529322439803.54566661530767.156020005
#Sta/Elev= 30
       0 2158.06    4.372156.196    21.2 2149.29    46.8 2133.21    78.8 2110.38
  118.422078.153   133.9 2065.28   149.2 2050.29   179.1 2048.25  194.192039.668
   198.5 2037.88   209.5 2037.39   226.7 2037.88  238.692039.668   261.7 2044.49
   276.3 2042.08  339.892042.435   395.52044.198  449.842044.348   560.3 2043.92
   594.8 2045.04   678.1 2049.48  782.112059.275   795.3  2060.2   815.1 2066.26
   855.1  2083.2   870.3  2091.3   880.3 2095.23   955.2 2136.15  1001.3 2160.08
#Mann= 9 ,-1 , 0
       0     .12       0    4.37      .1       0  118.42     .06       0
  194.19    .045       0  238.69      .1       0  339.89     .05       0
   395.5      .1       0  449.84     .05       0  782.11      .1       0
#XS Ineff= 2 , 0
                             480         2046.27
Permanent Ineff=
       F       F
Bank Sta=194.19,238.69
XS Rating Curve= 0 ,0
Exp/Cntr(USF)=0,0
Exp/Cntr=0.3,0.1

Type RM Length L Ch R = 1 ,195762  ,328.5,329.9,331.4
XS GIS Cut Line= 4
2439218.20973092531605.414890868 2439286.8602419531554.830303833
2439702.37649254531226.0304881072439886.64891674531048.984433485
#Sta/Elev= 30
       0  2082.7    10.6 2081.72   23.85 2078.51    73.7 2063.27    96.5 2048.17
   100.4 2047.14   115.7 2048.12     125  2047.6   130.3 2045.29  136.422040.268
  141.652036.625   146.3 2034.83   156.1  2034.6   176.9 2034.85  184.332036.628
   187.7 2037.38   213.3 2039.17   233.1 2039.84   335.1 2040.75  350.852040.373
   477.9 2040.81  591.282045.101   610.5 2046.31   626.8 2048.59   640.3 2048.77
   665.6 2056.91     728 2082.69     816 2121.53     827 2125.94   870.7 2148.76
#Mann= 7 ,-1 , 0
       0      .1       0   23.85     .06       0  136.42      .1       0
  141.65    .045       0  184.33      .1       0  350.85     .05       0
  591.28      .1       0
#XS Ineff= 2 , 0
                          356.16         2045.57
Permanent Ineff=
       F       F
Bank Sta=141.65,184.33
XS Rating Curve= 0 ,0
Exp/Cntr(USF)=0,0
Exp/Cntr=0.3,0.1

Type RM Length L Ch R = 1 ,195432  ,327.7,318.7,309.8
XS GIS Cut Line= 4
2439312.15253542531948.6674457472439460.29311173531829.432347736
2439850.51706886531554.8303038332439995.04446039531301.907368659
#Sta/Elev= 30
       0 2075.77    49.5 2063.65    79.4 2058.12   95.192051.993   116.3 2051.63
   168.7 2048.37  208.792048.393   222.5 2048.03   227.4 2045.95   239.3 2037.96
  246.372034.325   251.9 2032.21   264.1 2031.53   276.3 2032.05  286.252034.325
   305.7 2036.19   354.6 2035.22   388.8 2037.09   479.6 2036.53   550.2  2038.8
  650.51 2039.07   683.9 2040.43   711.4 2045.34   714.4 2046.65   722.5 2052.64
     787 2085.86   838.5 2110.05   856.1 2116.11   913.8 2131.78   958.6 2147.12
#Mann= 6 ,-1 , 0
       0     .05       0   95.19     .06       0  208.79     .05       0
  246.37    .045       0  286.25     .05       0  650.51      .1       0
#XS Ineff= 2 , 0
                          412.92         2042.58
Permanent Ineff=
       F       F
Bank Sta=246.37,286.25
XS Rating Curve= 0 ,0
Exp/Cntr(USF)=0,0
Exp/Cntr=0.3,0.1

Type RM Length L Ch R = 1 ,195113  ,375.4,388.3,397.5
XS GIS Cut Line= 4
2439460.29311173532356.9573268132439677.08419902532118.487130792
2439904.71484068531778.8477607012440078.14771051531547.603934256
#Sta/Elev= 30
       0 2094.22    2.392093.887    45.3 2087.65    62.3 2083.73    71.2 2080.29
    88.1    2071   104.7 2071.15   122.1 2069.91  129.332067.901   178.8 2054.88
   207.1 2050.05   238.2  2047.4   303.4 2043.97     352 2042.56   366.4 2037.88
   374.8 2036.45   444.3 2033.08  453.182031.391   466.3  2029.8   495.1 2029.88
  504.452031.391   516.4 2033.16   634.2 2034.24   692.6 2036.91  823.542037.879
     844  2039.5   871.1 2043.96   946.9 2082.92   994.5 2109.02  1020.2  2121.9
#Mann= 6 ,-1 , 0
       0     .05       0    2.39     .06       0  129.33     .05       0
  453.18    .045       0  504.45     .05       0  823.54      .1       0
#XS Ineff= 2 , 0
                          600.66         2041.29
Permanent Ineff=
       F       F
Bank Sta=453.18,504.45
XS Rating Curve= 0 ,0
Exp/Cntr(USF)=0,0
Exp/Cntr=0.3,0.1

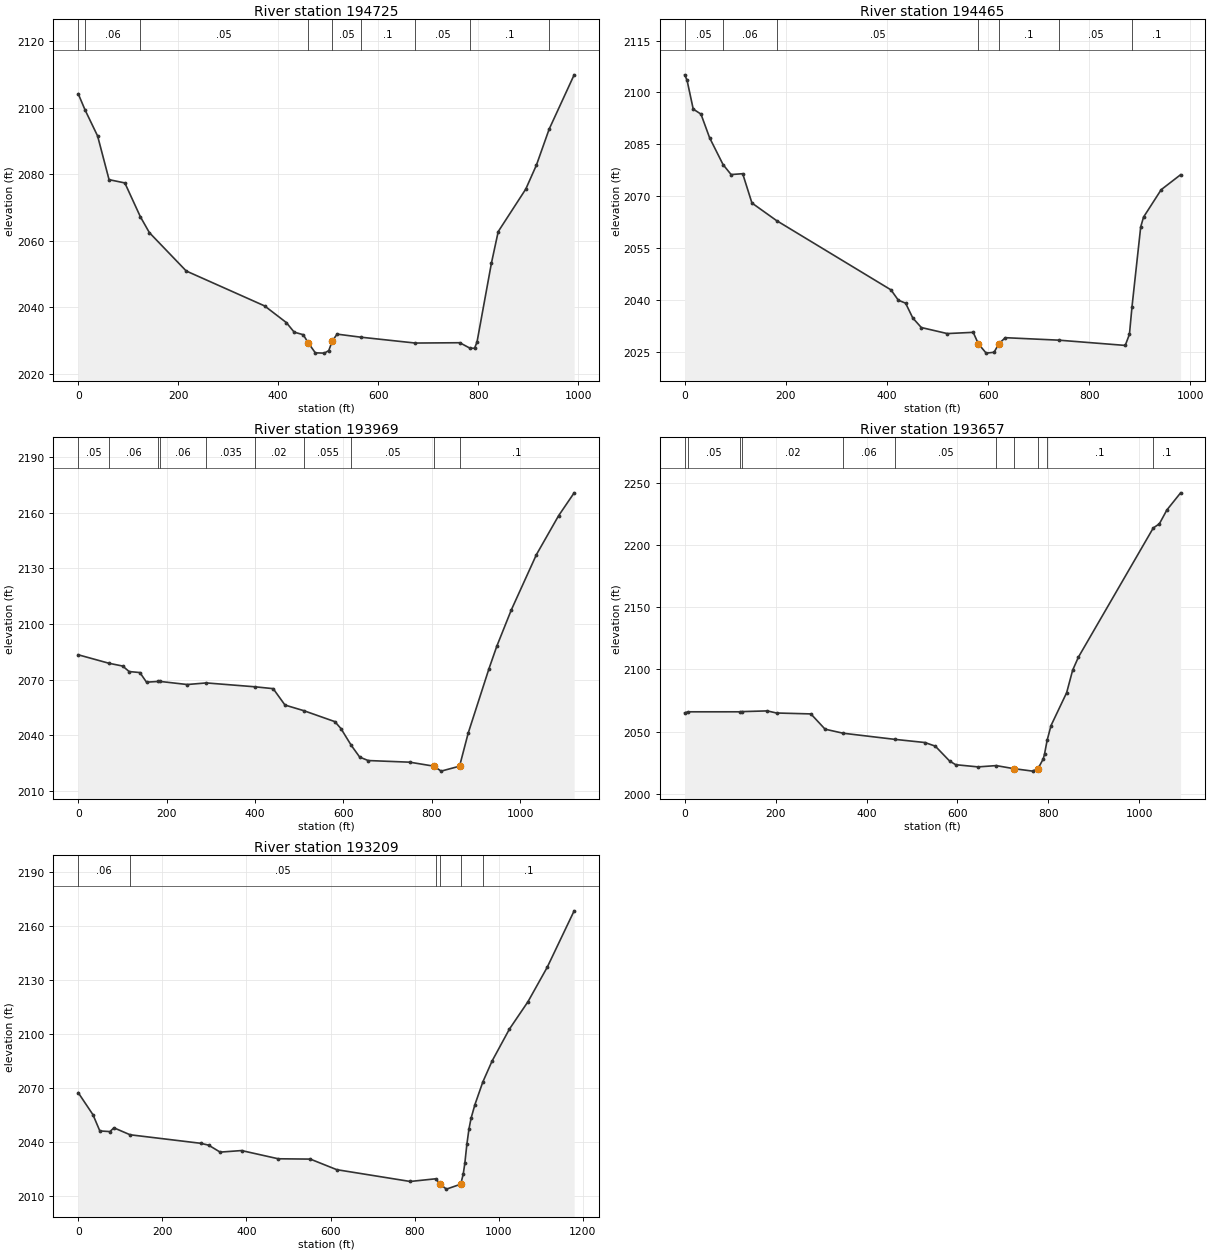
Type RM Length L Ch R = 1 ,194725  ,262.5,260.2,257.2
XS GIS Cut Line= 4
2439586.75457932532580.9747836822439875.80936237532375.023250754
2440276.87287387532104.034391639 2440327.4574609531959.507000111
#Sta/Elev= 30
       0 2104.24   13.622099.396    38.8 2091.53    61.7 2078.39    93.3  2077.4
  124.372067.214   142.4 2062.44   216.1  2050.9   372.9 2040.39   416.4 2035.37
     432  2032.5   450.2 2031.72   459.8 2029.35   474.3 2026.27   492.5 2026.18
   501.2 2026.95   508.1 2029.76   517.8  2031.9  564.852030.986  674.292029.214
   763.3 2029.31  783.732027.665   792.9 2027.65   797.8 2029.53   826.7 2053.34
   840.2 2062.76   895.3 2075.55   916.7  2082.8  942.062093.586   992.1 2109.94
#Mann= 9 ,-1 , 0
       0     .05       0   13.62     .06       0  124.37     .05       0
   459.8    .045       0   508.1     .05       0  564.85      .1       0
  674.29     .05       0  783.73      .1       0  942.06      .1       0
Bank Sta=459.8,508.1
XS Rating Curve= 0 ,0
Exp/Cntr(USF)=0,0
Exp/Cntr=0.3,0.1

Type RM Length L Ch R = 1 ,194465  ,486.6,495.6,500.7
XS GIS Cut Line= 4
2439662.63145987532797.7658709742440031.17630827532591.814338046
2440255.19376514532411.1550986362440406.94752624532187.137641768
#Sta/Elev= 30
       0 2105.09     4.7 2103.52    16.9 2095.17    32.2 2093.72    49.2  2086.9
   75.912079.099    91.8 2076.22   114.7 2076.47     133 2067.98  181.592062.903
   407.9 2042.84   422.5 2039.84   436.8    2039     451 2034.71   467.9 2031.94
   519.2 2030.19   570.5 2030.55  580.59 2027.25   596.1 2024.53   611.8 2024.78
   621.2 2027.25   633.9    2029  739.762028.282   871.1 2026.76   879.4 2029.98
  884.512038.022   901.7 2061.08   907.3 2063.91   942.2 2071.85   980.6 2076.18
#Mann= 7 ,-1 , 0
       0     .05       0   75.91     .06       0  181.59     .05       0
  580.59    .045       0   621.2      .1       0  739.76     .05       0
  884.51      .1       0
#XS Ineff= 2 , 0
          568.32 2030.27
Permanent Ineff=
       F       F
Bank Sta=580.59,621.2
XS Rating Curve= 0 ,0
Exp/Cntr(USF)=0,0
Exp/Cntr=0.3,0.1

Type RM Length L Ch R = 1 ,193969  ,313.4,311.7,308.4
XS GIS Cut Line= 4
 2439836.0643297533195.2161976762440258.80694992532902.548229832
2440598.44632001532689.3703273282440782.71874421532595.427522834
#Sta/Elev= 30
       0 2083.38   69.882078.775   100.6 2077.29   115.2 2074.32   139.5 2073.78
   154.5 2068.58   179.92068.952  184.91 2068.99   246.5 2067.31  289.922068.175
  399.95 2066.08   441.1 2065.08   467.8 2056.22  509.972053.214   580.6 2047.27
   594.4 2043.52  617.872034.403   636.9 2028.09     656 2026.25   750.2 2025.36
  804.772023.202   821.1 2020.53  862.762023.203   882.2    2041   929.1 2075.72
     947    2088   979.7 2107.54  1036.7 2137.51  1086.7 2158.46    1122 2170.86
#Mann= 10 ,-1 , 0
       0     .05       0   69.88     .06       0   179.9     .05       0
  184.91     .06       0  289.92    .035       0  399.95     .02       0
  509.97    .055       0  617.87     .05       0  804.77    .045       0
  862.76      .1       0
Bank Sta=804.77,862.76
XS Rating Curve= 0 ,0
Exp/Cntr(USF)=0,0
Exp/Cntr=0.3,0.1

Type RM Length L Ch R = 1 ,193657  ,449.2,447.9,448.1
XS GIS Cut Line= 4
2440132.34548234533426.460024121  2440479.211222533151.857980217
2440815.23740731532902.5482298322440985.05709235532747.181283939
#Sta/Elev= 30
       0 2065.01    7.182065.835  120.912065.845  125.91    2066   181.6 2066.57
     202 2064.89   277.6 2064.15   308.9 2051.88  348.362048.653  461.762043.739
   528.5 2041.17   551.3 2038.27   582.9 2026.28   596.2 2023.36   645.4  2021.6
  685.422022.638  723.522020.213   765.6  2018.2  777.332020.213   788.7 2027.94
   791.6 2031.85  797.252042.826   805.9 2054.79   840.3 2081.22   853.5  2099.3
   866.2 2109.78 1030.822213.485  1044.3 2216.87  1060.7 2227.91    1091 2241.72
#Mann= 11 ,-1 , 0
       0     .06       0    7.18     .05       0  120.91    .055       0
  125.91     .02       0  348.36     .06       0  461.76     .05       0
  685.42      .1       0  723.52    .045       0  777.33      .1       0
  797.25      .1       0 1030.82      .1       0
Bank Sta=723.52,777.33
XS Rating Curve= 0 ,0
Exp/Cntr(USF)=0,0
Exp/Cntr=0.3,0.1

Type RM Length L Ch R = 1 ,193209  ,275.2,285.1,296.5
XS GIS Cut Line= 4
2440323.84427611533780.5521333642440779.10555942533480.657795944
2441136.81085346533213.282121617 2441216.3009188533043.462436571
#Sta/Elev= 30
       0  2067.3    35.1 2055.05    51.4 2046.06    75.5  2045.7    84.9 2047.78
   123.42043.929   290.9 2039.21     310 2038.18   337.5 2034.31   388.4 2035.17
   475.7 2030.61   551.9 2030.43   614.9 2024.56   789.4 2018.02  850.172019.509
  860.812016.518   875.5 2013.77  909.642016.521   915.6 2022.22   919.3 2028.02
   924.2 2038.67   929.2 2047.16   934.2 2053.12   943.4 2060.71  962.212073.286
   984.2 2084.88  1025.3 2102.55  1069.5 2117.78  1115.3  2136.9  1179.3 2168.19
#Mann= 6 ,-1 , 0
       0     .06       0   123.4     .05       0  850.17      .1       0
  860.81    .045       0  909.64      .1       0  962.21      .1       0
Bank Sta=860.81,909.64
XS Rating Curve= 0 ,0
Exp/Cntr(USF)=0,0
Exp/Cntr=0.3,0.1