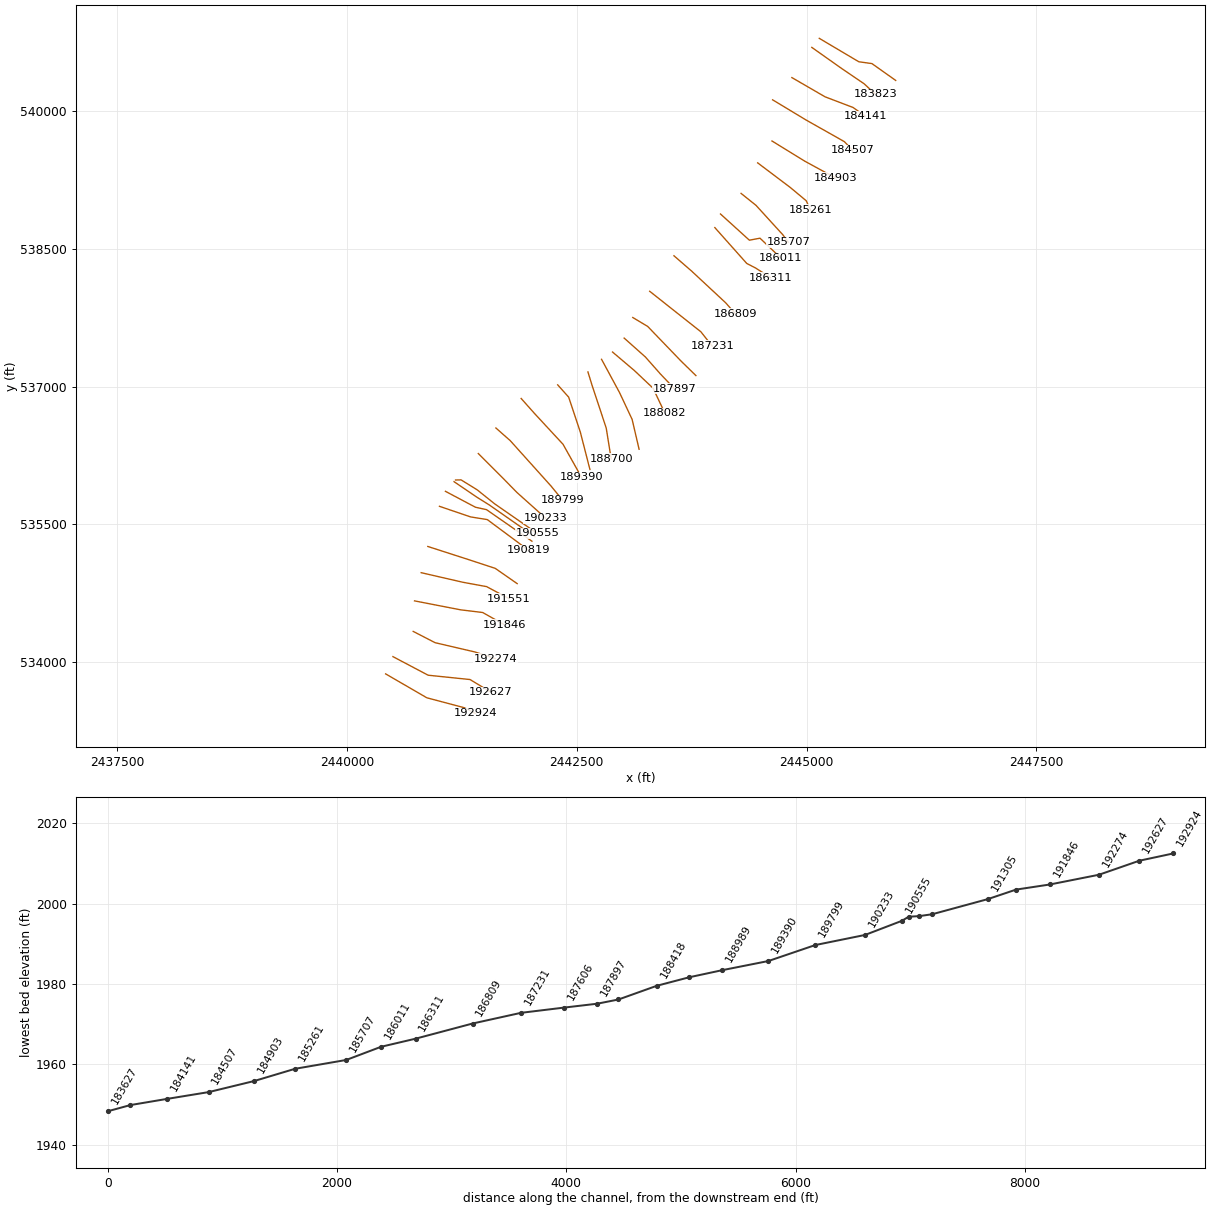
HEC-RAS study SFSBPOTOMC.prj: SFSBPOTOMC

--- SFSBPOTOMC.g01 (geometry) --- (continued)

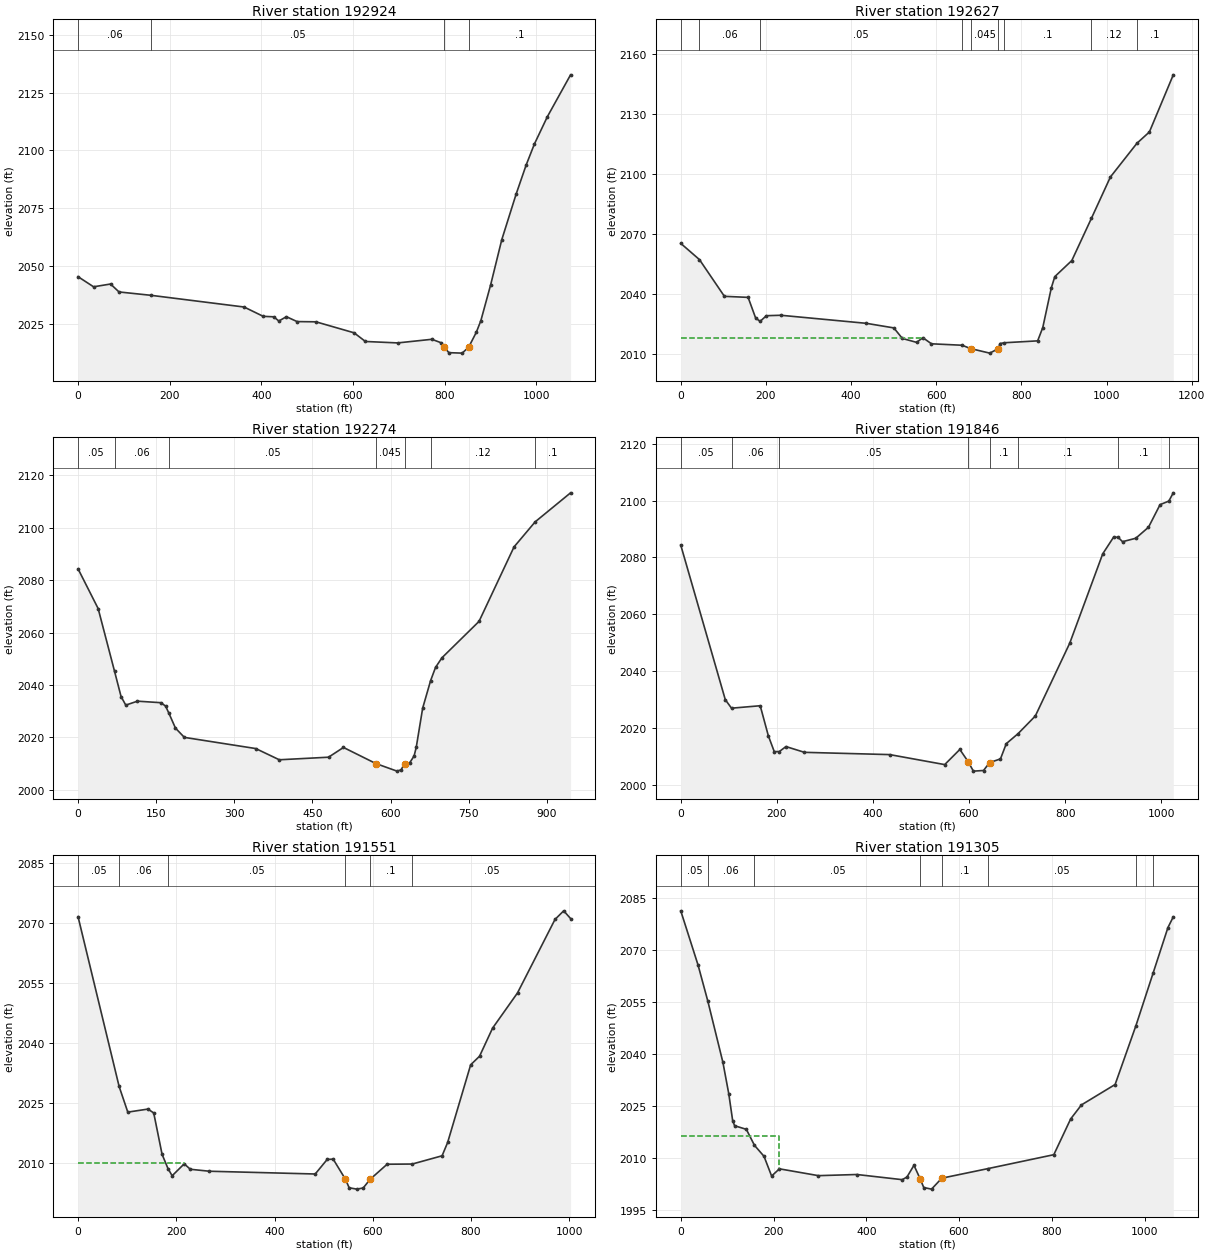
Type RM Length L Ch R = 1 ,192924  ,295.2,297.8,302.8
XS GIS Cut Line= 4
2440421.40026539533870.8817530692440869.43517913533610.732448319
 2441277.7250602533502.3369046732441396.96015821533440.912763273
#Sta/Elev= 30
       0 2045.48    33.9 2041.11    70.9 2042.31    89.4 2038.89   159.52037.426
   362.3 2032.38     404 2028.36   427.1 2028.15   438.1 2026.33   454.6  2028.2
   477.9 2026.09     519 2025.99   602.2 2021.25     627  2017.5   697.4 2016.88
   771.9 2018.44   792.6 2016.92  798.862015.042   809.1 2012.67   838.1 2012.47
  852.312015.041     869  2021.5   878.8 2026.45   900.2 2041.93   924.5 2061.45
   955.7 2081.06   977.7  2093.7   995.7 2102.77    1024 2114.57  1074.6 2132.64
#Mann= 4 ,-1 , 0
       0     .06       0   159.5     .05       0  798.86    .045       0
  852.31      .1       0
Bank Sta=798.86,852.31
XS Rating Curve= 0 ,0
Exp/Cntr(USF)=0,0
Exp/Cntr=0.3,0.1

Type RM Length L Ch R = 1 ,192627  ,356.1,352.5,347.4
XS GIS Cut Line= 4
2440500.89033073534058.7673620562440883.88791828533856.429013916
 2441339.1492016 533809.457611672441566.77984325533672.156589718
#Sta/Elev= 30
       0 2065.49   43.952057.374   102.5 2039.03   158.2 2038.51   175.9 2028.17
  186.512026.536   201.1 2029.35   235.1 2029.57     436 2025.54   500.4 2023.25
   520.5 2017.97   553.8 2016.04   568.7 2018.35   588.8 2015.31  660.652014.588
   681.12012.898   725.6 2010.65  746.09  2012.9   749.7 2015.44  760.132015.836
   838.2 2016.78   850.2 2023.43   870.3 2043.31   878.5 2048.89   918.4 2056.91
  964.282077.936    1009 2098.65 1071.312115.502  1100.6 2121.16  1156.7 2149.71
#Mann= 9 ,-1 , 0
       0     .05       0   43.95     .06       0  186.51     .05       0
  660.65      .1       0   681.1    .045       0  746.09      .1       0
  760.13      .1       0  964.28     .12       0 1071.31      .1       0
#XS Ineff= 2 , 0
          572.05 2018.01
Permanent Ineff=
       F       F
Bank Sta=681.1,746.09
XS Rating Curve= 0 ,0
Exp/Cntr(USF)=0,0
Exp/Cntr=0.3,0.1

Type RM Length L Ch R = 1 ,192274  ,424.6,428.1,431
XS GIS Cut Line= 4
2440721.29460281534333.3694059592440959.76479883 534210.52112316
2441393.34697342 534109.35194909 2441613.7512455534037.088253326
#Sta/Elev= 30
       0 2084.31    38.6 2069.16   70.122045.186    82.6 2035.59    91.6 2032.34
   114.1 2033.84   159.1 2033.26   168.1 2031.95  174.57 2029.17     187 2023.56
   204.1 2020.03   341.1 2015.77   386.3 2011.49   480.8 2012.47   509.5 2016.19
  571.562010.062   612.2 2007.16   620.1 2007.65  626.772010.061   636.9 2010.41
   645.1 2012.97   649.2 2016.27   661.5 2031.17  676.732041.668   686.2 2046.72
   698.5 2050.39   769.7 2064.27   836.9 2092.68  877.452102.236   945.4  2113.3
#Mann= 7 ,-1 , 0
       0     .05       0   70.12     .06       0  174.57     .05       0
  571.56    .045       0  626.77      .1       0  676.73     .12       0
  877.45      .1       0
Bank Sta=571.56,626.77
XS Rating Curve= 0 ,0
Exp/Cntr(USF)=0,0
Exp/Cntr=0.3,0.1

Type RM Length L Ch R = 1 ,191846  ,297.4,294.9,293.6
XS GIS Cut Line= 4
2440735.74734197534665.7824064742441237.98002753534568.226417192
2441476.45022355534539.3209388862441714.92041957534405.633101723
#Sta/Elev= 30
       0 2084.34    92.7 2029.91  105.662026.908   165.4 2027.77   182.3 2017.19
   194.6 2011.62  205.032011.618     219 2013.39   257.5 2011.36     435 2010.56
   549.4 2007.04   580.9 2012.37   598.1 2008.11   609.1 2004.74   630.2 2004.96
  642.872007.742   665.5 2009.05   677.6 2014.42  701.922017.906     738 2024.15
   809.7 2049.81   878.3 2081.26   900.8 2087.11  910.21 2087.12   919.6 2085.55
   947.1 2086.76   973.6 2090.64   997.7  2098.6 1015.952099.851  1025.2 2102.76
#Mann= 8 ,-1 , 0
       0     .05       0  105.66     .06       0  205.03     .05       0
   598.1    .045       0  642.87      .1       0  701.92      .1       0
  910.21      .1       0 1015.95      .1       0
#XS Ineff= 2 , 0
          223.56 2013.06
Permanent Ineff=
       F       F
Bank Sta=598.1,642.87
XS Rating Curve= 0 ,0
Exp/Cntr(USF)=0,0
Exp/Cntr=0.3,0.1

Type RM Length L Ch R = 1 ,191551  ,248.5,245.6,241.6
XS GIS Cut Line= 4
2440808.01103773534972.9031134712441263.27232104534868.120754613
2441519.80844101534821.1493523662441761.89182182534691.074699991
#Sta/Elev= 30
       0 2071.54   83.622029.126   101.3 2022.71   142.4 2023.47   154.1  2022.5
   171.1 2012.16  183.152008.603   191.6 2006.81   216.2 2009.79   228.6 2008.43
   267.5 2007.94   482.9 2007.25   507.3 2010.89   519.5 2010.96  544.382005.949
     552 2003.81   567.4 2003.47   580.5 2003.75  594.892005.948   629.3 2009.69
  680.392009.736   741.2  2011.8   752.5 2015.12   799.4 2034.53   817.5 2036.68
     844 2043.69   894.8  2052.5   971.1 2070.85   988.8    2073  1002.8 2071.08
#Mann= 6 ,-1 , 0
       0     .05       0   83.62     .06       0  183.15     .05       0
  544.38    .045       0  594.89      .1       0  680.39     .05       0
#XS Ineff= 2 , 0
          215.34 2010.04
Permanent Ineff=
       F       F
Bank Sta=544.38,594.89
XS Rating Curve= 0 ,0
Exp/Cntr(USF)=0,0
Exp/Cntr=0.3,0.1

Type RM Length L Ch R = 1 ,191305  ,481.3,486.2,490.3
XS GIS Cut Line= 4
2440880.27473349535258.3447117382441328.30964723 535113.81732021
 2441613.7512455535019.8745157172441852.22144152 534853.66801546
#Sta/Elev= 30
       0 2081.44    37.3 2065.79   58.462055.325    90.9 2037.69   103.5 2028.65
   111.9  2020.9   116.1 2019.41   141.4 2018.37  158.932013.754   179.5 2010.58
   195.9 2004.89   212.7 2006.97   296.8    2005   379.7 2005.33   477.5 2003.84
   487.7  2004.6   502.8 2007.99   516.2 2004.07   523.9 2001.57   540.7 2001.11
  562.772004.267  661.432007.006   804.3 2011.05   840.7 2021.38   863.9 2025.42
   936.5 2031.31  981.48 2048.34 1018.442063.481  1050.4 2076.62  1061.9  2079.7
#Mann= 8 ,-1 , 0
       0     .05       0   58.46     .06       0  158.93     .05       0
   516.2    .045       0  562.77      .1       0  661.43     .05       0
  981.48     .12       0 1018.44     .05       0
#XS Ineff= 2 , 0
          211.61 2016.55
Permanent Ineff=
       F       F
Bank Sta=516.2,562.77
XS Rating Curve= 0 ,0
Exp/Cntr(USF)=0,0
Exp/Cntr=0.3,0.1

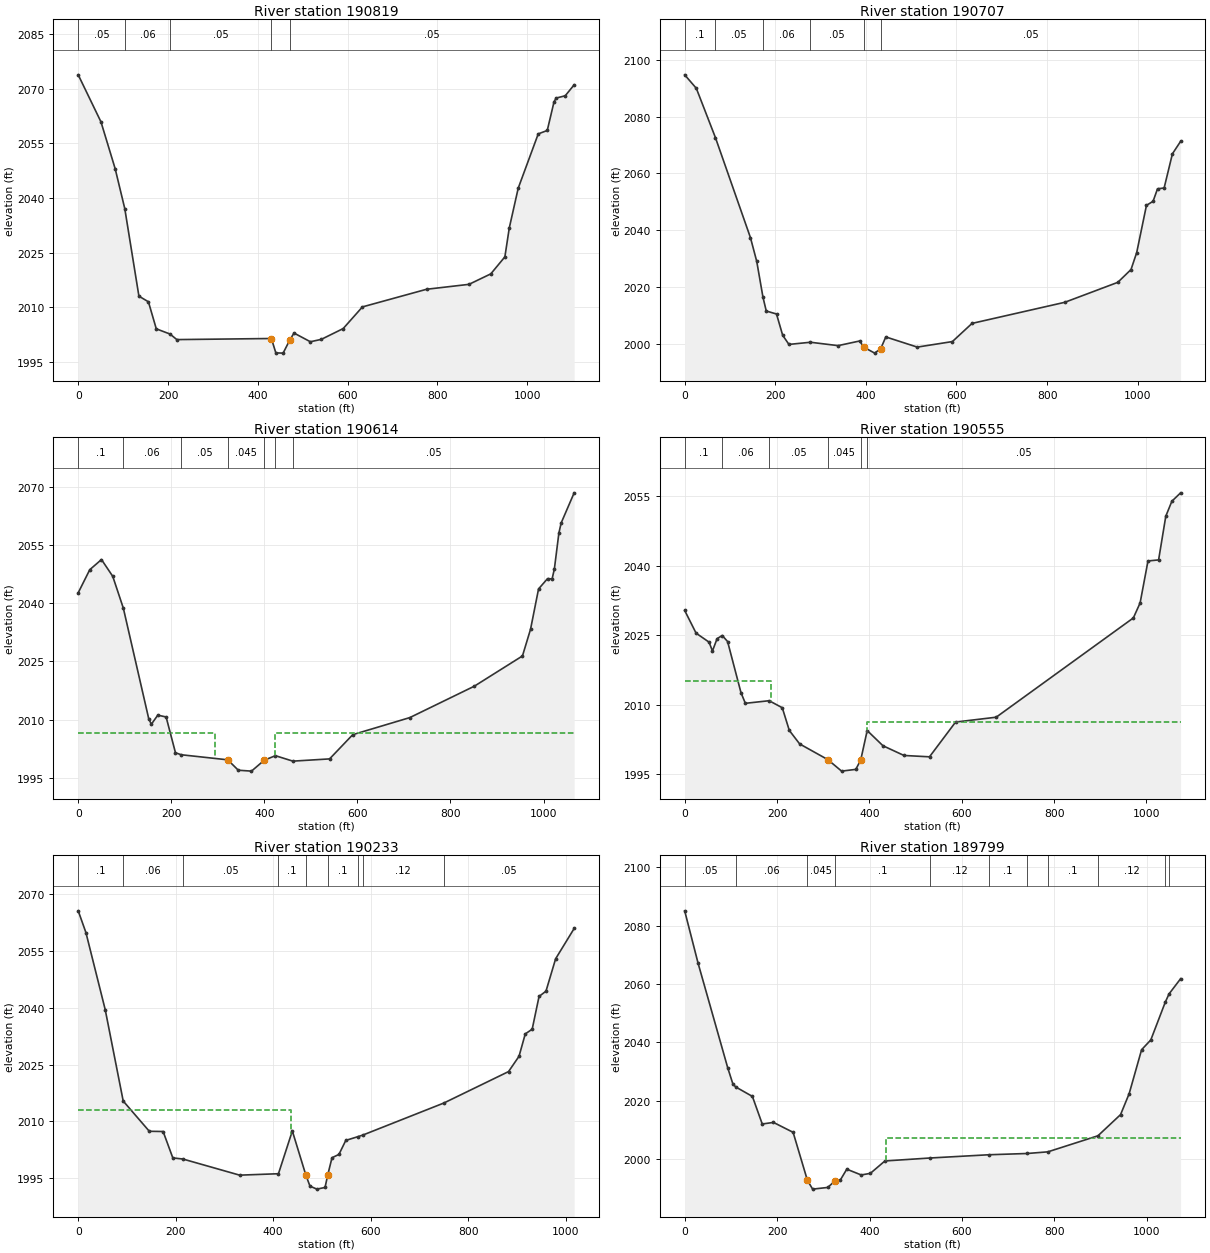
Type RM Length L Ch R = 1 ,190819  ,112.1,111.7,110.1
XS GIS Cut Line= 4
2441006.73620108535695.5400711112441346.37557117535579.918157888
2441527.03481058535551.0126795832441978.68290911 535214.98649428
#Sta/Elev= 30
       0 2073.86    50.7 2060.92    82.3 2048.05  103.712037.081   135.2 2013.01
   156.4 2011.45   173.9 2004.02  204.442002.593   219.7 2001.06   430.3 2001.36
   440.2 1997.41   456.4 1997.34   471.7 2001.04   480.7 2002.86   517.1 2000.47
   541.4 2001.12   590.2 2004.09   633.1 2010.05     776  2014.9   870.4 2016.25
     919 2019.13   950.4 2023.81   960.2 2031.76   980.1 2042.69  1024.7 2057.62
  1044.8 2058.56  1059.9 2066.45  1064.6 2067.47  1084.8  2068.1  1104.7 2071.11
#Mann= 5 ,-1 , 0
       0     .05       0  103.71     .06       0  204.44     .05       0
   430.3    .045       0   471.7     .05       0
Bank Sta=430.3,471.7
XS Rating Curve= 0 ,0
Exp/Cntr(USF)=0,0
Exp/Cntr=0.3,0.1

Type RM Length L Ch R = 1 ,190707  ,105.7,93.8,79.2
XS GIS Cut Line= 4
2441071.66609406535858.9160150892441398.92303854535685.304903984
2441518.71470517535659.2632373272442012.63831627535315.513237327
#Sta/Elev= 30
       0 2094.67    25.7 2089.93   67.922072.594   145.2 2037.46   159.1 2029.09
   172.82016.557   180.1 2011.68   202.7 2010.63   216.3 2003.17   230.1 1999.94
  277.672000.703   338.6 1999.51   386.6 2001.16   394.8 1999.01   419.5 1996.88
   432.9  1998.5     444 2002.57   513.4    1999     591 2000.94   634.4 2007.33
   839.1 2014.74   956.1 2021.75   985.3 2026.25   997.9 2032.23  1019.4  2048.8
    1034 2050.24  1043.8 2054.61  1058.4 2054.91  1076.7 2066.911094.814  2071.3
#Mann= 6 ,-1 , 0
       0      .1       0   67.92     .05       0   172.8     .06       0
  277.67     .05       0   394.8    .045       0   432.9     .05       0
Bank Sta=394.8,432.9
XS Rating Curve= 0 ,0
Exp/Cntr(USF)=0,0
Exp/Cntr=0.5,0.3

Type RM Length L Ch R = 1 ,190614  ,67.3,58.8,61.2
XS GIS Cut Line= 4
2441165.41609406535963.9507373122441415.41609409535793.811848432
 2441549.9647052535709.6104595362442045.62442738535363.256292865
#Sta/Elev= 30
       0 2042.65    24.8 2048.59      50 2051.21    74.2 2046.89   97.022038.666
   151.6 2010.19   157.2  2008.8     171 2011.13   188.9 2010.67     209 2001.46
  221.122000.942   321.3 1999.63   344.1 1996.95   372.4 1996.72   399.8 1999.53
  423.762000.697  461.351999.292   540.2 1999.87     590 2006.11   712.5  2010.5
   851.4  2018.6   954.7 2026.38   972.1 2033.26   989.3 2043.64  1008.6 2046.29
  1018.4 2046.21  1023.3 2048.78    1033 2058.03  1037.9 2060.631065.808 2068.39
#Mann= 7 ,-1 , 0
       0      .1       0   97.02     .06       0  221.12     .05       0
   321.3    .045       0   399.8     .05       0  423.76      .1       0
  461.35     .05       0
#XS Ineff= 2 , 0
           293.1 2006.59  421.91         2006.59
Permanent Ineff=
       F       F
Bank Sta=321.3,399.8
XS Rating Curve= 0 ,0
Exp/Cntr(USF)=0,0
Exp/Cntr=0.5,0.3

Type RM Length L Ch R = 1 ,190555  ,339.8,321.6,317.1
XS GIS Cut Line= 5
2441182.02520934535982.0452604362441242.18403602535983.413132773
2441416.58479976535875.4301992822441607.25637186535722.631292865
2442070.79803851535400.582681775
#Sta/Elev= 30
       02030.397  24.7262025.487  52.7332023.557  60.1742021.648  70.2442024.311
  81.3012024.985  92.9232023.687 121.9952012.628 131.4042010.345 182.9972010.906
 211.3832009.387 226.5812004.495 249.0212001.576 309.9031998.196  339.831995.704
 370.5861996.082 381.297 1998.11  395.272004.466 429.4172001.183 474.9461999.085
 530.2181998.794 586.6832006.296  674.622007.344 971.7282028.779  986.342032.015
1003.4042041.0781026.3962041.3061041.9882050.7451055.1352053.9761074.0752055.789
#Mann= 6 ,-1 , 0
       0      .1       0  81.301     .06       0 182.997     .05       0
 309.903    .045       0 381.297     .05       0  395.27     .05       0
#XS Ineff= 2 , 0
          187.95 2015.16   394.3         2006.29
Permanent Ineff=
       F       F
Bank Sta=309.903,381.297
XS Rating Curve= 0 ,0
Exp/Cntr(USF)=0,0
Exp/Cntr=0.5,0.3

Type RM Length L Ch R = 1 ,190233  ,437.5,433.8,426.1
XS GIS Cut Line= 4
 2441429.4788213536270.0364524352441693.24131084536006.273962896
2441848.60825673535847.2938322152442162.95533331535565.465418736
#Sta/Elev= 30
       0 2065.47    15.8 2059.75    55.4 2039.45   92.322015.384   145.9 2007.42
   174.2 2007.36   194.1 2000.41  214.752000.117   331.2 1995.87  410.821996.245
   439.3 2007.51   467.2 1995.82   475.5 1992.98   489.6 1992.19   506.4 1992.63
  512.061995.986   520.7 2000.46   534.9 2001.33     549 2005.02  573.522005.991
  583.832006.419  750.192014.863   882.9 2023.14   904.4 2027.17   917.2 2033.06
   931.4  2034.3   945.5 2042.93   959.7 2044.31   979.5 2052.85  1017.5 2060.82
#Mann= 9 ,-1 , 0
       0      .1       0   92.32     .06       0  214.75     .05       0
  410.82      .1       0   467.2    .045       0  512.06      .1       0
  573.52      .1       0  583.83     .12       0  750.19     .05       0
#XS Ineff= 2 , 0
          436.36 2013.04
Permanent Ineff=
       F       F
Bank Sta=467.2,512.06
XS Rating Curve= 0 ,0
Exp/Cntr(USF)=0,0
Exp/Cntr=0.3,0.1

Type RM Length L Ch R = 1 ,189799  ,405.9,409.1,412.4
XS GIS Cut Line= 4
2441620.97761508536548.2516811262441776.34456097536410.950659174
2442220.76628992535915.944343191 2442347.2277575535760.577397298
#Sta/Elev= 30
       0 2085.13      29 2067.16    93.1 2031.31   104.2 2025.79  110.322024.728
   146.5 2021.48   167.8 2012.02   192.1 2012.56   234.6 2009.16  265.441992.727
   276.8 1989.68   309.6 1990.26   325.2 1992.52   336.7  1992.8   350.7 1996.52
   381.9 1994.54   401.7 1995.09   433.2 1999.34  530.552000.354  658.122001.469
  741.162001.902  785.69 2002.47  894.052007.975     943 2015.24   961.6 2022.43
   988.5  2037.5  1008.4 2040.85 1039.722053.802 1047.862056.634  1072.9 2061.85
#Mann= 11 ,-1 , 0
       0     .05       0  110.32     .06       0  265.44    .045       0
   325.2      .1       0  530.55     .12       0  658.12      .1       0
  741.16     .12       0  785.69      .1       0  894.05     .12       0
 1039.72      .1       0 1047.86      .1       0
#XS Ineff= 2 , 0
                          436.36          2007.1
Permanent Ineff=
       F       F
Bank Sta=265.44,325.2
XS Rating Curve= 0 ,0
Exp/Cntr(USF)=0,0
Exp/Cntr=0.3,0.1

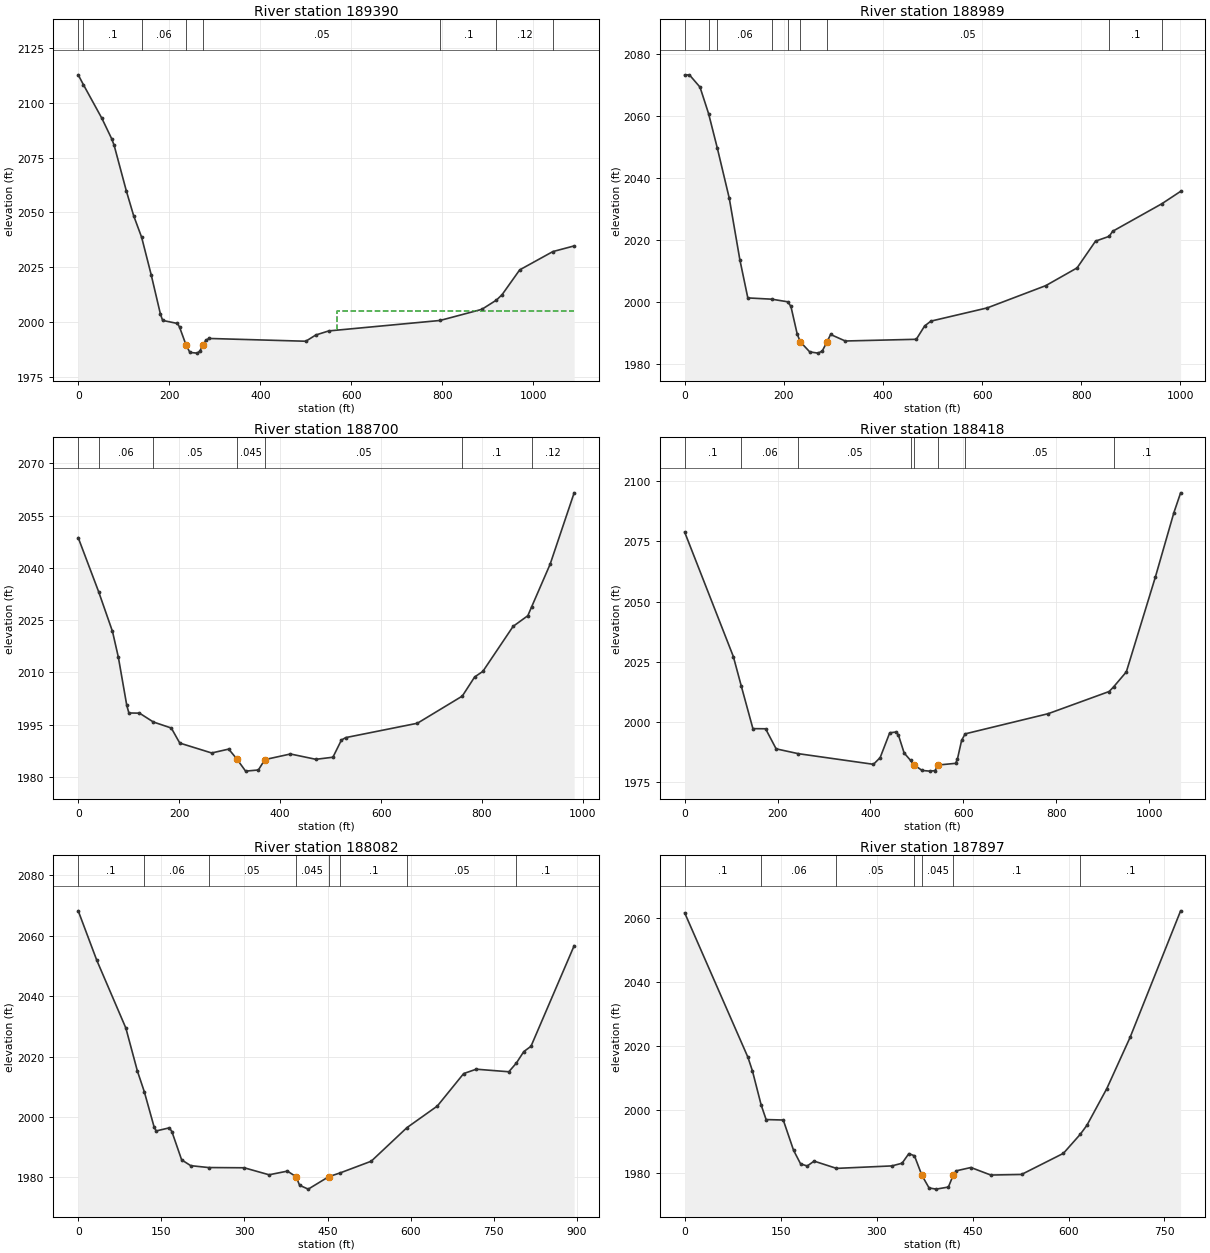
Type RM Length L Ch R = 1 ,189390  ,410.2,401.4,391.8
XS GIS Cut Line= 4
2441895.57965898536869.8251272762442040.10705051536707.231811807
2442350.84094229536371.2056265042442553.17929043536009.887147684
#Sta/Elev= 30
       0 2112.83   11.292108.378    52.1 2092.91    73.5 2083.63    78.9 2080.63
   105.6 2059.88   121.7 2048.53  139.372038.582   160.2 2021.57   180.5 2003.62
   185.4 2000.65     218 1999.26   222.5 1997.64  236.511989.622   245.2 1986.02
   261.6 1985.71     267 1986.62  274.781989.624   280.3 1991.63   287.6 1992.41
   499.9 1991.14   521.9    1994   550.3 1995.85  794.772000.628   886.5 2005.71
  918.662009.941   931.1 2012.44   969.7 2023.74 1042.552032.095  1089.3 2034.68
#Mann= 8 ,-1 , 0
       0     .05       0   11.29      .1       0  139.37     .06       0
  236.51    .045       0  274.78     .05       0  794.77      .1       0
  918.66     .12       0 1042.55      .1       0
#XS Ineff= 2 , 0
                          569.11         2004.84
Permanent Ineff=
       F       F
Bank Sta=236.51,274.78
XS Rating Curve= 0 ,0
Exp/Cntr(USF)=0,0
Exp/Cntr=0.3,0.1

Type RM Length L Ch R = 1 ,188989  ,289.5,289.1,289.9
XS GIS Cut Line= 4
2442293.02998568537017.9657035922442412.26508369536884.277866429
2442538.72655128536504.8934636682442643.50891014536096.603582601
#Sta/Elev= 30
       0  2073.3     9.5 2073.36    30.9 2069.39   48.182060.855   65.552049.876
    89.9 2033.54   111.3 2013.64   127.4 2001.28  176.092000.864  207.682000.028
   214.3 1998.57     227 1989.62  233.261987.102   252.3 1983.84   269.1 1983.44
   277.6 1984.13  287.251987.102   294.4 1989.47     324 1987.36   467.3 1987.91
   484.2 1992.23   496.8 1993.78   610.3 1998.05   728.6 2005.25   791.7 2010.98
   828.9 2019.62  856.572021.186   863.3 2022.79  962.692031.704  1000.6 2035.71
#Mann= 9 ,-1 , 0
       0      .1       0   48.18      .1       0   65.55     .06       0
  176.09    .055       0  207.68     .05       0  233.26    .045       0
  287.25     .05       0  856.57      .1       0  962.69     .12       0
Bank Sta=233.26,287.25
XS Rating Curve= 0 ,0
Exp/Cntr(USF)=0,0
Exp/Cntr=0.3,0.1

Type RM Length L Ch R = 1 ,188700  ,284.3,282.2,290
XS GIS Cut Line= 4
2442621.82980141537158.8799103322442665.18801887537017.965703592
2442820.55496476536548.2516811262442874.75273658536212.225495823
#Sta/Elev= 30
       0 2048.67   40.372033.195    67.9 2021.76    79.5 2014.38    96.2 2000.54
   100.4 1998.36   121.4 1998.31  148.831995.774   184.4 1994.04   201.2 1989.72
   264.4 1986.88   298.1 1987.99  313.691985.266   331.6 1981.67   356.9    1982
   369.8 1984.98   420.5 1986.59   470.8 1985.06   504.6 1985.66   521.4 1990.58
   529.9 1991.29   671.9 1995.41  760.872003.204   785.4  2008.7   801.6 2010.29
   861.6 2023.22   890.7 2026.27  898.322028.838   934.9 2041.05   982.5 2061.54
#Mann= 7 ,-1 , 0
       0      .1       0   40.37     .06       0  148.83     .05       0
  313.69    .045       0   369.8     .05       0  760.87      .1       0
  898.32     .12       0
Bank Sta=313.69,369.8
XS Rating Curve= 0 ,0
Exp/Cntr(USF)=0,0
Exp/Cntr=0.3,0.1

Type RM Length L Ch R = 1 ,188418  ,330.7,335.6,349.9
XS GIS Cut Line= 4
2442769.97037772537296.1809322842442965.08235629536934.862453463
2443102.38337824536642.1944856192443178.26025879536317.007854681
#Sta/Elev= 30
       0 2078.87   104.8 2027.17  122.022014.816   146.9 1997.22   174.2 1997.16
   196.9 1988.82  244.451986.822   406.5 1982.39   420.9 1985.19   441.5  1995.5
   454.8  1995.8     460 1994.68   472.5 1987.11  486.211984.047   493.1 1982.27
   511.1 1979.84   527.6 1979.56   538.7 1979.75   546.4  1982.1   583.3  1982.8
   587.3 1984.62   596.2 1992.29  603.791995.043   782.5 2003.42   913.9 2012.65
  923.842014.648   950.9  2020.8  1013.4  2060.2  1053.3 2086.98  1067.8 2095.22
#Mann= 8 ,-1 , 0
       0      .1       0  122.02     .06       0  244.45     .05       0
  486.21      .1       0   493.1    .045       0   546.4      .1       0
  603.79     .05       0  923.84      .1       0
Bank Sta=493.1,546.4
XS Rating Curve= 0 ,0
Exp/Cntr(USF)=0,0
Exp/Cntr=0.3,0.1

Type RM Length L Ch R = 1 ,188082  ,188.6,185.4,186.3
XS GIS Cut Line= 4
2442889.20547573537375.6709976242443127.67567175537173.332649485
2443330.01401989 536981.833855712443460.08867227536707.231811807
#Sta/Elev= 30
       0 2068.29    33.5 2051.92      86 2029.47   106.9 2015.19  119.232008.438
   137.2 1996.59   140.7  1995.4   164.6 1996.44   169.1 1995.18   186.7 1985.83
   203.1 1983.91  235.221983.288   299.6 1983.21   344.5 1980.89   377.6  1982.1
  393.261980.264   399.6 1977.41   415.2 1976.14  452.271980.266  472.68  1981.5
   528.9 1985.38  593.441996.508   648.2 2003.65   695.8 2014.41   718.5 2015.85
   777.3    2015   790.92017.892   804.3 2021.68   817.3 2023.44   895.2 2056.74
#Mann= 8 ,-1 , 0
       0      .1       0  119.23     .06       0  235.22     .05       0
  393.26    .045       0  452.27     .05       0  472.68      .1       0
  593.44     .05       0   790.9      .1       0
Bank Sta=393.26,452.27
XS Rating Curve= 0 ,0
Exp/Cntr(USF)=0,0
Exp/Cntr=0.3,0.1

Type RM Length L Ch R = 1 ,187897  ,289.8,290.9,293.1
XS GIS Cut Line= 4
2443015.66694332537527.4247587282443246.91076977537321.473225801
2443409.50408523537137.2008016032443561.25784634536978.220670922
#Sta/Elev= 30
       0  2061.6    98.9 2016.36   105.9 2012.11  119.572001.424   127.3 1996.87
   154.1 1996.73   170.2 1987.25   181.2 1982.99   191.6 1982.34   202.3 1983.86
   237.31981.586   323.8 1982.36   339.8  1983.2   350.4 1986.21  359.171985.523
  370.771979.422     382 1975.46   393.1 1975.09   412.2 1975.74   419.8 1979.47
   424.7 1980.83   447.4 1981.86   478.5  1979.5   526.5 1979.68     592  1986.3
  618.251992.236   628.7 1995.07   659.8 2006.56   696.2  2022.6   775.2 2062.23
#Mann= 7 ,-1 , 0
       0      .1       0  119.57     .06       0   237.3     .05       0
  359.17      .1       0  370.77    .045       0   419.8      .1       0
  618.25      .1       0
Bank Sta=370.77,419.8
XS Rating Curve= 0 ,0
Exp/Cntr(USF)=0,0
Exp/Cntr=0.3,0.1

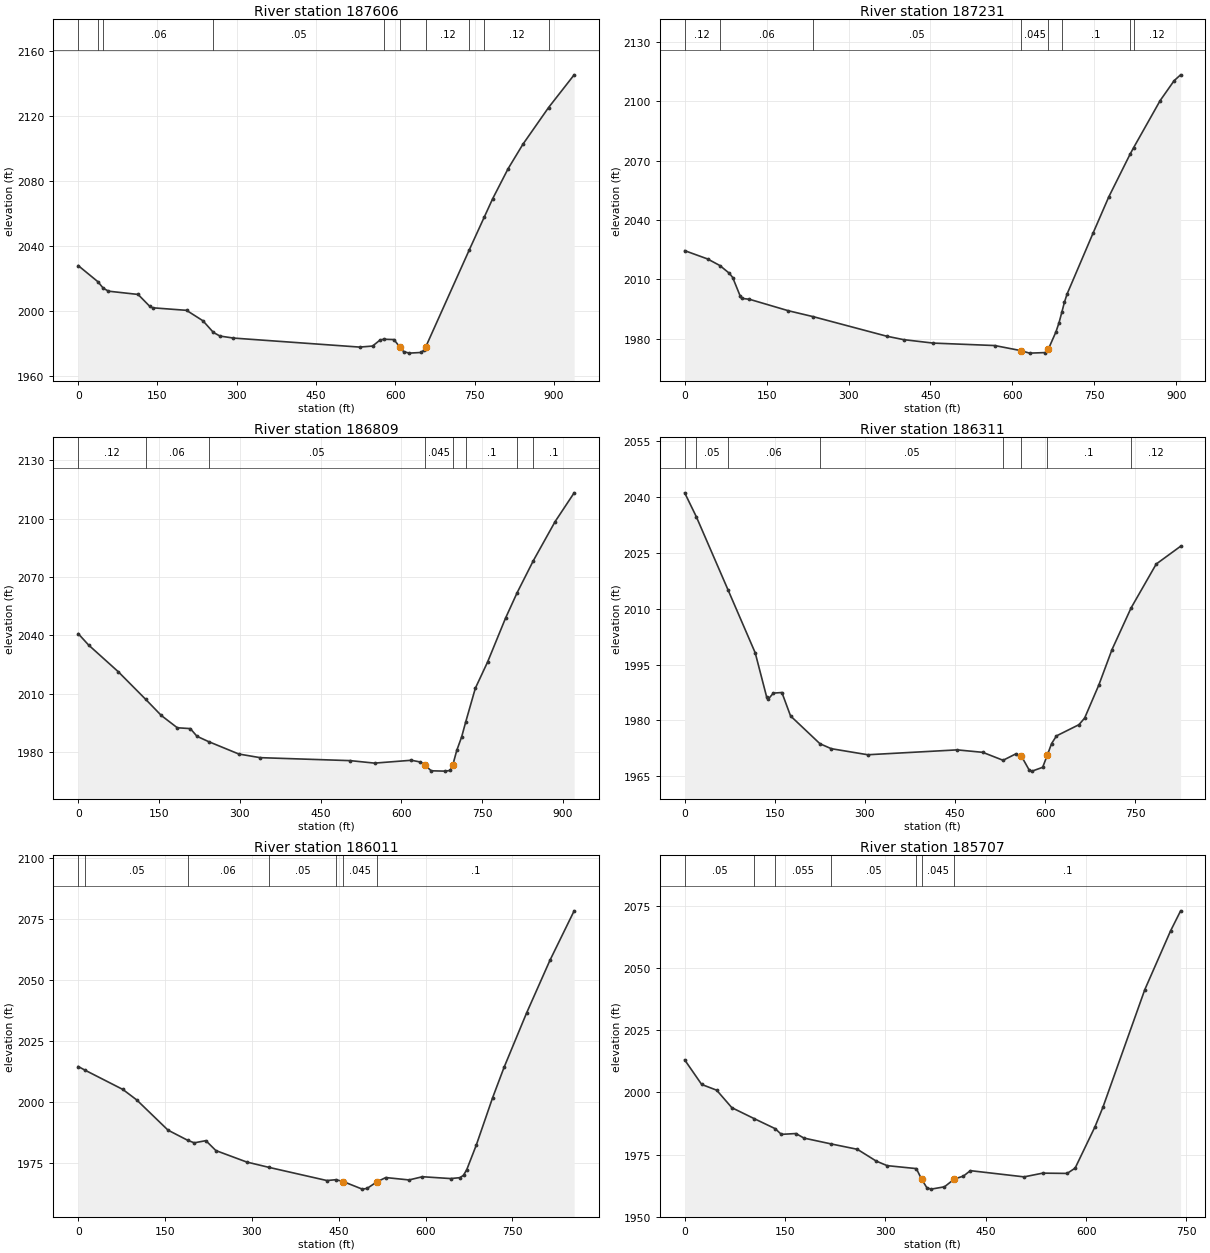
Type RM Length L Ch R = 1 ,187606  ,370.4,374.4,377.7
XS GIS Cut Line= 4
2443109.60974781537751.4422155972443272.20306328537653.886226316
 2443633.5215421537278.1150083432443796.11485757537119.134877662
#Sta/Elev= 30
       0    2028   37.252018.076   47.37 2014.09    57.3 2012.25   113.3 2010.24
   135.3 2002.93     141 2002.02   204.9 2000.46     236 1994.03  255.831986.833
   268.3 1984.62   293.7 1983.39   532.3 1977.84   556.9 1978.47   571.1 1982.19
  577.741982.665   597.3 1982.47   608.8 1977.74   615.5  1975.1   626.1 1974.12
     649 1974.53   654.7 1976.03  657.531977.975  739.892037.684  768.372057.961
   784.2 2069.21   813.3 2087.61   841.3 2102.66  889.832125.249   938.3 2145.41
#Mann= 10 ,-1 , 0
       0     .12       0   37.25      .1       0   47.37     .06       0
  255.83     .05       0  577.74      .1       0   608.8    .045       0
  657.53     .12       0  739.89      .1       0  768.37     .12       0
  889.83      .1       0
Bank Sta=608.8,657.53
XS Rating Curve= 0 ,0
Exp/Cntr(USF)=0,0
Exp/Cntr=0.3,0.1

Type RM Length L Ch R = 1 ,187231  ,425,422.8,420.3
XS GIS Cut Line= 4
2443293.88217201538036.8838138652443521.51281367537856.224574455
 2443850.3126294537596.0752697042443973.16091219537440.708323812
#Sta/Elev= 30
       0 2024.57      42 2020.37   64.372017.059    81.8 2013.13    87.9    2011
   101.7 2001.59   104.5 2000.47   118.6 2000.01     190 1994.21  235.751991.205
   370.1 1981.35   400.6 1979.64   454.7 1977.89   567.6 1976.65   615.1 1974.11
   631.3 1972.82   659.8 1973.09   665.5 1974.67   679.6 1983.51   685.4 1988.26
  690.641993.681   695.1 1998.45   700.2 2002.77     748 2033.67   776.5 2051.79
  815.372073.265  821.722076.512   870.5 2100.38   896.1 2110.43   907.9 2113.35
#Mann= 8 ,-1 , 0
       0     .12       0   64.37     .06       0  235.75     .05       0
   615.1    .045       0   665.5      .1       0  690.64      .1       0
  815.37      .1       0  821.72     .12       0
Bank Sta=615.1,665.5
XS Rating Curve= 0 ,0
Exp/Cntr(USF)=0,0
Exp/Cntr=0.3,0.1

Type RM Length L Ch R = 1 ,186809  ,489.9,497.2,502.3
XS GIS Cut Line= 4
2443557.64466155538423.4945862022443749.14345533538257.288085945
2444121.30148851537910.4223462782444226.08384737537791.187248267
#Sta/Elev= 30
       0 2040.86    19.2 2035.03    74.2 2021.33  125.332007.071   154.3 1998.78
     184 1992.46   208.2 1992.03   220.6 1988.07  242.121985.339   298.2 1978.96
   337.8 1977.09   505.5 1975.55   550.4 1974.28   618.7 1975.75   635.6 1974.84
  643.341973.421   655.5 1970.33   680.9 1970.16   691.2  1970.5  695.741973.424
     703 1980.82   712.1 1987.78  719.79 1995.62   737.5 2012.79   760.2 2026.25
   793.6 2048.86   815.12061.916  845.192078.385   885.7 2098.51     921 2113.28
#Mann= 8 ,-1 , 0
       0     .12       0  125.33     .06       0  242.12     .05       0
  643.34    .045       0  695.74      .1       0  719.79      .1       0
   815.1      .1       0  845.19      .1       0
Bank Sta=643.34,695.74
XS Rating Curve= 0 ,0
Exp/Cntr(USF)=0,0
Exp/Cntr=0.3,0.1

Type RM Length L Ch R = 1 ,186311  ,282.4,300.4,319.7
XS GIS Cut Line= 4
 2444002.0663905538730.6152931992444348.93213017538340.391336074
2444446.48811945538289.8067490392444609.08143492538185.024390181
#Sta/Elev= 30
       0 2041.16   19.35 2034.75   71.962015.159   117.4 1998.17   136.3  1986.4
   139.1 1985.73   147.6 1987.35   161.8 1987.51   176.2 1981.22  225.161973.748
     244 1972.42   304.7 1970.79   453.6  1972.1   496.1 1971.44  529.911969.304
   551.2 1971.03   560.1 1970.51   573.7 1966.59   578.2 1966.39   595.8 1967.42
  603.511970.665   610.6 1973.78   618.8 1975.86   656.1 1978.86   665.6 1980.63
   689.3 1989.54   711.2 1999.05  742.922010.224   784.8 2022.03   825.4 2026.81
#Mann= 8 ,-1 , 0
       0      .1       0   19.35     .05       0   71.96     .06       0
  225.16     .05       0  529.91      .1       0   560.1    .045       0
  603.51      .1       0  742.92     .12       0
Bank Sta=560.1,603.51
XS Rating Curve= 0 ,0
Exp/Cntr(USF)=0,0
Exp/Cntr=0.3,0.1

Type RM Length L Ch R = 1 ,186011  ,331.4,304.3,268.1
XS GIS Cut Line= 4
 2444063.4905319538878.7558695162444377.83760847538593.314271248
 2444493.4595217538614.9933799772444721.09016335538398.202292685
#Sta/Elev= 30
       0 2014.54   11.932013.021    77.2 2005.14     101 2000.88   155.1 1988.51
  189.041984.364   200.4 1983.32   220.5 1984.21   237.8 1980.15     291 1975.47
  329.251973.293   429.6 1967.89   445.21968.239  457.861967.461   490.6 1964.38
   498.9 1964.67  516.651967.461   531.3 1969.11   571.4 1968.14   594.6 1969.45
   643.4  1968.7   659.2 1969.07   665.5 1970.05   671.1 1972.35   687.5 1982.35
   715.8 2001.79   735.6 2014.23   774.4 2036.41   814.8 2057.99   856.6 2078.22
#Mann= 7 ,-1 , 0
       0      .1       0   11.93     .05       0  189.04     .06       0
  329.25     .05       0   445.2      .1       0  457.86    .045       0
  516.65      .1       0
Bank Sta=457.86,516.65
XS Rating Curve= 0 ,0
Exp/Cntr(USF)=0,0
Exp/Cntr=0.3,0.1

Type RM Length L Ch R = 1 ,185707  ,443.4,445.8,449.1
XS GIS Cut Line= 4
2444287.50798877539102.7733263842444450.10130424538972.698674009
2444742.76927208538651.1252278592444800.58022869538571.635162519
#Sta/Elev= 30
       0 2013.09    25.4  2003.2    47.8  2000.9    70.5 1993.86  104.231989.414
  135.221985.427   144.5 1983.13   166.3 1983.46   178.3 1981.63  219.421979.249
   258.1 1977.12   286.4 1972.37   302.6 1970.55  346.291969.357  354.011965.169
   362.1 1961.61   368.5  1961.1   388.3 1962.03  403.091965.166   416.7 1966.35
     427 1968.53   507.3 1966.03   535.2 1967.53   571.7 1967.42   583.6 1969.54
   613.3 1986.18   625.2 1994.07   687.8 2041.37   726.2 2064.93   741.3 2073.04
#Mann= 7 ,-1 , 0
       0     .05       0  104.23     .06       0  135.22    .055       0
  219.42     .05       0  346.29      .1       0  354.01    .045       0
  403.09      .1       0
Bank Sta=354.01,403.09
XS Rating Curve= 0 ,0
Exp/Cntr(USF)=0,0
Exp/Cntr=0.3,0.1

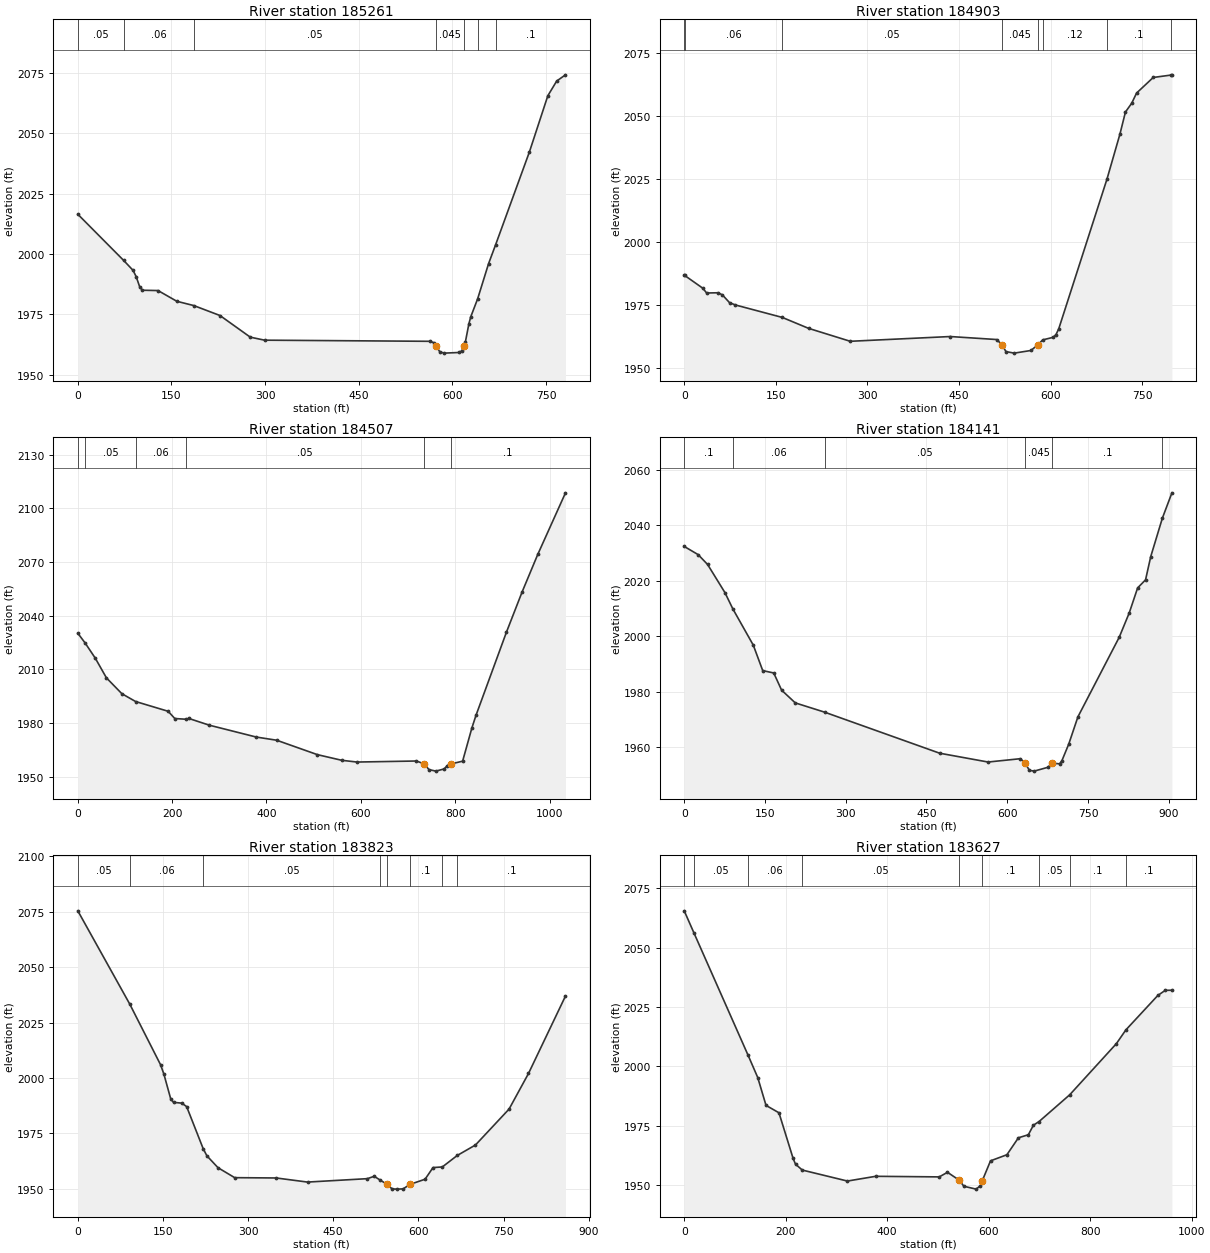
Type RM Length L Ch R = 1 ,185261  ,353.2,357.6,361.9
XS GIS Cut Line= 4
2444468.16722818539435.1863268992444822.25933742539167.810652572
2444995.69220725539023.283261044 2445042.6636095538922.114086974
#Sta/Elev= 30
       0 2016.49   73.471997.326    88.4 1993.25    93.4 1990.67    99.1 1986.42
   103.5 1984.98   128.5 1984.85   158.6  1980.4  185.791978.622   227.7  1974.5
   276.2 1965.53   299.1 1964.28   563.9 1963.81   570.1 1963.26  574.311961.739
   579.7 1959.45   586.7 1958.91     611 1959.18   615.1 1959.93  618.431961.738
   620.8 1963.71   626.3 1971.07   629.3 1973.98  640.291981.403   657.8 1995.99
  669.242003.938   723.3 2042.38   752.7  2065.6   766.9  2071.7     781 2074.28
#Mann= 7 ,-1 , 0
       0     .05       0   73.47     .06       0  185.79     .05       0
  574.31    .045       0  618.43     .05       0  640.29      .1       0
  669.24      .1       0
Bank Sta=574.31,618.43
XS Rating Curve= 0 ,0
Exp/Cntr(USF)=0,0
Exp/Cntr=0.3,0.1

Type RM Length L Ch R = 1 ,184903  ,396.8,396.6,395.9
XS GIS Cut Line= 4
2444623.53417407 539673.65652292 2444981.2394681 539453.25225084
2445179.96463145539344.8567071942445313.65246862 539272.59301143
#Sta/Elev= 30
       0 1986.89     .711986.713    30.5 1981.62    36.7 1979.74    55.5 1979.83
    62.5 1978.99    74.2  1975.9    83.6    1975  160.551970.037   203.5 1965.71
   271.8 1960.56   435.5 1962.45   511.5 1961.26  520.421959.204   526.7 1956.47
   540.3 1955.86   567.7 1956.91  579.121959.204  586.931961.119   604.1 1962.14
   608.7 1963.23   613.2 1965.52  692.162024.963   713.3 2042.76   722.4 2051.61
   732.7 2055.11   740.6 2059.13   767.9 2065.33  797.322066.296   798.5 2066.38
#Mann= 8 ,-1 , 0
       0     .05       0     .71     .06       0  160.55     .05       0
  520.42    .045       0  579.12     .05       0  586.93     .12       0
  692.16      .1       0  797.32     .12       0
Bank Sta=520.42,579.12
XS Rating Curve= 0 ,0
Exp/Cntr(USF)=0,0
Exp/Cntr=0.3,0.1

Type RM Length L Ch R = 1 ,184507  ,361.3,365.3,370.2
XS GIS Cut Line= 4
2444630.76054365540121.6914366572444995.69220725539901.287164577
 2445411.2084579539666.430153343 2445501.5380776 539572.48734885
#Sta/Elev= 30
       0 2030.23   15.472024.795      37  2016.3    60.7 2005.26    93.4 1996.41
  122.521992.035   191.6 1986.57   205.6 1982.53  229.581982.121   235.1 1982.59
   278.8  1978.8   378.5 1972.16   421.6 1970.39   507.9 1962.33   559.5 1959.17
   591.8 1958.19     718 1958.77  734.661957.126   744.4 1953.98   759.1 1953.11
   776.7 1954.34   783.6 1956.25   791.11957.127   815.8 1958.68   835.4 1977.21
   844.2 1984.34   908.7 2030.81   941.8 2053.23   975.1 2074.29  1033.9 2108.74
#Mann= 6 ,-1 , 0
       0      .1       0   15.47     .05       0  122.52     .06       0
  229.58     .05       0  734.66    .045       0   791.1      .1       0
Bank Sta=734.66,791.1
XS Rating Curve= 0 ,0
Exp/Cntr(USF)=0,0
Exp/Cntr=0.3,0.1

Type RM Length L Ch R = 1 ,184141  ,322.1,318.6,311.6
XS GIS Cut Line= 4
2444840.32526136540363.7748174662445201.64374018540154.210099751
2445505.15126239540038.5881865282445638.83909955539944.645382035
#Sta/Elev= 30
       0 2032.43    25.9 2029.47    43.4 2025.93    75.6 2015.79   90.39 2009.88
   128.3 1996.83   145.8 1987.66   166.3  1986.8   180.9  1980.6   206.3 1976.01
  260.661972.679   474.5 1957.87   564.4 1954.69   624.3 1955.89   632.9 1954.39
   641.2  1951.7     650 1951.41   675.7  1952.8   683.5 1954.29   697.1 1954.04
   701.4 1955.11   714.2 1961.13   731.3 1970.99     808 1999.68   826.7  2008.5
   842.2 2017.48   856.9 2020.38   866.6  2028.8  888.212042.655   905.9 2051.76
#Mann= 6 ,-1 , 0
       0      .1       0   90.39     .06       0  260.66     .05       0
   632.9    .045       0   683.5      .1       0  888.21     .12       0
Bank Sta=632.9,683.5
XS Rating Curve= 0 ,0
Exp/Cntr(USF)=0,0
Exp/Cntr=0.3,0.1

Type RM Length L Ch R = 1 ,183823  ,182.9,195.6,205.8
XS GIS Cut Line= 4
2445057.11634865540692.574633193 2445378.6897948540464.943991536
2445627.99954519 540295.12430649 2445747.2346432540183.115578056
#Sta/Elev= 30
       0 2075.37   91.45 2033.35   145.9 2005.91   151.6  2001.8   163.7 1990.58
   168.6 1989.01   183.2 1988.66   191.8 1987.07  220.831968.154   227.4 1964.91
     247 1959.54   276.4 1955.05   349.6 1954.91   404.7 1953.06   510.2  1954.6
   522.2 1955.67  532.571953.978   544.1 1952.16   553.8 1949.97   562.5 1949.88
   573.1 1949.99   585.5 1952.05   611.8 1954.34   625.8  1959.6   642.21959.879
  668.491965.057   700.6 1969.78   759.8 1985.98     794 2002.02   859.2 2036.96
#Mann= 8 ,-1 , 0
       0     .05       0   91.45     .06       0  220.83     .05       0
  532.57      .1       0   544.1    .045       0   585.5      .1       0
   642.2      .1       0  668.49      .1       0
Bank Sta=544.1,585.5
XS Rating Curve= 0 ,0
Exp/Cntr(USF)=0,0
Exp/Cntr=0.5,0.3

Type RM Length L Ch R = 1 ,183627  ,27.8,27.9,28
XS GIS Cut Line= 4
2445138.15914962540791.2424039842445568.36748296540536.034070641
 2445711.0758163540516.2424039692445969.40914965540332.909070641
#Sta/Elev= 30
       0 2065.54   19.272056.182  125.992004.664   144.9 1995.33   161.2 1983.61
   186.7  1980.5   214.6 1961.26   219.3 1958.86  232.711956.377   321.6 1951.75
   377.3 1953.75   502.6  1953.5   518.8 1955.44   542.3 1952.06   551.1 1949.55
   575.3 1948.35   583.4 1949.76   587.4 1951.89   603.6 1960.26   635.9 1962.83
   658.6 1969.97   678.2 1971.25   688.1 1975.26  699.221976.799  759.711988.079
   851.6  2009.6  870.362015.399   933.3  2029.9     948 2032.06   961.1  2032.1
#Mann= 9 ,-1 , 0
       0     .12       0   19.27     .05       0  125.99     .06       0
  232.71     .05       0   542.3    .045       0   587.4      .1       0
  699.22     .05       0  759.71      .1       0  870.36      .1       0
#XS Ineff= 2 , 0
                             597         1956.35
Permanent Ineff=
       F       F
Bank Sta=542.3,587.4
XS Rating Curve= 0 ,0
Exp/Cntr(USF)=0,0
Exp/Cntr=0.5,0.3