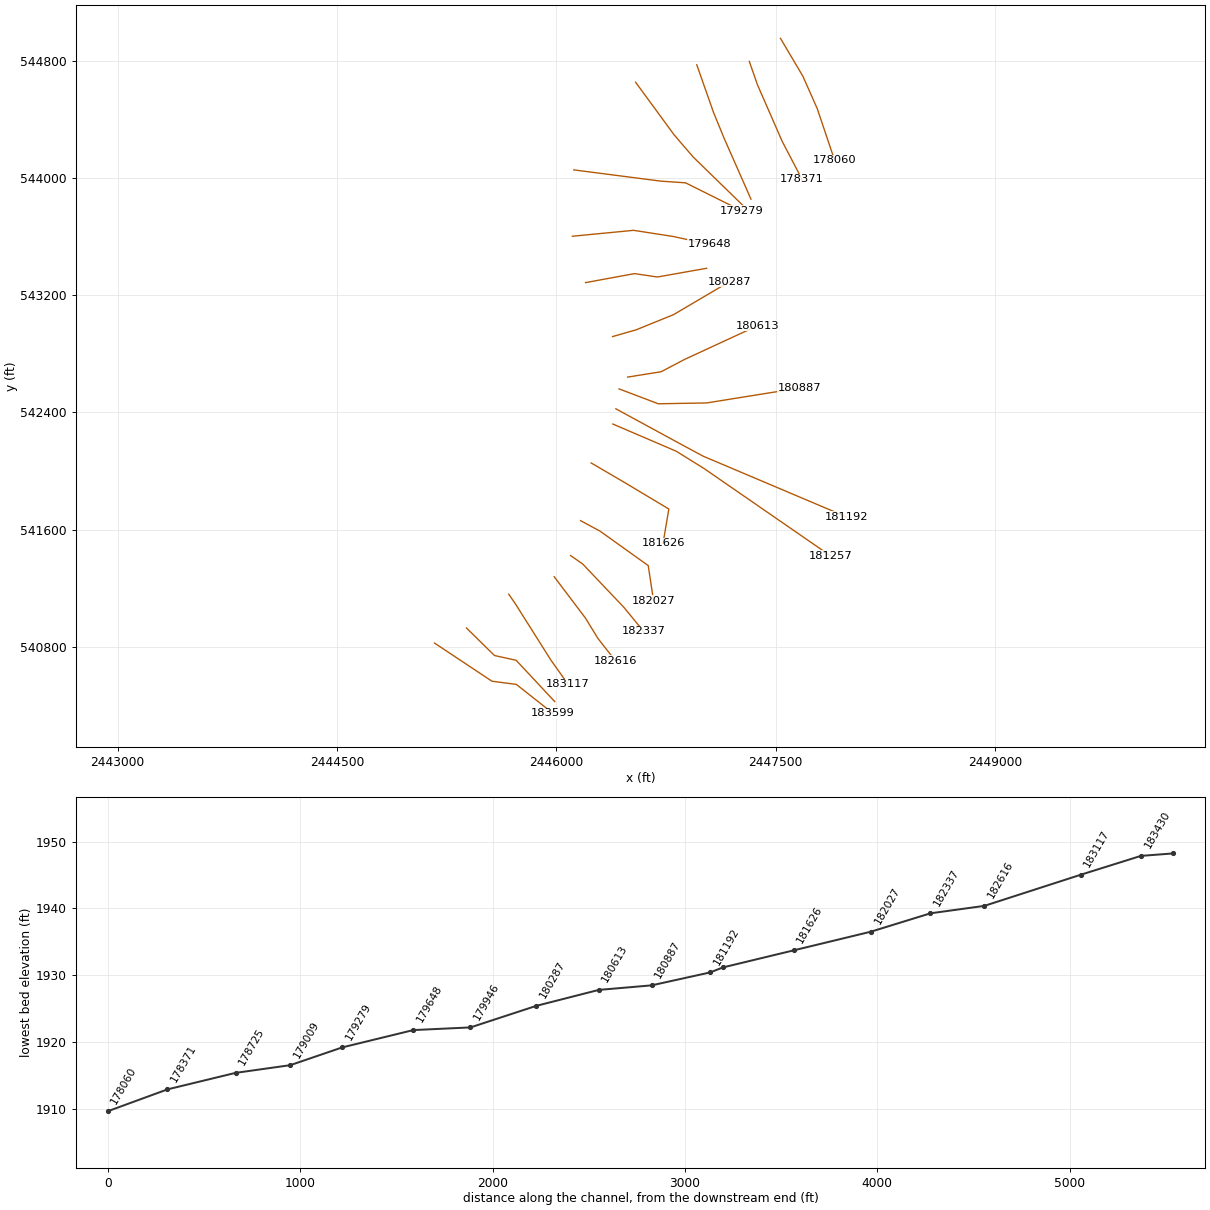
HEC-RAS study SFSBPOTOMC.prj: SFSBPOTOMC

--- SFSBPOTOMC.g01 (geometry) --- (continued)

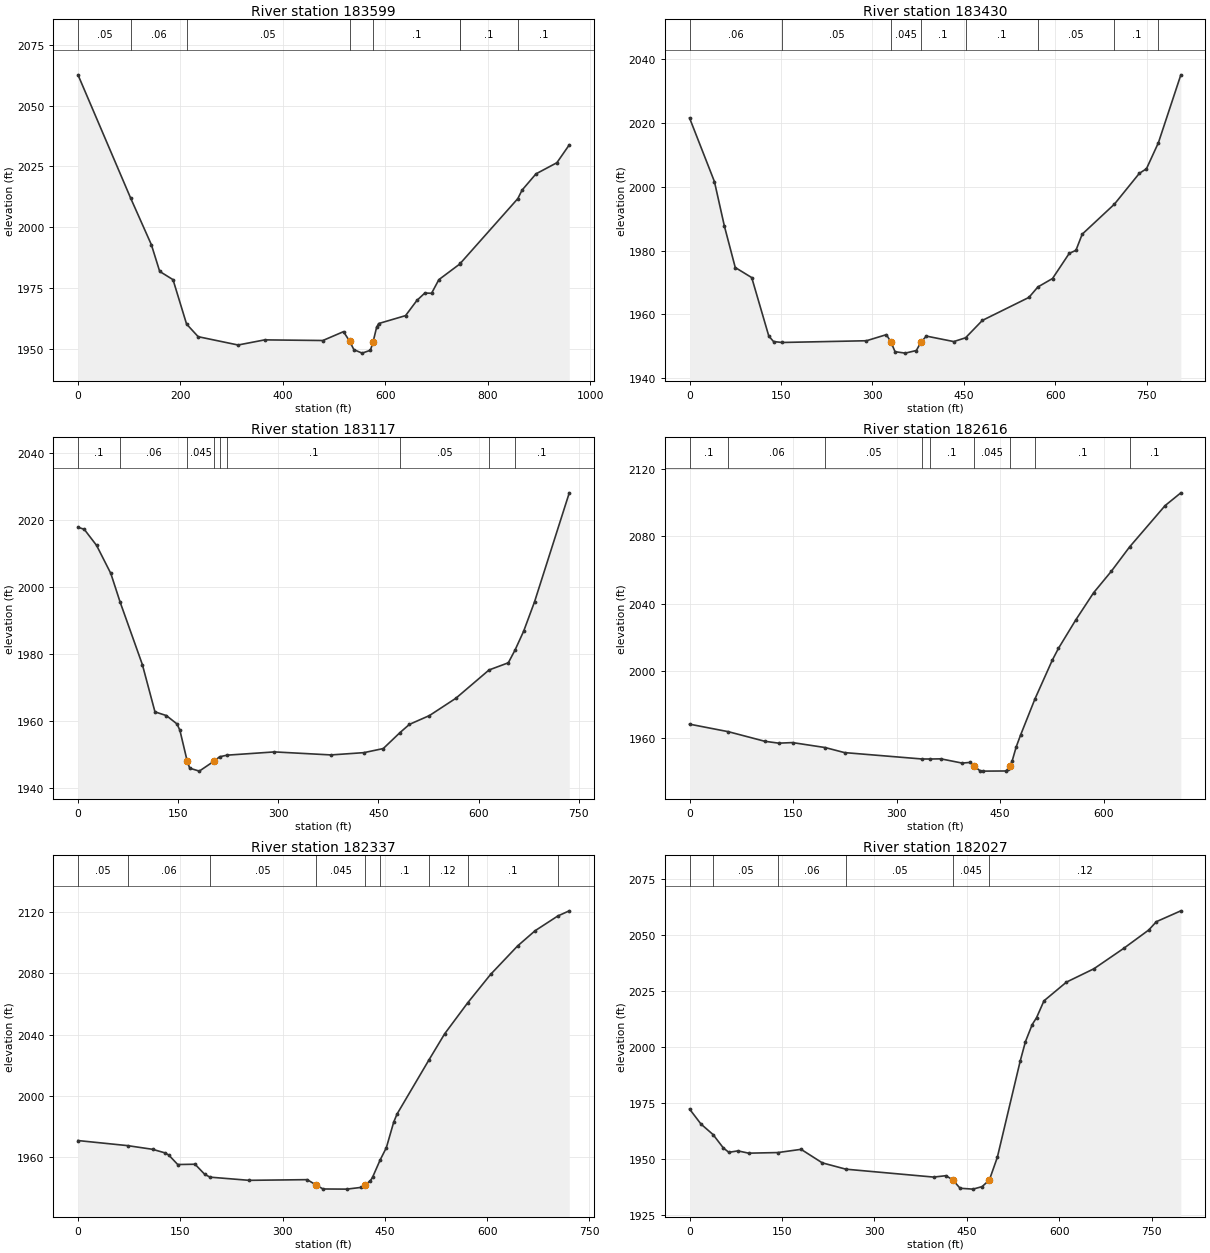
Type RM Length L Ch R = 1 ,183599  ,171.4,168.9,166.7
XS GIS Cut Line= 4
 2445167.3258163540824.5757373122445560.03414965540564.159070641
 2445726.7008163540542.2840706562445977.74248296540344.367403969
#Sta/Elev= 30
       0 2062.67  102.952011.908   143.3  1992.8   159.5 1981.84   185.5 1978.45
  211.951960.196   234.6    1955   312.5 1951.58   364.4 1953.69     478 1953.43
   518.3 1957.07   530.4 1953.09   538.5 1949.67   554.6 1948.24   570.8 1949.42
  575.961952.822   582.9 1958.84   586.9  1960.4   639.4 1963.66   661.7 1969.95
   677.1 1972.95   690.2 1972.85   704.4 1978.45  744.94 1984.83  746.531985.202
  858.542011.773   866.8 2015.26     894 2021.95   934.8 2026.53     959 2033.89
#Mann= 8 ,-1 , 0
       0     .05       0  102.95     .06       0  211.95     .05       0
   530.4    .045       0  575.96      .1       0  744.94     .05       0
  746.53      .1       0  858.54      .1       0
Bank Sta=530.4,575.96
XS Rating Curve= 0 ,0
Exp/Cntr(USF)=0,0
Exp/Cntr=0.5,0.3

Type RM Length L Ch R = 1 ,183430  ,329.8,313.9,292.5
XS GIS Cut Line= 4
2445385.91616438540927.4316444252445577.41495815540739.546035439
2445725.55553447540707.0273723452445989.31802401540425.198958865
#Sta/Elev= 30
       0 2021.55    40.8 2001.63    57.2 1987.64      75 1974.69     102 1971.54
     130 1953.22   137.8  1951.5  151.721951.208   290.2 1951.75   322.9 1953.66
   330.4 1951.33   337.1 1948.32   353.9 1947.87     372 1948.69   379.4 1951.24
   388.4 1953.21   433.4 1951.49  452.761952.677   480.3 1958.12   556.7 1965.33
   571.41968.603   595.4 1971.25   622.8 1979.12   633.8 1980.08   644.1 1985.14
   696.91994.544   737.8  2004.2   749.5 2005.64   769.12013.806   805.9 2035.07
#Mann= 8 ,-1 , 0
       0     .06       0  151.72     .05       0   330.4    .045       0
   379.4      .1       0  452.76      .1       0   571.4     .05       0
   696.9      .1       0   769.1      .1       0
Bank Sta=330.4,379.4
XS Rating Curve= 0 ,0
Exp/Cntr(USF)=0,0
Exp/Cntr=0.3,0.1

Type RM Length L Ch R = 1 ,183117  ,491.8,500.2,496.9
XS GIS Cut Line= 4
2445674.97094744 541158.675470872445721.94234968541090.024959894
2445964.02573049540707.0273723452446079.64764371540544.434056876
#Sta/Elev= 30
       0 2017.75     9.4 2017.13    27.9 2012.32    49.2 2003.96   63.011995.494
    96.4 1976.82   115.3 1962.71   132.4  1961.6   148.4 1959.09   152.7 1957.16
   163.5 1948.09   167.3 1945.92   181.7 1945.04  204.311948.088  212.061949.313
  223.32  1949.8   294.3 1950.77   378.9 1949.87   428.2 1950.55   457.2 1951.77
  482.261956.532   496.4 1958.98   526.4 1961.61   565.9 1966.76  615.611975.199
   644.5 1977.34  654.561981.141   667.4 1986.73   683.7 1995.48   735.8 2028.01
#Mann= 9 ,-1 , 0
       0      .1       0   63.01     .06       0   163.5    .045       0
  204.31     .06       0  212.06     .05       0  223.32      .1       0
  482.26     .05       0  615.61      .1       0  654.56      .1       0
Bank Sta=163.5,204.31
XS Rating Curve= 0 ,0
Exp/Cntr(USF)=0,0
Exp/Cntr=0.3,0.1

Type RM Length L Ch R = 1 ,182616  ,272.7,279.8,277.2
XS GIS Cut Line= 4
2445985.70483922541277.9105688812446198.88274173540996.082155401
2446285.59917664540855.1679486622446404.83427465540703.414187557
#Sta/Elev= 30
       0 1968.32   56.261963.834   109.1 1958.13   129.2 1957.02   149.2 1957.36
  196.481954.412   224.5 1951.41  336.711947.612  349.021947.601   364.2 1947.69
   394.8 1945.18   406.5 1945.56  412.151943.559   420.5 1940.68   425.2 1940.39
   458.1 1940.48   461.7 1941.54   464.51943.563   467.5 1946.56   473.3 1954.85
   479.5 1961.74   500.51983.404   525.5 2006.32   534.4 2013.34   559.5 2030.26
   585.4 2046.46     611 2059.19  637.542073.701     689 2098.28   711.8 2105.87
#Mann= 9 ,-1 , 0
       0      .1       0   56.26     .06       0  196.48     .05       0
  336.71      .1       0  349.02      .1       0  412.15    .045       0
   464.5      .1       0   500.5      .1       0  637.54      .1       0
Bank Sta=412.15,464.5
XS Rating Curve= 0 ,0
Exp/Cntr(USF)=0,0
Exp/Cntr=0.3,0.1

Type RM Length L Ch R = 1 ,182337  ,302.4,309.7,317.9
XS GIS Cut Line= 4
2446097.71356766541422.4379604092446180.81681778541364.627003798
2446462.64523126541068.3458511652446596.33306843540905.752535696
#Sta/Elev= 30
       0 1970.97    72.8 1967.66   109.5 1965.25   127.2 1962.98     133 1961.58
   146.3 1955.33   171.7 1955.52   185.9 1948.93  193.761947.094   250.9 1945.02
   336.2 1945.46  349.481941.918   359.4 1939.38   394.2 1939.28     415 1940.39
  421.041941.918     429 1944.86     432 1946.97  443.211958.334   452.3 1966.34
   463.1 1983.04     468 1988.29  514.312023.244   537.9 2040.68  571.452060.758
   605.2 2079.38   644.8 2097.95   670.4 2107.85  703.782117.494   720.6 2120.85
#Mann= 9 ,-1 , 0
       0     .05       0    72.8     .06       0  193.76     .05       0
  349.48    .045       0  421.04     .05       0  443.21      .1       0
  514.31     .12       0  571.45      .1       0  703.78     .12       0
Bank Sta=349.48,421.04
XS Rating Curve= 0 ,0
Exp/Cntr(USF)=0,0
Exp/Cntr=0.3,0.1

Type RM Length L Ch R = 1 ,182027  ,396.9,400.8,403.4
XS GIS Cut Line= 4
2446166.36407863 541660.908156432446300.05191579541588.644460666
2446628.85173152541353.787449433 2446664.9835794541115.317253412
#Sta/Elev= 30
       0  1972.3    18.6 1965.58   38.171960.892    54.9  1954.9    63.8 1952.97
    78.5 1953.61    95.9 1952.59  143.33 1952.86     181  1954.3   215.4 1948.26
  253.671945.438     396 1941.91   416.1 1942.53  427.09 1940.66     439 1936.92
     460 1936.53   474.8 1937.66  486.541940.657   499.4 1950.71   536.5 1993.69
   545.1 2002.44     556 2010.02     563 2013.06   575.1 2020.62   611.6 2028.98
   656.1 2034.93   704.3 2044.01   745.1 2052.25   757.5 2055.97   797.2 2060.81
#Mann= 6 ,-1 , 0
       0      .1       0   38.17     .05       0  143.33     .06       0
  253.67     .05       0  427.09    .045       0  486.54     .12       0
Bank Sta=427.09,486.54
XS Rating Curve= 0 ,0
Exp/Cntr(USF)=0,0
Exp/Cntr=0.3,0.1

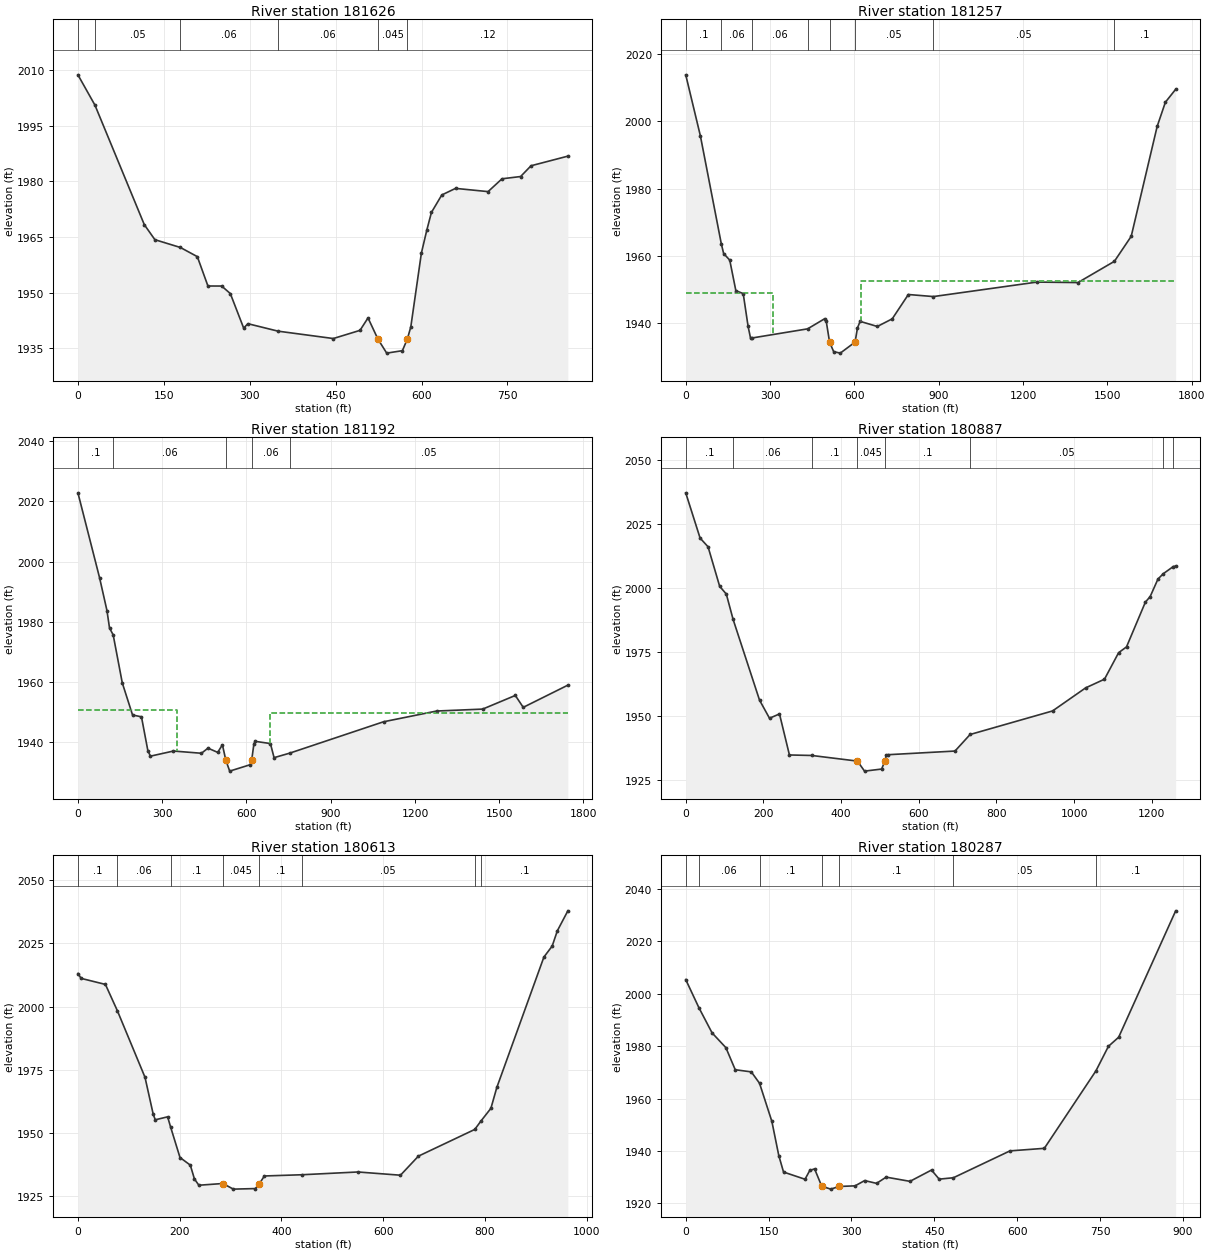
Type RM Length L Ch R = 1 ,181626  ,368.2,368.9,364.9
XS GIS Cut Line= 4
 2446238.6277744542054.7452983442446455.41886169541928.283830757
2446769.76593826541740.3982217712446730.02090559541505.541210538
#Sta/Elev= 30
       0 2008.66   29.742000.497   115.9 1968.33   134.4 1964.28  178.941962.179
   208.5 1959.71     227 1951.81     251  1951.8   266.1 1949.77   289.4 1940.48
   296.8 1941.66   349.41939.654   445.9 1937.67   492.5 1939.87   506.5 1943.22
  523.721937.541   539.1 1933.74   566.5  1934.4  575.171937.542   581.2 1940.81
   599.7  1960.7     609 1966.77   617.2 1971.62   635.3 1976.32   659.3 1978.09
   716.1 1977.22   740.4 1980.67   772.9 1981.28   791.1 1984.18   855.4 1986.77
#Mann= 6 ,-1 , 0
       0      .1       0   29.74     .05       0  178.94     .06       0
   349.4     .06       0  523.72    .045       0  575.17     .12       0
#XS Ineff= 2 , 0
          507.54 1940.92
Permanent Ineff=
       F       F
Bank Sta=523.72,575.17
XS Rating Curve= 0 ,0
Exp/Cntr(USF)=0,0
Exp/Cntr=0.5,0.3

Type RM Length L Ch R = 1 ,181257  ,61.3,65.2,67
XS GIS Cut Line= 4
2446386.77171096 542320.87211509 2446820.4508163542134.992403984
2447010.03414965542017.2840706412447873.00228262 541422.22107178
#Sta/Elev= 30
       0 2013.74    52.2 1995.61  126.511963.649   134.9 1960.72   156.6 1958.77
   178.4 1949.69   204.5 1948.86   221.9 1939.12   230.6 1935.63   235.71935.668
  433.57 1938.38   494.8 1941.41   499.7 1940.75  511.821934.446   526.3 1931.62
   549.9 1931.18  602.541934.449   611.1 1938.68   620.5  1940.6   681.7 1939.09
   734.7 1941.35   792.1 1948.57   881.3 1947.96  1249.8 1952.26  1395.5 1952.11
 1525.171958.414    1585 1965.83  1677.3 1998.43  1706.6 2005.62  1743.2 2009.45
#Mann= 8 ,-1 , 0
       0      .1       0  126.51     .06       0   235.7     .06       0
  433.57     .06       0  511.82    .045       0  602.54     .05       0
   881.3     .05       0 1525.17      .1       0
#XS Ineff= 2 , 0
          309.53 1949.03  624.97         1952.49
Permanent Ineff=
       F       F
Bank Sta=511.82,602.54
XS Rating Curve= 0 ,0
Exp/Cntr(USF)=0,0
Exp/Cntr=0.5,0.3

Type RM Length L Ch R = 1 ,181192  ,288.3,305,338
XS GIS Cut Line= 4
2446407.89385092542424.5626201032446862.11748299542177.700737327
2447005.86748299542100.617403984 2447986.0758163541686.034070656
#Sta/Elev= 30
       0 2022.82    77.1 1994.63   103.4 1983.74   112.5 1977.96  125.571975.659
     158 1959.72   194.5 1949.08   226.3 1948.46   249.1 1937.21   258.2 1935.41
   340.1 1937.11   439.9 1936.37   463.1 1938.07   497.7 1936.66   514.5 1939.19
  526.541934.088   540.4 1930.44     613 1932.56  618.71 1934.09   626.6 1939.48
   631.2 1940.33   685.4 1939.59   698.4 1934.91   754.51936.422    1088 1946.82
  1277.2 1950.39  1441.1 1951.03  1557.3 1955.56  1585.5 1951.61  1744.4 1958.98
#Mann= 5 ,-1 , 0
       0      .1       0  125.57     .06       0  526.54    .045       0
  618.71     .06       0   754.5     .05       0
#XS Ineff= 2 , 0
           352.9 1950.69  684.12         1949.86
Permanent Ineff=
       F       F
Bank Sta=526.54,618.71
XS Rating Curve= 0 ,0
Exp/Cntr(USF)=0,0
Exp/Cntr=0.5,0.3

Type RM Length L Ch R = 1 ,180887  ,257.7,274.4,293.3
XS GIS Cut Line= 4
2446429.01599079542560.8964322222446697.84322597 542459.12612176
2447028.11668634542464.886705371 2447663.7010781542566.657015833
#Sta/Elev= 30
       0 2037.17      37  2019.5    57.5  2016.1    87.4 2000.66   104.5 1997.64
  121.941987.763     190 1956.23   215.7 1949.15   241.4 1950.83     267 1934.81
  324.491934.614  442.181932.412   460.4  1928.5   504.4 1929.31  512.811932.414
   516.4 1934.78   520.7 1934.91   693.3 1936.34   732.21942.804   944.5    1952
  1029.6    1961  1078.2  1964.4  1114.6 1974.75  1134.9 1977.01  1183.5 1994.49
  1195.7 1996.63  1215.9 2003.51 1229.832005.618 1255.272008.376  1261.5 2008.57
#Mann= 8 ,-1 , 0
       0      .1       0  121.94     .06       0  324.49      .1       0
  442.18    .045       0  512.81      .1       0   732.2     .05       0
 1229.83      .1       0 1255.27     .05       0
Bank Sta=442.18,512.81
XS Rating Curve= 0 ,0
Exp/Cntr(USF)=0,0
Exp/Cntr=0.3,0.1

Type RM Length L Ch R = 1 ,180613  ,327.1,325.3,327
XS GIS Cut Line= 4
2446488.54202144542641.5446027772446717.04517134542678.028298981
2446878.34151245 542762.516858612447377.59209208542992.940203053
#Sta/Elev= 30
       0 2013.04     6.3 2011.12    54.1 2008.73   77.541998.346   131.9 1972.03
   148.1 1957.38   152.1 1955.22   176.4  1956.4  182.141952.434   200.7 1940.32
     221  1937.3   229.1 1931.84   237.8 1929.36     285 1930.04   305.6 1927.82
   348.9 1928.04   356.7 1929.93   366.6 1933.02  440.211933.502   550.5  1934.6
   634.2 1933.32   669.4 1940.85  780.261951.415  792.641954.791     812 1959.76
   823.6 1967.99   916.2 2019.55   932.5  2023.9   942.6 2029.92   963.3 2037.82
#Mann= 8 ,-1 , 0
       0      .1       0   77.54     .06       0  182.14      .1       0
     285    .045       0   356.7      .1       0  440.21     .05       0
  780.26      .1       0  792.64      .1       0
Bank Sta=285,356.7
XS Rating Curve= 0 ,0
Exp/Cntr(USF)=0,0
Exp/Cntr=0.3,0.1

Type RM Length L Ch R = 1 ,180287  ,355.1,341.6,333.8
XS GIS Cut Line= 4
2446384.85151644542918.0526161092446546.14785755542964.137284998
2446801.53373097543067.8277899972447183.65244384543292.490550829
#Sta/Elev= 30
       0  2005.4   23.871994.655    47.7 1985.05    72.7 1979.41    89.6 1970.99
   118.7 1970.17  133.591965.822   155.9 1951.27   168.4 1938.26     177 1931.95
   215.9  1929.2   224.5 1932.55   233.2 1933.16   246.1 1926.56   262.4 1925.43
   277.8 1926.45   306.5 1926.68   323.8 1928.69   345.4 1927.63   362.7 1930.01
   405.8  1928.4   444.8 1932.71   458.7 1929.24  484.36 1929.77   586.8 1940.02
     649    1941  742.391970.565     765 1979.93   783.5 1983.39   886.7 2031.63
#Mann= 7 ,-1 , 0
       0      .1       0   23.87     .06       0  133.59      .1       0
   246.1    .045       0   277.8      .1       0  484.36     .05       0
  742.39      .1       0
Bank Sta=246.1,277.8
XS Rating Curve= 0 ,0
Exp/Cntr(USF)=0,0
Exp/Cntr=0.3,0.1

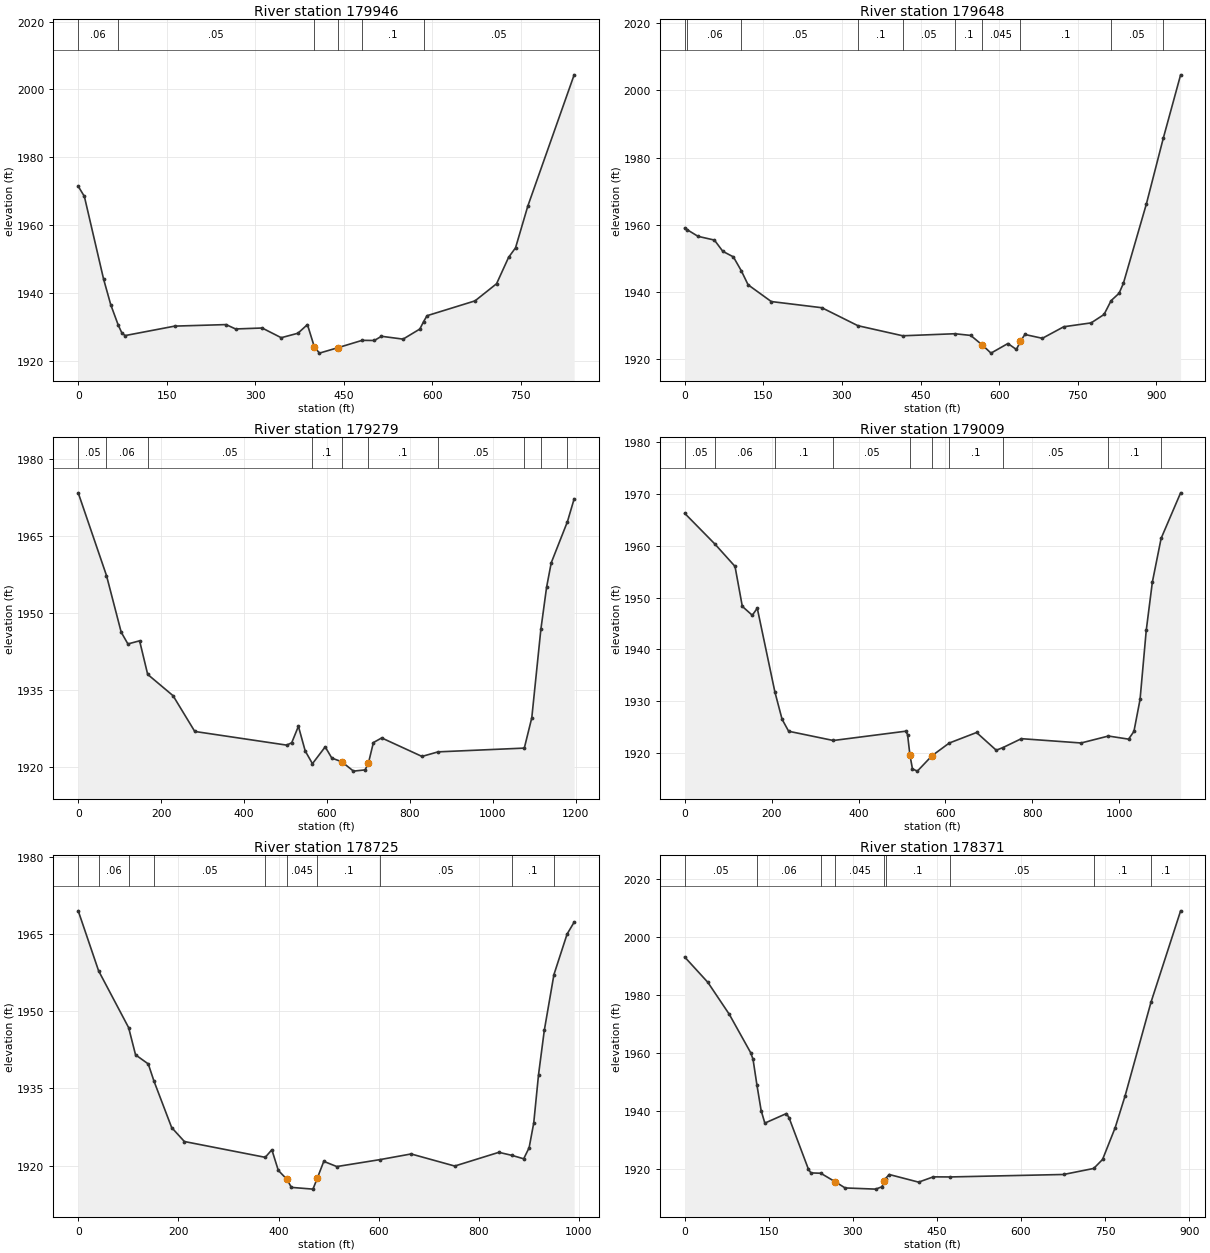
Type RM Length L Ch R = 1 ,179946  ,293.4,297.1,299.5
XS GIS Cut Line= 4
2446200.51284088543286.7299672182446534.62669032543348.176192403
2446692.08264236543325.1338579592447028.11668634543384.659888607
#Sta/Elev= 30
       0 1971.45    10.4 1968.46    42.9 1944.11    55.1  1936.5   67.891930.439
    74.2 1928.08    79.5 1927.39   163.5 1930.18   250.4 1930.63   266.6 1929.34
   311.6 1929.62   343.9 1926.76   372.2 1928.08   388.3 1930.63   399.9  1924.1
   408.6 1922.21   439.7  1923.8  480.98 1925.98   501.6 1925.94   513.7 1927.18
   550.3 1926.34   578.7 1929.32  585.121931.519   590.9 1933.25   672.2 1937.63
   708.7 1942.69     729 1950.45   740.8 1953.28   761.5 1965.54   840.1 2004.32
#Mann= 6 ,-1 , 0
       0     .06       0   67.89     .05       0   399.9    .045       0
   439.7     .05       0  480.98      .1       0  585.12     .05       0
Bank Sta=399.9,439.7
XS Rating Curve= 0 ,0
Exp/Cntr(USF)=0,0
Exp/Cntr=0.3,0.1

Type RM Length L Ch R = 1 ,179648  ,365.7,369.3,371.4
XS GIS Cut Line= 4
2446110.26369764543603.5620658282446528.86610671543643.886151105
2446801.53373097543601.6418712912447045.39843717543547.876424254
#Sta/Elev= 30
       0 1959.06    5.281958.482    25.5 1956.56    56.7 1955.45    72.8  1952.1
    92.9 1950.45  107.961946.344     121 1942.14   165.2 1937.16   261.7 1935.32
  330.511929.971  416.021926.971  515.49 1927.58   545.7 1927.08   568.2 1924.18
   584.4 1921.81   616.7 1924.67   632.9 1922.89   640.4  1925.3   649.1 1927.36
   682.4 1926.22   723.3 1929.66   775.5 1930.81   800.1 1933.31  813.631937.441
   828.8 1939.62     837 1942.57     881 1966.27  913.11 1985.75   946.2 2004.62
#Mann= 10 ,-1 , 0
       0     .05       0    5.28     .06       0  107.96     .05       0
  330.51      .1       0  416.02     .05       0  515.49      .1       0
   568.2    .045       0   640.4      .1       0  813.63     .05       0
  913.11      .1       0
Bank Sta=568.2,640.4
XS Rating Curve= 0 ,0
Exp/Cntr(USF)=0,0
Exp/Cntr=0.3,0.1

Type RM Length L Ch R = 1 ,179279  ,291.6,270.4,243.6
XS GIS Cut Line= 4
2446119.86467033544056.727976566 2446715.1249768543979.920195085
2446884.10209606543968.3990278632447266.22080893543778.299768697
#Sta/Elev= 30
       0 1973.38    68.21957.287   103.7 1946.26   119.9 1943.97   148.1 1944.58
  167.57 1938.05   228.8  1933.9   281.2 1926.94     503 1924.28   515.1 1924.75
   531.2 1927.95   547.6 1923.15  565.051920.668   595.8 1923.94   611.8 1921.76
   635.9 1921.04     664 1919.22     692 1919.46     700 1920.75   712.1 1924.78
   732.1 1925.68   829.3 1922.08  868.18 1922.97 1076.161923.701  1094.2  1929.6
 1116.081946.794  1129.9    1955  1141.1 1959.76 1180.15 1967.76  1196.4 1972.21
#Mann= 10 ,-1 , 0
       0     .05       0    68.2     .06       0  167.57     .05       0
  565.05      .1       0   635.9    .045       0     700      .1       0
  868.18     .05       0 1076.16      .1       0 1116.08     .12       0
 1180.15      .1       0
Bank Sta=635.9,700
XS Rating Curve= 0 ,0
Exp/Cntr(USF)=0,0
Exp/Cntr=0.3,0.1

Type RM Length L Ch R = 1 ,179009  ,290.4,283.9,271.6
XS GIS Cut Line= 4
2446542.30746847544655.8286721182446805.37412005544296.752293694
2446935.94734856544145.0569252692447291.18333791543799.421908604
#Sta/Elev= 30
       0 1966.22   69.421960.306   115.8 1955.99   132.6 1948.29   155.5 1946.58
     167 1947.94  207.481931.824   224.1 1926.54   239.2 1924.24  341.97 1922.46
   508.5 1924.25   512.7  1923.6   518.3  1919.6     524 1916.99   535.3 1916.56
     569 1919.53  608.65 1921.97   671.5    1924   716.7 1920.59  732.311921.103
   774.6 1922.81   911.9 1921.98  974.81 1923.32  1021.2 1922.72  1033.5 1924.21
  1047.6 1930.37  1061.8 1943.66  1075.9 1952.97 1096.061961.391  1140.9 1970.16
#Mann= 10 ,-1 , 0
       0     .05       0   69.42     .06       0  207.48      .1       0
  341.97     .05       0   518.3    .045       0     569     .05       0
  608.65      .1       0  732.31     .05       0  974.81      .1       0
 1096.06     .12       0
Bank Sta=518.3,569
XS Rating Curve= 0 ,0
Exp/Cntr(USF)=0,0
Exp/Cntr=0.3,0.1

Type RM Length L Ch R = 1 ,178725  ,354.1,354.1,354.5
XS GIS Cut Line= 4
2446960.90987754544774.8807334142447074.20135523544452.288051193
2447149.08894217544269.8695701762447331.50742319543857.027744715
#Sta/Elev= 30
       0 1969.54    40.71957.874  100.691946.819   114.5 1941.53   139.9 1939.76
  151.341936.406   186.6 1927.39     212 1924.67  373.541921.594   386.7 1923.07
   399.6 1919.05   417.1 1917.29   425.6 1915.75   468.8 1915.41   477.5 1917.55
   490.4 1920.81   516.4  1919.8  602.491921.147   664.8 1922.25   751.9  1919.9
   840.1 1922.57     8671921.957   889.6 1921.31   900.5 1923.47   909.7 1928.28
   919.3  1937.7   930.8  1946.3  950.041957.143   976.3 1965.02   990.4 1967.34
#Mann= 10 ,-1 , 0
       0      .1       0    40.7     .06       0  100.69    .055       0
  151.34     .05       0  373.54      .1       0   417.1    .045       0
   477.5      .1       0  602.49     .05       0     867      .1       0
  950.04     .12       0
Bank Sta=417.1,477.5
XS Rating Curve= 0 ,0
Exp/Cntr(USF)=0,0
Exp/Cntr=0.3,0.1

Type RM Length L Ch R = 1 ,178371  ,312.1,310.4,309.2
XS GIS Cut Line= 4
2447319.98625597544797.9230678582447375.67189754544638.546921285
 2447544.6490168544252.5878193432447680.98282893543991.441362307
#Sta/Elev= 30
       0 1992.95    41.3 1984.22    79.5 1973.22   117.6 1960.01   121.9 1957.74
  128.941948.763   136.4 1940.03     143 1935.69   181.5 1938.99   186.1 1937.58
   220.8 1919.78   225.2 1918.53  242.721918.417   268.9 1915.43   286.2 1913.35
   340.8 1912.94   351.8 1913.75     356 1915.57  358.321916.601   364.9 1917.98
   417.3 1915.35   443.5 1917.17  473.921917.139     676 1917.99   729.71920.071
   745.5 1923.18   767.9 1934.09   785.7 1945.12  831.811977.331   884.7 2008.86
#Mann= 9 ,-1 , 0
       0     .05       0  128.94     .06       0  242.72    .045       0
   268.9    .045       0     356    .045       0  358.32      .1       0
  473.92     .05       0   729.7      .1       0  831.81      .1       0
Bank Sta=268.9,356
XS Rating Curve= 0 ,0
Exp/Cntr(USF)=0,0
Exp/Cntr=0.3,0.1

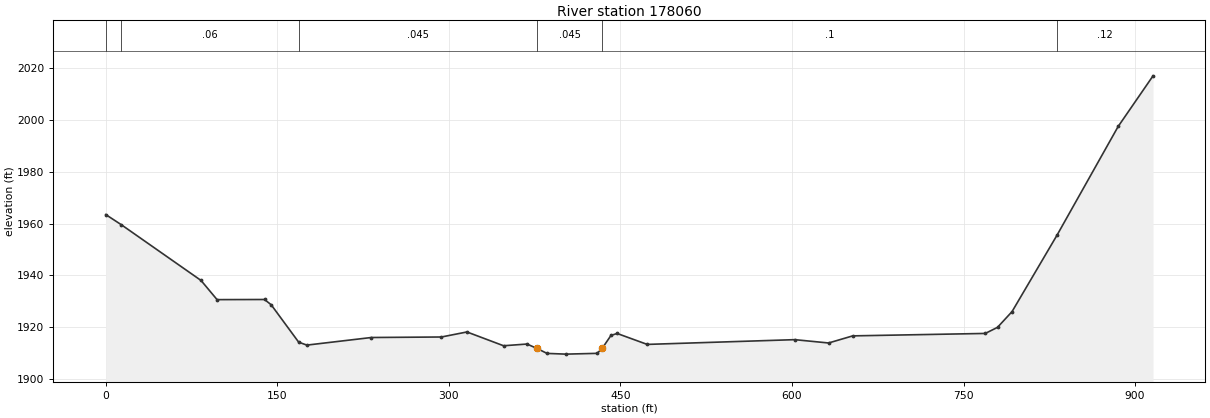
Type RM Length L Ch R = 1 ,178060  ,197.5,203,212
XS GIS Cut Line= 4
2447533.12784958544955.3790198942447686.74341254544696.152757396
2447784.67333393544475.3303856382447903.72539522544122.014590825
#Sta/Elev= 30
       0 1963.49    13.71959.549    83.3 1938.08    97.3 1930.69   138.8 1930.74
   144.6 1928.72  168.651914.291   175.8 1913.15   232.2 1916.08   293.5 1916.28
   315.8 1918.22   347.8  1912.9   368.3 1913.56   377.1 1911.85   385.8 1909.95
   402.3 1909.67   429.6 1909.97     434 1911.86   441.7 1916.87   447.1 1917.64
   473.4 1913.42   602.4 1915.25     632 1913.97   653.1 1916.71     769 1917.65
   779.7    1920   792.4 1926.07  831.831955.622   885.2 1997.48   915.7 2017.01
#Mann= 6 ,-1 , 0
       0      .1       0    13.7     .06       0  168.65    .045       0
   377.1    .045       0     434      .1       0  831.83     .12       0
Bank Sta=377.1,434
XS Rating Curve= 0 ,0
Exp/Cntr(USF)=0,0
Exp/Cntr=0.3,0.1