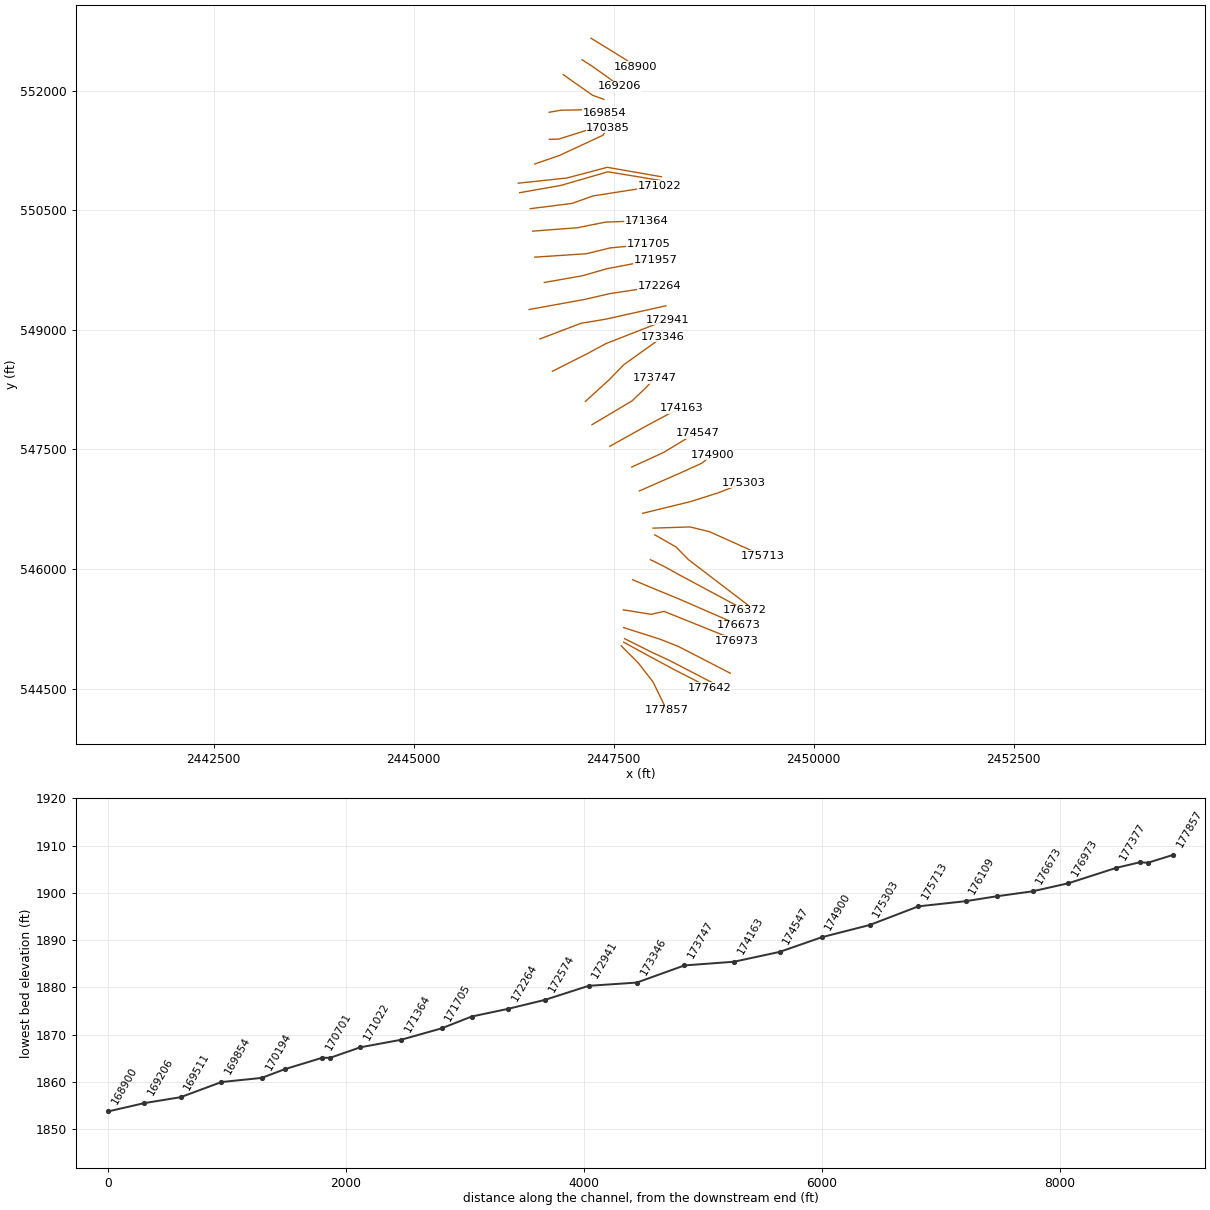
HEC-RAS study SFSBPOTOMC.prj: SFSBPOTOMC

--- SFSBPOTOMC.g01 (geometry) --- (continued)

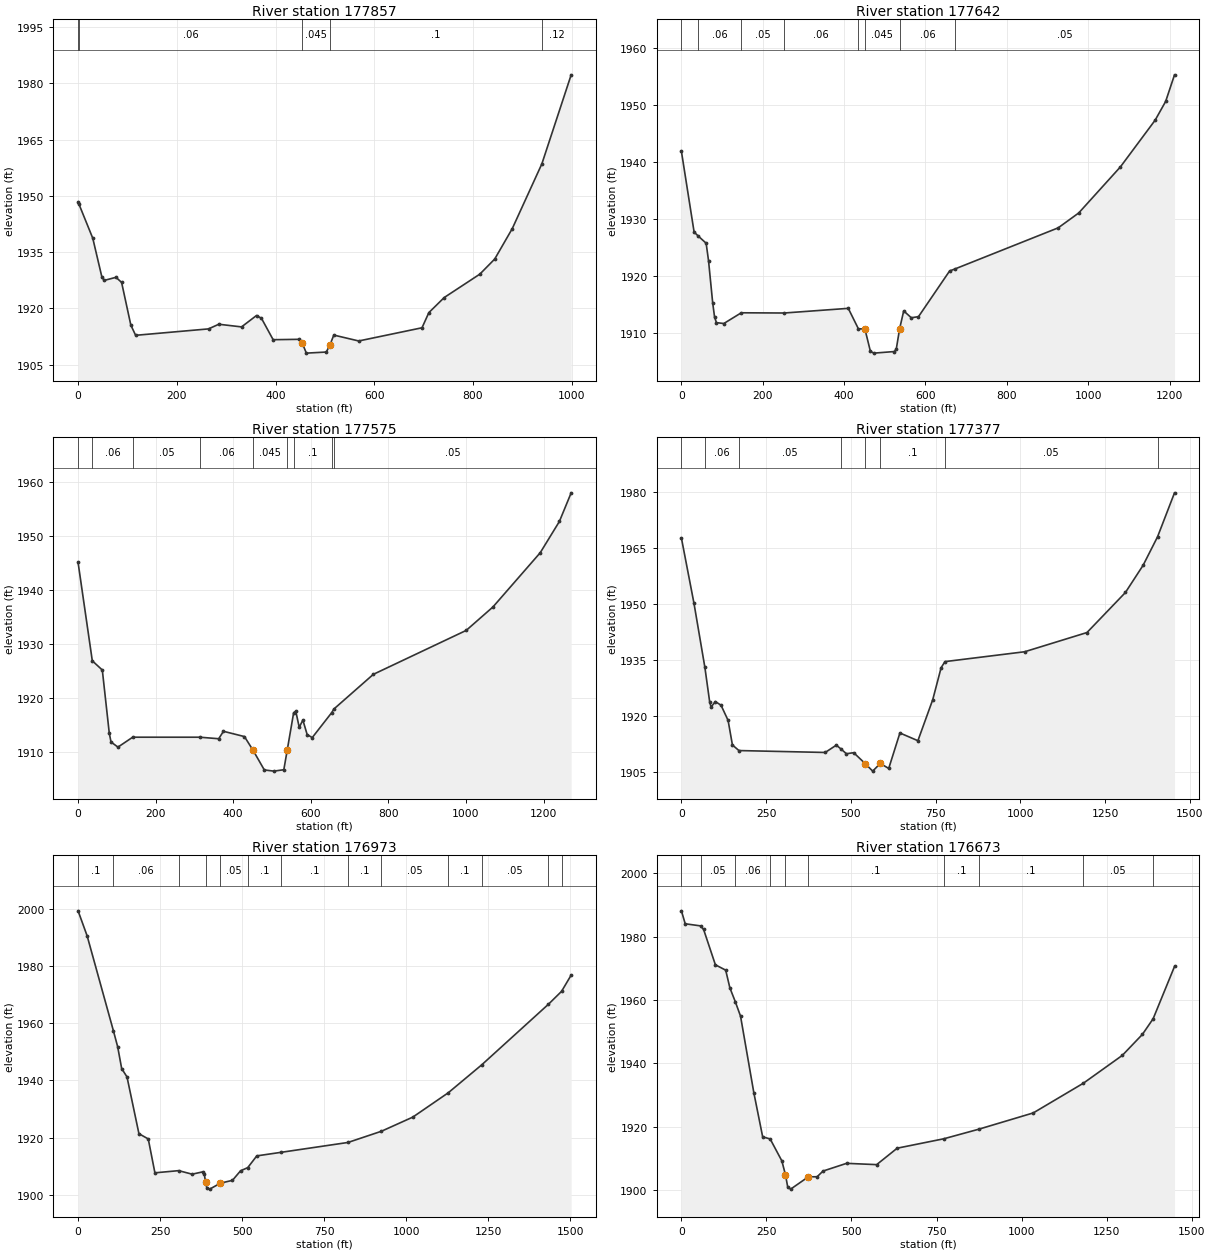
Type RM Length L Ch R = 1 ,177857  ,203.5,215.6,234.6
XS GIS Cut Line= 4
2447592.65388023545036.0271904492447809.63586291544817.125013228
2447990.13414939544582.8612797112448162.95165772544227.625290361
#Sta/Elev= 30
       0  1948.4    1.321947.938    29.8 1938.69    48.4 1928.27    53.2 1927.46
    76.8 1928.28    88.2 1926.92   106.9 1915.54   116.6 1912.82   264.3 1914.53
   285.1 1915.77   331.2 1915.06   361.5  1918.1   371.6 1917.34   395.2 1911.65
   447.5 1911.75   454.2 1910.74   462.5 1908.07   502.9 1908.36   510.2 1910.23
   518.1 1912.88   568.6 1911.31   696.8 1914.83   710.7 1918.87   741.8 1922.89
   813.9 1929.12   844.1 1933.15   879.7 1941.27  939.621958.522     999 1982.26
#Mann= 5 ,-1 , 0
       0      .1       0    1.32     .06       0   454.2    .045       0
   510.2      .1       0  939.62     .12       0
Bank Sta=454.2,510.2
XS Rating Curve= 0 ,0
Exp/Cntr(USF)=0,0
Exp/Cntr=0.5,0.3

Type RM Length L Ch R = 1 ,177642  ,63.7,66.7,68.9
XS GIS Cut Line= 4
2447623.37699282545082.1118593382447961.33123133544895.852989246
2448260.88157911544734.5566481362448692.92534994544511.814081841
#Sta/Elev= 30
       0  1941.8    31.2 1927.64   41.731926.905    60.8 1925.67    66.7 1922.59
    76.9  1915.2    81.5 1912.71    86.1 1911.73   104.3 1911.58  147.191913.461
  252.641913.422   410.2 1914.24  435.031910.657   451.1 1910.61   464.7 1906.67
   473.3 1906.38   523.8 1906.66   528.3 1907.13  536.491910.681   546.5 1913.79
   565.1 1912.59   582.8 1912.78   659.3  1920.8  673.491921.185   926.2 1928.37
   976.7 1930.98  1079.2 1939.07  1164.7 1947.28  1190.5 1950.57  1212.2 1955.23
#Mann= 8 ,-1 , 0
       0      .1       0   41.73     .06       0  147.19     .05       0
  252.64     .06       0  435.03      .1       0   451.1    .045       0
  536.49     .06       0  673.49     .05       0
#XS Ineff= 2 , 0
             420 1911.52     566         1911.52
Permanent Ineff=
       F       F
Bank Sta=451.1,536.49
XS Rating Curve= 0 ,0
Exp/Cntr(USF)=0,0
Exp/Cntr=0.5,0.3

Type RM Length L Ch R = 1 ,177575  ,196.9,197.7,200.2
XS GIS Cut Line= 4
2447634.89816004545126.2763336892447982.45337124 544951.53863082
2448189.83438124544855.5289039692448769.73313142544554.058361656
#Sta/Elev= 30
       0 1945.15   36.691926.927    62.5 1925.22    80.4 1913.54    84.9 1911.89
   102.8 1910.94  140.811912.775  314.431912.773   362.5 1912.49   374.8 1913.87
   428.9 1912.89  450.951910.367   480.1 1906.71   504.8 1906.49   530.4 1906.75
  539.121910.368  555.711917.311   561.2 1917.59   570.1 1914.61   579.5 1915.95
   590.5 1913.27   603.6  1912.7  653.851917.329  659.431917.996   761.1 1924.42
  1000.5 1932.56  1069.4  1936.9  1191.3 1946.95  1240.7 1952.74  1271.1 1958.05
#Mann= 9 ,-1 , 0
       0      .1       0   36.69     .06       0  140.81     .05       0
  314.43     .06       0  450.95    .045       0  539.12     .06       0
  555.71      .1       0  653.85     .06       0  659.43     .05       0
Bank Sta=450.95,539.12
XS Rating Curve= 0 ,0
Exp/Cntr(USF)=0,0
Exp/Cntr=0.5,0.3

Type RM Length L Ch R = 1 ,177377  ,384.3,404.2,413.9
XS GIS Cut Line= 4
2447623.37699282545264.5303403552448074.62270902545120.515750078
  2448306.966248545028.3464123012448955.99200151544692.312368321
#Sta/Elev= 30
       0 1967.76    37.1 1950.26   69.251933.091    83.3  1923.9    87.5 1922.48
   100.1 1923.95   116.9 1922.96   137.7  1918.9   150.5 1912.31  169.67 1910.82
   424.1 1910.31     457 1912.27  470.931911.224   486.7 1909.97   508.2 1910.25
   542.3 1907.31   564.2 1905.31   586.6 1907.36   611.5 1906.03   644.5 1915.53
   697.6 1913.46   741.4 1924.47   766.1 1933.03  777.451934.651  1012.4 1937.29
  1196.3 1942.44  1309.7 1953.17  1361.9 1960.46  1404.61968.113  1454.5 1979.87
#Mann= 8 ,-1 , 0
       0      .1       0   69.25     .06       0  169.67     .05       0
  470.93      .1       0   542.3    .045       0   586.6      .1       0
  777.45     .05       0  1404.6      .1       0
Bank Sta=542.3,586.6
XS Rating Curve= 0 ,0
Exp/Cntr(USF)=0,0
Exp/Cntr=0.3,0.1

Type RM Length L Ch R = 1 ,176973  ,315,300.1,276.3
XS GIS Cut Line= 4
2447619.53660374 545487.272906652447967.09181495545431.587265077
2448128.38815606 545468.070961282449042.40075568545099.393610171
#Sta/Elev= 30
       0 1999.24    27.6  1990.5  107.941957.242   120.7 1951.76   132.9 1944.14
   149.1 1941.24   185.5  1921.4   213.9 1919.57   234.2 1907.73  306.581908.495
   347.6 1907.26   380.3 1908.08   384.6 1907.38   388.5 1904.53   392.6 1902.41
   401.3 1902.04   433.7 1904.12   470.6 1905.11   495.2 1908.44  517.19 1909.55
   544.7 1913.65  619.031914.898   822.7 1918.34  924.531922.252  1020.2 1927.19
 1128.191935.681 1230.021945.422 1433.691966.619 1473.591971.115  1502.9 1976.79
#Mann= 13 ,-1 , 0
       0      .1       0  107.94     .06       0  306.58     .05       0
   388.5    .045       0   433.7     .05       0  517.19      .1       0
  619.03      .1       0   822.7      .1       0  924.53     .05       0
 1128.19      .1       0 1230.02     .05       0 1433.69      .1       0
 1473.59     .05       0
Bank Sta=388.5,433.7
XS Rating Curve= 0 ,0
Exp/Cntr(USF)=0,0
Exp/Cntr=0.3,0.1

Type RM Length L Ch R = 1 ,176673  ,304.8,301.4,296.7
XS GIS Cut Line= 4
2447734.74827597545865.5512304452447961.33123133545769.541503593
2448310.80663707545625.5269133162449067.36328466545295.253452948
#Sta/Elev= 30
       0 1988.18    11.2 1984.09   56.381983.425    65.2 1982.31    99.9 1971.14
   130.2 1969.45   142.4 1963.89  158.63 1959.43   173.8 1954.94   212.9 1930.77
   238.9 1916.83  260.841916.187   295.2 1909.27  305.991904.828   312.5 1901.01
   321.2 1900.34   373.1 1904.22     399 1904.25   416.3 1906.04   485.6 1908.48
     574 1908.07   634.3 1913.26  771.621916.236  874.151919.253  1034.3 1924.39
 1181.731933.774  1296.1 1942.55  1355.2 1949.18 1386.78 1954.12  1449.6 1970.61
#Mann= 10 ,-1 , 0
       0      .1       0   56.38     .05       0  158.63     .06       0
  260.84     .05       0  305.99    .045       0   373.1      .1       0
  771.62      .1       0  874.15      .1       0 1181.73     .05       0
 1386.78      .1       0
Bank Sta=305.99,373.1
XS Rating Curve= 0 ,0
Exp/Cntr(USF)=0,0
Exp/Cntr=0.3,0.1

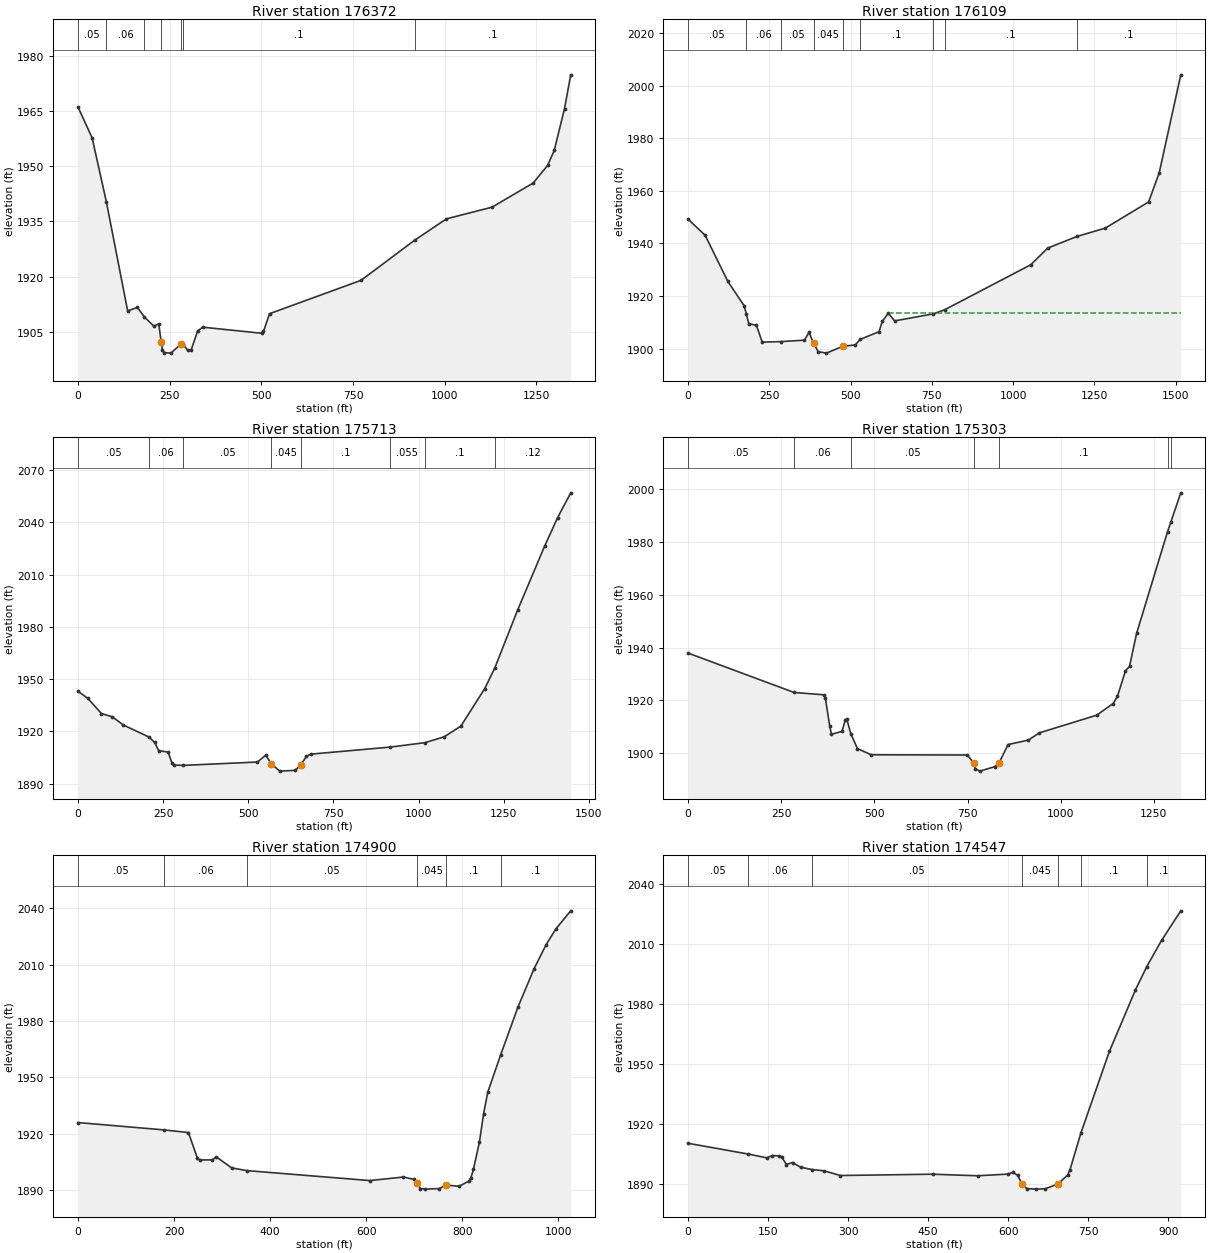
Type RM Length L Ch R = 1 ,176372  ,271.1,262.2,253
XS GIS Cut Line= 4
2447957.49084226546117.0967147952448128.38815606546032.608155166
  2448306.966248545932.7580392412449142.25087161545483.432517576
#Sta/Elev= 30
       0 1966.03    38.4 1957.69    77.21940.345   135.3 1910.75     162 1911.69
  181.111909.067   207.1 1906.58   220.1 1907.23   226.9 1902.24     230 1900.23
   235.1 1899.46   252.9 1899.29   280.4 1901.69  286.641901.771   298.7 1900.05
   308.3 1900.11   326.2 1905.31     340 1906.33   500.5 1904.68   505.7 1905.16
   522.2 1909.98     772 1919.05  917.761929.907  1004.8 1935.72  1128.9 1938.88
  1241.1 1945.42  1280.7 1950.23  1298.8 1954.29  1326.8 1965.65  1343.7 1974.79
#Mann= 7 ,-1 , 0
       0     .05       0    77.2     .06       0  181.11     .05       0
   226.9    .045       0   280.4     .05       0  286.64      .1       0
  917.76      .1       0
Bank Sta=226.9,280.4
XS Rating Curve= 0 ,0
Exp/Cntr(USF)=0,0
Exp/Cntr=0.3,0.1

Type RM Length L Ch R = 1 ,176109  ,370,396,421.4
XS GIS Cut Line= 4
2448013.17648383546428.1682297932448278.16332994546276.472861368
2448433.69908744546117.0967147952449217.13845855545516.075824706
#Sta/Elev= 30
       0 1949.23    52.5  1943.1   122.3 1925.53   172.1 1916.34  179.381913.063
   186.7 1909.44   210.2 1908.86     228 1902.44  285.461902.641   357.7 1903.18
   371.9 1906.13   385.8 1902.08   400.2  1898.8   425.7 1898.25   475.2 1900.82
   514.3 1901.38  529.151903.471   587.4 1906.43   597.4 1910.38   615.9 1913.45
   635.2 1910.52  754.72 1913.21  789.321914.767  1053.7 1931.87  1106.3 1938.23
 1195.941942.652  1283.5 1945.85  1416.6 1955.81    1449 1966.83  1515.5 2004.19
#Mann= 9 ,-1 , 0
       0     .05       0  179.38     .06       0  285.46     .05       0
   385.8    .045       0   475.2      .1       0  529.15      .1       0
  754.72    .055       0  789.32      .1       0 1195.94      .1       0
#XS Ineff= 2 , 0
                          620.27         1913.58
Permanent Ineff=
       F       F
Bank Sta=385.8,475.2
XS Rating Curve= 0 ,0
Exp/Cntr(USF)=0,0
Exp/Cntr=0.3,0.1

Type RM Length L Ch R = 1 ,175713  ,394.5,410.3,437.2
XS GIS Cut Line= 4
2447990.13414939546512.6567894232448452.90103281546528.018345719
2448694.84554448546468.492315071 2449364.9934379546167.021772758
#Sta/Elev= 30
       0 1943.02    28.6 1938.97    68.7 1930.22   100.7 1928.36   132.7 1923.68
   208.1 1916.76   224.7 1913.71   236.7 1908.96   264.8 1908.08   275.7 1901.81
   280.8 1900.65  309.321900.465   526.7 1902.38   551.4 1906.31   567.8 1901.28
   592.6 1897.16   637.9  1897.6  654.11 1900.84   670.9 1905.63   683.2 1906.91
  915.861910.943 1018.691913.494  1075.5 1916.87  1124.4 1923.03  1194.5 1944.59
 1224.341956.553    1291 1989.66    1370 2026.21  1408.3 2042.68    1447 2056.98
#Mann= 8 ,-1 , 0
       0     .05       0   208.1     .06       0  309.32     .05       0
   567.8    .045       0  654.11      .1       0  915.86    .055       0
 1018.69      .1       0 1224.34     .12       0
Bank Sta=567.8,654.11
XS Rating Curve= 0 ,0
Exp/Cntr(USF)=0,0
Exp/Cntr=0.3,0.1

Type RM Length L Ch R = 1 ,175303  ,400.2,403.2,408.1
XS GIS Cut Line= 4
2447861.48111541546698.9156595142448456.74142189546844.850444328
2448806.21682763546956.2217274762449124.96912077547081.034372382
#Sta/Elev= 30
       0  1937.9  284.261922.989   363.7 1922.11   368.2 1920.91   380.2 1910.16
   384.7 1907.17   413.1 1908.24   421.4 1912.41   425.5 1913.03   436.51907.441
   454.3 1901.74   491.4  1899.4   749.3 1899.31   766.9 1896.29   770.3 1894.16
   782.9 1893.21     823 1894.91   834.7 1896.43   858.5 1903.26   913.1 1904.96
   942.5 1907.69  1096.4 1914.39  1140.6 1918.81  1152.1 1921.55  1173.5 1931.12
  1184.5 1932.92  1203.6 1945.42 1286.581983.892  1294.91987.345    1322 1998.56
#Mann= 7 ,-1 , 0
       0     .05       0  284.26     .06       0   436.5     .05       0
   766.9    .045       0   834.7      .1       0 1286.58      .1       0
  1294.9      .1       0
Bank Sta=766.9,834.7
XS Rating Curve= 0 ,0
Exp/Cntr(USF)=0,0
Exp/Cntr=0.3,0.1

Type RM Length L Ch R = 1 ,174900  ,349,352.5,356.7
XS GIS Cut Line= 4
 2447819.2368356 546979.264061922448320.40760976547200.086433678
2448598.83581763547326.8192731222448735.16962976547432.429972658
#Sta/Elev= 30
       0    1926  178.391922.115   229.9 1920.69   248.6 1907.07     253 1906.13
   279.2 1906.15     288 1907.74   320.1 1901.87  352.221900.449   607.4 1895.17
   677.7 1897.05   699.7 1895.78  706.621893.841   712.8 1890.94   721.6 1890.62
   752.4 1890.91     766 1892.83   793.2 1892.11   813.9 1894.87   818.3 1896.79
   823.4 1901.17   835.9 1915.69   844.5 1930.63   853.2 1942.09  880.141962.046
   916.3 1987.52   949.6 2007.76   974.9 2020.63   995.1 2028.95    1026 2038.55
#Mann= 6 ,-1 , 0
       0     .05       0  178.39     .06       0  352.22     .05       0
  706.62    .045       0     766      .1       0  880.14      .1       0
Bank Sta=706.62,766
XS Rating Curve= 0 ,0
Exp/Cntr(USF)=0,0
Exp/Cntr=0.3,0.1

Type RM Length L Ch R = 1 ,174547  ,386.1,384.4,382.3
XS GIS Cut Line= 4
2447723.22710874547278.8144096962448124.54776698 547463.15308525
2448401.05578031547632.1302045092448543.15017605547701.257207842
#Sta/Elev= 30
       01910.454  112.881905.063 147.4931903.174 157.9341904.341 171.1391904.155
 175.5411903.586 184.3451899.842 195.7541900.834 210.8361898.502  232.511897.295
 254.7731896.697 285.5861894.333 458.2711894.993 542.6511894.204 598.9041895.031
  608.891895.871 617.6191894.499 626.3481890.042 635.0771887.799 652.5351887.524
 669.2211887.671  692.661889.997 711.4111894.466 716.0991897.339  736.381915.568
 789.8041956.374 838.7351987.202  859.961998.839 887.6652011.944 923.7022026.728
#Mann= 7 ,-1 , 0
       0     .05       0  112.88     .06       0  232.51     .05       0
 626.348    .045       0  692.66      .1       0  736.38      .1       0
  859.96      .1       0
Bank Sta=626.348,692.66
XS Rating Curve= 0 ,0
Exp/Cntr(USF)=0,0
Exp/Cntr=0.3,0.1

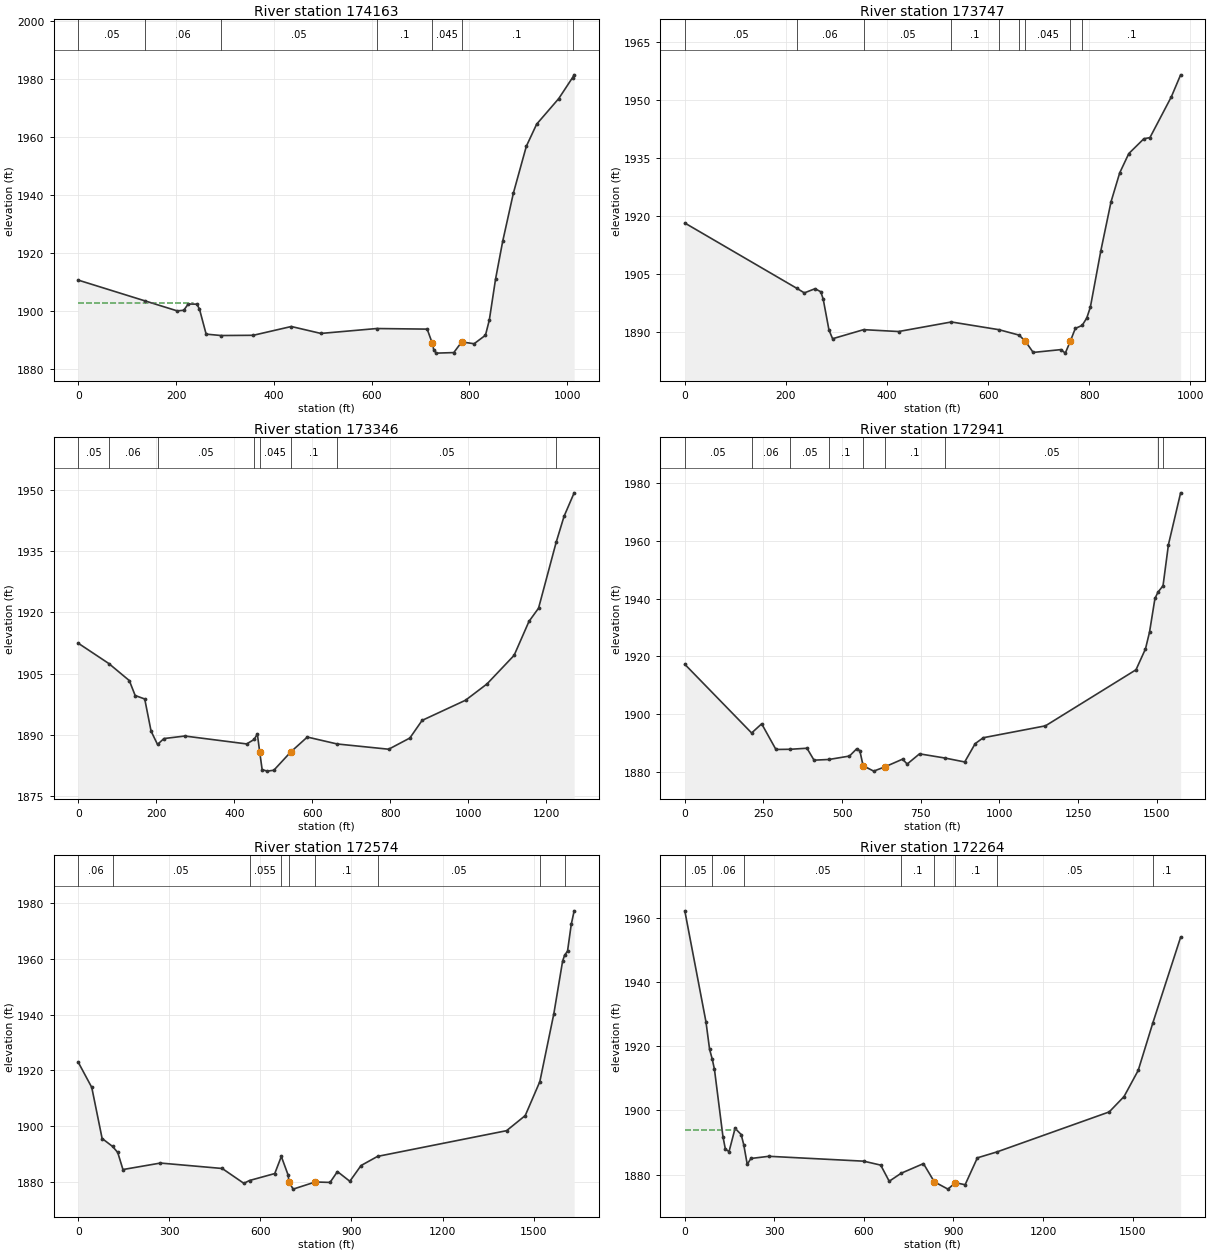
Type RM Length L Ch R = 1 ,174163  ,407.7,416.4,425.2
XS GIS Cut Line= 4
2447450.55948449547539.9608667312447921.00714606547803.027518304
2448210.95652115547958.563275803 2448343.4499442548020.009500988
#Sta/Elev= 30
       0 1910.61   136.21903.462   202.2 1900.01   215.6 1900.22   224.8 1902.38
   242.4 1902.32   247.7 1900.66   261.4 1891.99  292.05 1891.51   357.7 1891.59
   435.6 1894.62   496.1 1892.23  610.171893.922   713.5 1893.72   723.4 1889.08
   727.1 1886.49   732.2 1885.44   767.9 1885.63   784.1  1889.3   809.5 1888.68
   832.7 1891.61   840.6 1896.86   853.3 1910.94     868 1924.05   889.8 1940.62
   916.3 1956.78   937.4  1964.4   982.6 1973.23 1010.931980.487  1014.1 1981.41
#Mann= 7 ,-1 , 0
       0     .05       0   136.2     .06       0  292.05     .05       0
  610.17      .1       0   723.4    .045       0   784.1      .1       0
 1010.93      .1       0
#XS Ineff= 2 , 0
          235.07  1902.8
Permanent Ineff=
       F       F
Bank Sta=723.4,784.1
XS Rating Curve= 0 ,0
Exp/Cntr(USF)=0,0
Exp/Cntr=0.3,0.1

Type RM Length L Ch R = 1 ,173747  ,395,400.5,399.6
XS GIS Cut Line= 4
2447227.81691819547810.7082964522447728.98769235548110.258644228
2447901.80520069548275.3953744132448007.41590022548392.527241171
#Sta/Elev= 30
       0 1918.27  221.811901.381   236.4 1900.22   257.6  1901.3     269  1900.5
   273.7 1898.62   285.2  1890.6   292.3 1888.38  353.641890.723   422.8 1890.24
  527.191892.708  621.131890.718  661.141889.316  673.521887.735     689 1884.84
     744 1885.57   752.5 1884.66  762.441887.735   772.3 1891.04  785.811891.822
   794.9  1893.7   802.1 1896.54   822.9 1911.17     843 1923.77   860.1 1931.22
   878.1 1936.21   907.9 1940.04   919.9 1940.33   962.3 1950.89   980.6 1956.55
#Mann= 9 ,-1 , 0
       0     .05       0  221.81     .06       0  353.64     .05       0
  527.19      .1       0  621.13     .05       0  661.14      .1       0
  673.52    .045       0  762.44      .1       0  785.81      .1       0
Bank Sta=673.52,762.44
XS Rating Curve= 0 ,0
Exp/Cntr(USF)=0,0
Exp/Cntr=0.3,0.1

Type RM Length L Ch R = 1 ,173346  ,411.5,405,386.6
XS GIS Cut Line= 4
 2447145.2485531 548102.577866082447444.79890087548377.165684875
2447625.29718736548563.4245549672448116.86698883548916.740349779
#Sta/Elev= 30
       0 1912.43    78.11907.459   130.7 1903.27   145.7  1899.6   170.2 1898.75
   186.5 1890.85     2031887.584   219.5 1889.03   273.1 1889.65   431.6 1887.71
  450.771888.814   458.9 1890.18     4651885.725   471.2 1881.41   483.9 1881.03
   501.1 1881.24  544.441885.727     587  1889.4   663.5  1887.7   795.6 1886.41
   849.9 1889.16   881.3 1893.49   992.6 1898.44  1047.6 1902.44  1117.2 1909.47
  1155.2 1917.79  1179.8 1921.05 1224.941937.222  1245.3 1943.64  1271.1 1949.38
#Mann= 8 ,-1 , 0
       0     .05       0    78.1     .06       0     203     .05       0
  450.77      .1       0     465    .045       0  544.44      .1       0
   663.5     .05       0 1224.94      .1       0
Bank Sta=465,544.44
XS Rating Curve= 0 ,0
Exp/Cntr(USF)=0,0
Exp/Cntr=0.3,0.1

Type RM Length L Ch R = 1 ,172941  ,370.1,367.3,349.7
XS GIS Cut Line= 4
2446732.40672764548480.8561898742447164.45049847548699.758367095
2447406.39501013548830.331595613 2448166.7920468549127.961748852
#Sta/Elev= 30
       0 1917.29   212.41893.534   244.3  1896.7   289.6 1887.83  335.291887.898
   388.3 1888.26   410.7 1884.13  458.181884.371   523.3 1885.55     546 1888.03
   556.2 1887.44   566.7 1882.21   600.4 1880.34   636.9 1881.86     692 1884.47
   706.8 1882.79     746 1886.32  827.671884.852   889.6 1883.51   922.9 1889.85
   948.6 1891.89  1146.2    1896    1434 1915.39  1464.1 1922.62    1477 1928.43
  1494.2 1940.04 1503.791942.225 1519.891944.447  1537.1 1958.68  1575.8 1976.58
#Mann= 9 ,-1 , 0
       0     .05       0   212.4     .06       0  335.29     .05       0
  458.18      .1       0   566.7    .045       0   636.9      .1       0
  827.67     .05       0 1503.79      .1       0 1519.89      .1       0
Bank Sta=566.7,636.9
XS Rating Curve= 0 ,0
Exp/Cntr(USF)=0,0
Exp/Cntr=0.3,0.1

Type RM Length L Ch R = 1 ,172574  ,308.2,310,308.5
XS GIS Cut Line= 4
2446577.51103499548886.6573020332447089.56291153549082.943854706
2447396.79403745 549134.149042362448152.07055535549302.699451722
#Sta/Elev= 30
       0 1922.86    44.2  1913.9    78.4 1895.54  112.711892.699   129.8 1890.54
     147  1884.4   270.6 1886.73   474.1 1884.78   545.4 1879.45  564.011880.466
   647.2 1882.96  668.84  1889.1   691.5 1882.35  693.95 1880.05   707.7 1877.37
   780.7 1879.94   829.4 1879.78   853.7 1883.67   894.6 1880.19   931.5 1885.84
  985.851889.121    1411 1898.35  1472.5 1903.77 1520.651915.976  1566.8 1940.36
  1595.5 1959.12 1601.921961.278  1611.9 1962.82  1624.2 1972.46  1633.7 1977.27
#Mann= 9 ,-1 , 0
       0     .06       0  112.71     .05       0  564.01    .055       0
  668.84     .05       0  693.95    .045       0   780.7      .1       0
  985.85     .05       0 1520.65      .1       0 1601.92      .1       0
Bank Sta=693.95,780.7
XS Rating Curve= 0 ,0
Exp/Cntr(USF)=0,0
Exp/Cntr=0.3,0.1

Type RM Length L Ch R = 1 ,172264  ,301.3,306.8,308.4
XS GIS Cut Line= 4
2446440.96386791549255.7613630392447132.23390124549381.640782688
2447456.53342305549456.3150146842448075.26277387 549550.19119205
#Sta/Elev= 30
       0 1962.19    70.9 1927.61    83.1 1919.01   92.091915.946    99.4 1912.76
   127.8 1891.85     136 1887.91   148.2 1887.16   168.5 1894.42   188.8 1892.49
  197.471889.326   209.2 1883.19   221.4 1885.02   281.7  1885.7   599.5 1884.18
   656.4 1882.95   684.9 1877.92  724.761880.414   799.6 1883.42   835.9 1877.75
   881.7 1875.47   906.3 1877.47   939.2 1876.84   980.2 1885.22 1046.221887.076
    1422 1899.53  1471.7 1904.33  1519.1 1912.47 1567.88  1927.2  1661.2 1953.97
#Mann= 8 ,-1 , 0
       0     .05       0   92.09     .06       0  197.47     .05       0
  724.76      .1       0   835.9    .045       0   906.3      .1       0
 1046.22     .05       0 1567.88      .1       0
#XS Ineff= 2 , 0
          175.07 1893.87
Permanent Ineff=
       F       F
Bank Sta=835.9,906.3
XS Rating Curve= 0 ,0
Exp/Cntr(USF)=0,0
Exp/Cntr=0.3,0.1

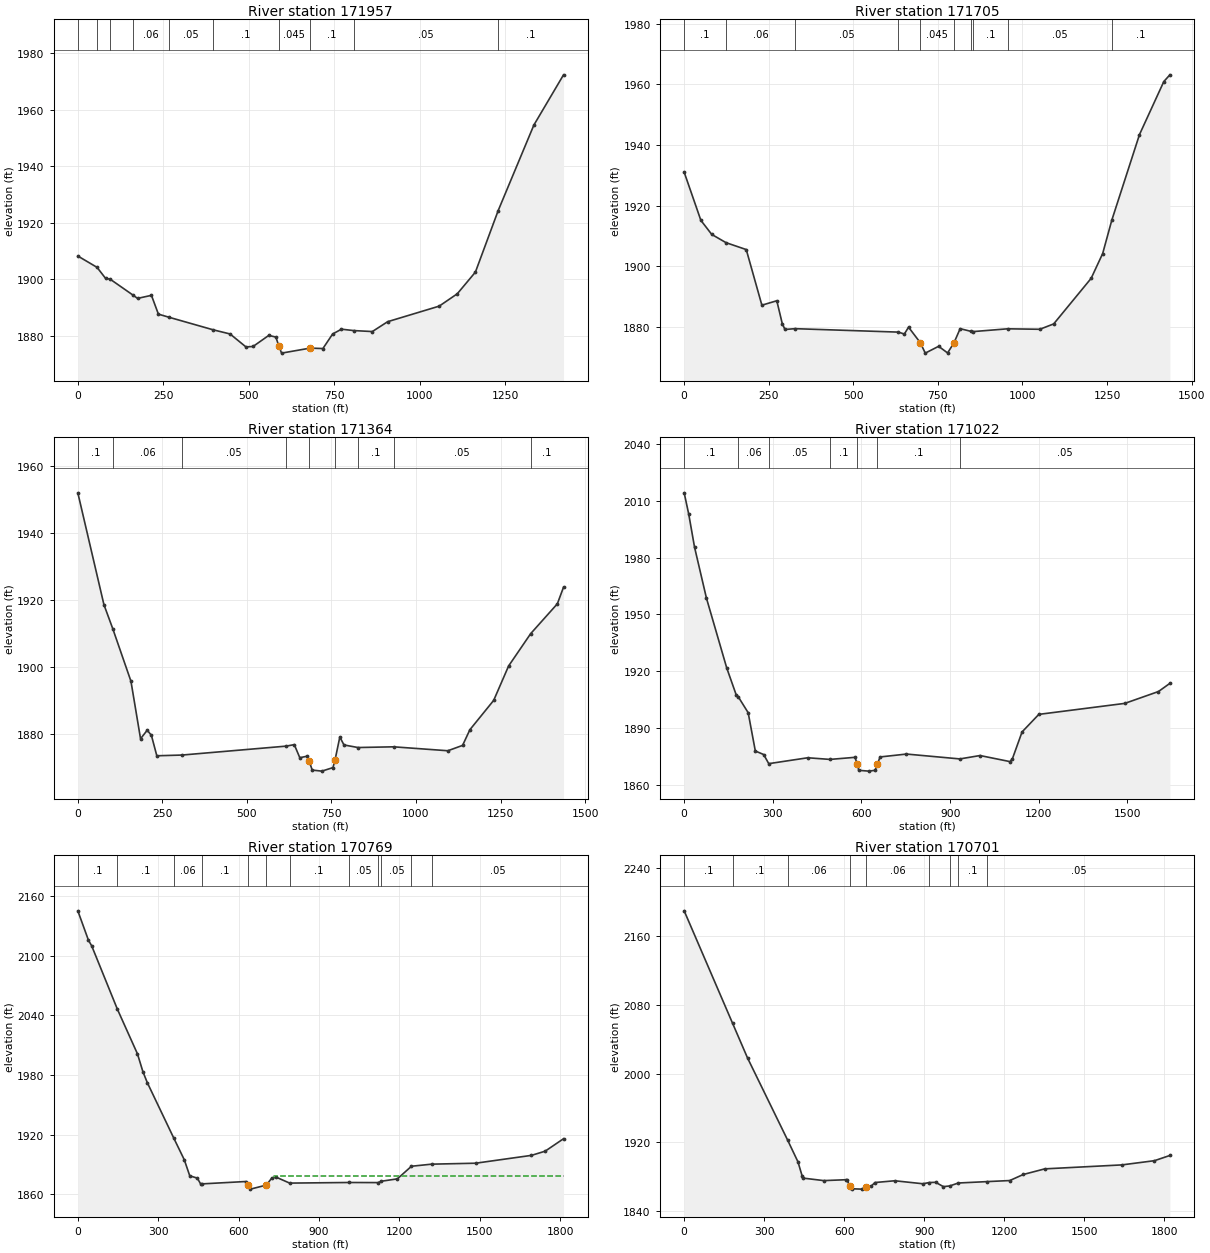
Type RM Length L Ch R = 1 ,171957  ,261.3,252.4,259.7
XS GIS Cut Line= 4
2446630.84977213549594.9957312472447113.03195587 549680.33771067
2447413.86243333549767.8132395792448019.79048724549883.024911801
#Sta/Elev= 30
       0 1908.19   56.111904.185    81.1 1900.29   94.551899.992   161.31894.361
   174.6  1893.2   215.2 1894.28   235.5 1887.63   266.51886.532  396.161882.069
     445 1880.62   491.5 1876.03   512.3  1876.2   558.1  1880.1   578.9 1879.53
   587.3 1876.44   595.6 1873.84   678.9 1875.61   716.4 1875.46   744.8  1880.6
   770.6 1882.31  806.09 1881.82   860.9 1881.47   905.7 1884.96  1056.3 1890.46
  1109.2 1894.83  1162.2  1902.5 1228.791924.262  1333.1 1954.51  1419.8 1972.28
#Mann= 10 ,-1 , 0
       0     .05       0   56.11     .06       0   94.55     .05       0
   161.3     .06       0   266.5     .05       0  396.16      .1       0
   587.3    .045       0   678.9      .1       0  806.09     .05       0
 1228.79      .1       0
Bank Sta=587.3,678.9
XS Rating Curve= 0 ,0
Exp/Cntr(USF)=0,0
Exp/Cntr=0.3,0.1

Type RM Length L Ch R = 1 ,171705  ,340.9,340.9,335.4
XS GIS Cut Line= 4
2446513.50455042549912.8946045992447157.83649506549955.565594311
2447450.13277459550028.106276821 2447936.5820573550075.044365503
#Sta/Elev= 30
       0 1931.05    49.3 1915.17    81.4 1910.52  123.751907.788   183.5 1905.51
   229.7 1887.16   273.8 1888.62   289.9  1881.1   297.9 1879.14  327.39 1879.41
  633.181878.276   650.8 1877.64   663.2  1879.9  698.021874.775   712.6 1871.34
   752.1 1873.59   778.6  1871.4   797.61874.776   815.7 1879.41  848.461878.504
  855.121878.455     9561879.365  1051.2 1879.21  1092.2 1880.98  1202.9 1896.02
  1236.9 1904.18 1264.071915.247  1345.8 1943.46  1417.7 1960.95  1435.6 1963.17
#Mann= 10 ,-1 , 0
       0      .1       0  123.75     .06       0  327.39     .05       0
  633.18      .1       0  698.02    .045       0   797.6      .1       0
  848.46     .05       0  855.12      .1       0     956     .05       0
 1264.07      .1       0
Bank Sta=698.02,797.6
XS Rating Curve= 0 ,0
Exp/Cntr(USF)=0,0
Exp/Cntr=0.3,0.1

Type RM Length L Ch R = 1 ,171364  ,336.2,342.1,349.1
XS GIS Cut Line= 4
2446485.76840711550239.3276758932447046.89192181550281.998665605
2447396.79403745550352.4057986292447913.11301296   550371.607744
#Sta/Elev= 30
       0 1951.96    77.2 1918.59  103.571911.346   157.1 1895.74   185.5 1878.58
   205.2 1881.13   217.6 1879.59   233.6  1873.5   307.91873.716  616.381876.381
   640.1 1876.83   656.4 1872.92   676.8 1873.35     684  1871.9   693.2 1869.23
   721.7 1868.92   754.4 1869.97   760.4 1872.15   774.8 1879.11     787 1876.73
  828.561875.962  933.981876.174  1094.2    1875  1137.8  1876.6  1159.4 1881.28
  1229.8 1890.04  1273.9  1900.3 1339.161909.944    1418 1918.84  1436.3  1923.8
#Mann= 9 ,-1 , 0
       0      .1       0  103.57     .06       0   307.9     .05       0
  616.38      .1       0     684    .045       0   760.4      .1       0
  828.56      .1       0  933.98     .05       0 1339.16      .1       0
Bank Sta=684,760.4
XS Rating Curve= 0 ,0
Exp/Cntr(USF)=0,0
Exp/Cntr=0.3,0.1

Type RM Length L Ch R = 1 ,171022  ,254.6,253.2,250.1
XS GIS Cut Line= 4
2446455.89871431550520.9562079912446978.61833828550587.096242044
  2447241.044925 550680.972419412448068.86212541 550811.11893803
#Sta/Elev= 30
       0  2014.2    15.4 2002.99    35.1 1985.51    75.4 1958.61     144  1921.8
   176.2 1907.52   182.71906.644   216.6 1898.16   240.8 1877.95     269 1876.09
  286.241871.274   418.2 1874.38  493.321873.515     578 1874.61  586.381870.848
   590.7 1867.75   624.7 1867.33     646 1867.75   653.41870.848     663 1874.81
   752.3 1876.34  932.991873.771  1001.2 1875.56  1102.7 1872.35    1111 1873.97
  1143.4 1888.01  1200.1 1897.28  1491.1 1903.08    1605 1909.34  1643.6 1913.65
#Mann= 7 ,-1 , 0
       0      .1       0   182.7     .06       0  286.24     .05       0
  493.32      .1       0  586.38    .045       0   653.4      .1       0
  932.99     .05       0
Bank Sta=586.38,653.4
XS Rating Curve= 0 ,0
Exp/Cntr(USF)=0,0
Exp/Cntr=0.5,0.3

Type RM Length L Ch R = 1 ,170769  ,68.7,67.5,67.7
XS GIS Cut Line= 4
 2446323.6186462550721.5098596362446839.93762171550813.252487516
2447426.66373025550983.9364463632448094.46471924550872.991873112
#Sta/Elev= 30
       0  2145.2    39.7 2115.56    51.6 2110.04  147.56 2046.22   222.6  2001.2
   242.9 1983.25   259.1 1972.37  358.011916.474   397.3 1894.64   417.6 1878.53
     446 1876.16   458.2 1870.33  463.231870.383   627.3 1872.78  634.411869.186
   644.2 1865.11  703.551869.184   723.1 1876.02   739.8 1877.17  790.391871.177
 1010.341871.784 1120.311871.684 1132.731873.054  1192.3 1875.44 1245.031888.142
 1320.411890.237  1484.3 1891.19  1692.8 1899.09  1743.8  1903.3  1812.4 1915.84
#Mann= 12 ,-1 , 0
       0      .1       0  147.56      .1       0  358.01     .06       0
  463.23      .1       0  634.41    .045       0  703.55     .06       0
  790.39      .1       0 1010.34     .05       0 1120.31      .1       0
 1132.73     .05       0 1245.03      .1       0 1320.41     .05       0
#XS Ineff= 2 , 0
                             733         1878.76
Permanent Ineff=
       F       F
Bank Sta=634.41,703.55
XS Rating Curve= 0 ,0
Exp/Cntr(USF)=0,0
Exp/Cntr=0.5,0.3

Type RM Length L Ch R = 1 ,170701  ,304.2,316.1,322.6
XS GIS Cut Line= 5
2446306.55025035550840.9886308462446911.13368669 550905.59425585
2447069.98785335550947.2609225062447417.86845961551040.060810655
2448096.02952001 550921.21925585
#Sta/Elev= 30
       0 2189.79   181.72058.432   237.5 2018.16  387.651922.428   426.6 1896.93
   442.7 1880.01   446.7 1877.94   523.2 1875.05   607.6 1876.09   611.8 1875.38
  619.971868.758   628.4 1865.53   665.5 1865.11   682.1 1867.39   700.5 1868.38
   715.1 1872.81   789.6 1874.87     895 1871.37  918.991872.812   942.8 1873.05
   971.8    1868  995.171868.801 1027.831872.255 1136.291873.889  1220.5 1875.12
  1271.3 1882.19  1351.8 1888.75  1640.8 1893.37    1763 1898.29  1820.8 1904.37
#Mann= 9 ,-1 , 0
       0      .1       0   181.7      .1       0  387.65     .06       0
  619.97    .045       0   682.1     .06       0  918.99      .1       0
  995.17     .06       0 1027.83      .1       0 1136.29     .05       0
Bank Sta=619.97,682.1
XS Rating Curve= 0 ,0
Exp/Cntr(USF)=0,0
Exp/Cntr=0.5,0.3

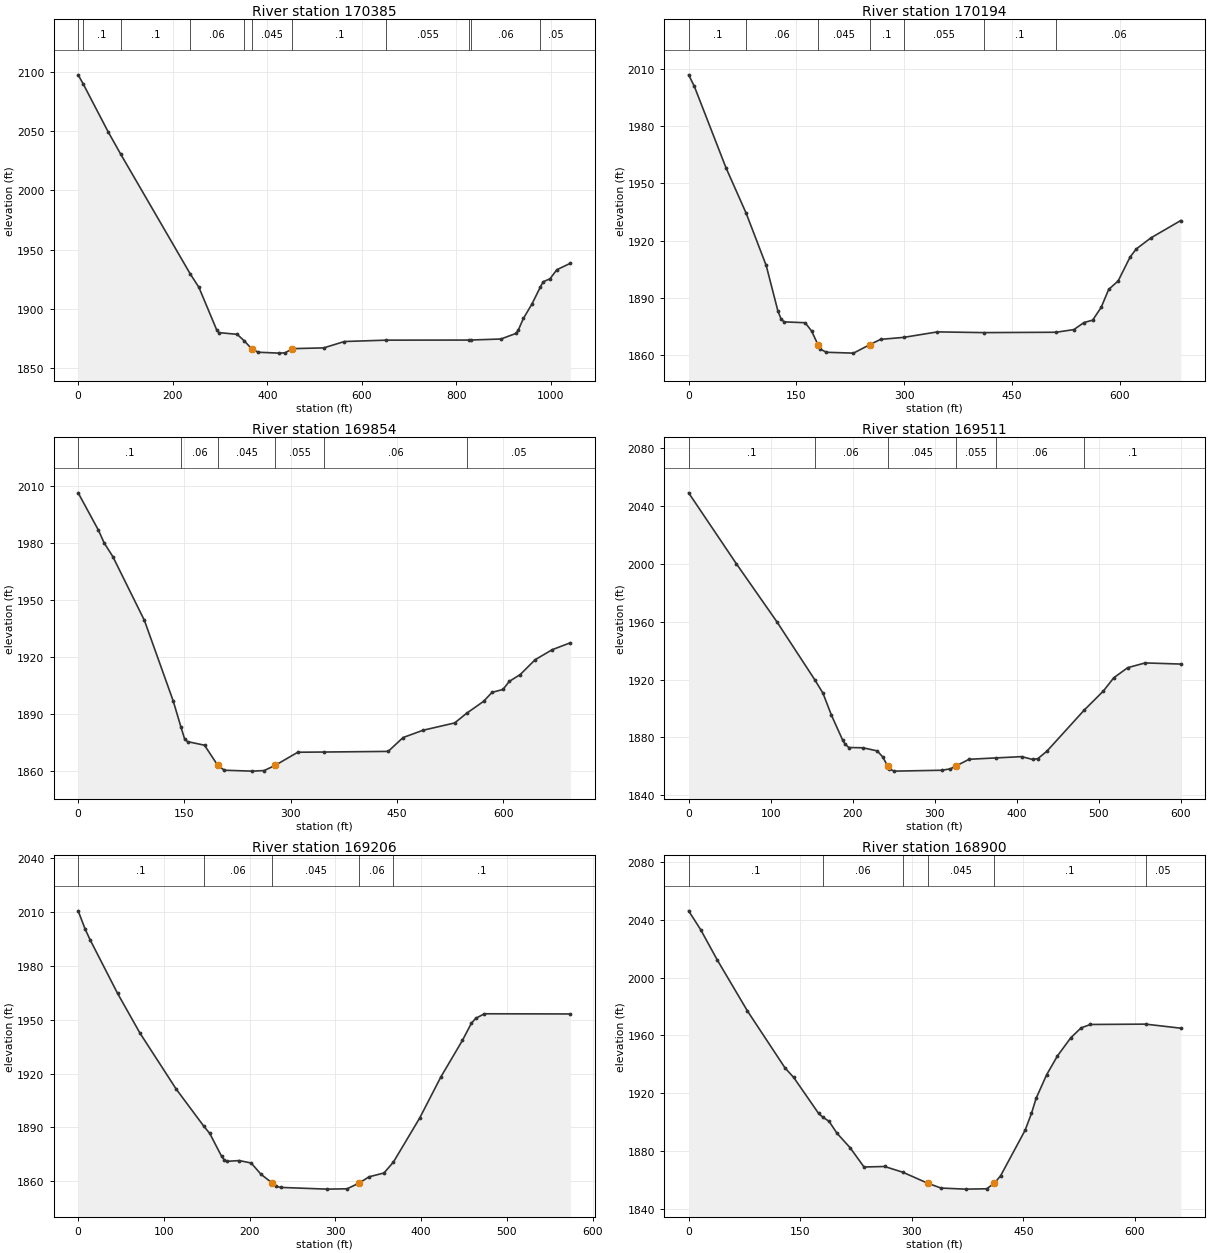
Type RM Length L Ch R = 1 ,170385  ,207.9,190.9,192.2
XS GIS Cut Line= 4
2446513.50455042551082.0797226992446820.73567634551188.757196979
2447364.79079517551442.6495857632447428.79727973551538.659312615
#Sta/Elev= 30
       0 2097.45   10.862089.641    63.4 2049.41   89.572030.849  236.591929.842
   255.4 1918.18   293.5 1881.83   297.7    1880   336.3 1878.55  351.011873.185
  367.071866.315   380.4 1863.46   424.9 1862.69   437.8 1862.94   453.2 1866.47
   519.4 1867.11   563.1 1872.49  652.051873.642  827.161873.716  831.491873.768
   894.2  1874.6   925.9  1879.3   930.7 1881.84   941.6 1891.91   959.5 1903.91
   977.5 1918.37   983.6 1922.89     998 1925.42  1012.4 1933.03    1041 1938.46
#Mann= 11 ,-1 , 0
       0      .1       0   10.86      .1       0   89.57      .1       0
  236.59     .06       0  351.01      .1       0  367.07    .045       0
   453.2      .1       0  652.05    .055       0  827.16     .05       0
  831.49     .06       0   977.5     .05       0
Bank Sta=367.07,453.2
XS Rating Curve= 0 ,0
Exp/Cntr(USF)=0,0
Exp/Cntr=0.3,0.1

Type RM Length L Ch R = 1 ,170194  ,345.4,339.7,323.9
XS GIS Cut Line= 4
2446694.85625669551391.4443981092446810.06792891551393.577947595
 2447226.1100786551525.8580157012447343.45530031551587.730950783
#Sta/Elev= 30
       0    2007     7.9 2001.01    51.9 1958.26   79.981934.358   107.9 1906.88
   124.3  1882.8   128.5  1878.9   132.7 1877.28   162.1 1876.82     171 1872.48
   179.8 1865.38   183.1    1863   191.5 1861.31   229.3 1860.86  252.291865.382
     267 1868.09  298.991869.123   346.1 1872.02  410.311871.632  510.871871.819
   535.7 1873.21   549.9 1876.93   561.9 1878.17   573.8 1884.92   584.2 1894.32
   597.4 1898.78     614 1911.34   622.6 1915.58     643 1921.39   684.5  1930.5
#Mann= 7 ,-1 , 0
       0      .1       0   79.98     .06       0   179.8    .045       0
  252.29      .1       0  298.99    .055       0  410.31      .1       0
  510.87     .06       0
Bank Sta=179.8,252.29
XS Rating Curve= 0 ,0
Exp/Cntr(USF)=0,0
Exp/Cntr=0.3,0.1

Type RM Length L Ch R = 1 ,169854  ,364.9,343.8,311
XS GIS Cut Line= 4
2446690.58915772551730.6787663172446839.93762171551756.281360144
2447164.23714352551762.6820086012447379.72564157551726.411667346
#Sta/Elev= 30
       0 2006.53    28.6 1986.87    36.7 1980.15    48.9 1972.97    93.5 1939.34
   134.1 1896.95  145.061883.155   150.3 1876.83   154.3 1875.53   178.3 1873.62
  197.031862.992   206.3 1860.44   245.6 1859.98   262.4 1860.28  277.821862.992
   309.9 1869.93  347.23 1870.04   437.4 1870.37   458.4 1877.66   486.5  1881.5
   531.2 1885.35  547.951890.408   571.9  1896.7   583.9 1901.45   599.4    1903
   608.2 1907.22   623.7 1910.84   644.7 1918.64   668.8 1923.93   694.4 1927.56
#Mann= 6 ,-1 , 0
       0      .1       0  145.06     .06       0  197.03    .045       0
  277.82    .055       0  347.23     .06       0  547.95     .05       0
Bank Sta=197.03,277.82
XS Rating Curve= 0 ,0
Exp/Cntr(USF)=0,0
Exp/Cntr=0.3,0.1

Type RM Length L Ch R = 1 ,169511  ,302.5,305.1,306.6
XS GIS Cut Line= 4
2446867.67376502552204.3267521172446967.95059085552131.786069607
2447234.64427655551944.0337148762447375.45854259551892.828527222
#Sta/Elev= 30
       0 2048.92    58.1 2000.03   107.5 1959.96  153.731919.872   163.7  1910.6
     174 1895.47   187.9 1877.96   190.8 1875.31   195.3 1873.08   212.5 1872.89
   229.8 1870.74   236.5 1866.62  242.471860.395   244.6 1858.28   250.4 1856.77
   308.2 1857.37   318.8 1858.32  326.171860.395   341.7 1864.94  374.61  1865.9
     406 1866.78   419.2 1864.83   425.6 1865.41   436.5 1870.47  482.071898.892
   505.4 1912.06   518.1 1921.22   535.1 1928.21   556.4 1931.48   599.8 1930.69
#Mann= 6 ,-1 , 0
       0      .1       0  153.73     .06       0  242.47    .045       0
  326.17    .055       0  374.61     .06       0  482.07      .1       0
Bank Sta=242.47,326.17
XS Rating Curve= 0 ,0
Exp/Cntr(USF)=0,0
Exp/Cntr=0.3,0.1

Type RM Length L Ch R = 1 ,169206  ,301.9,305.7,307
XS GIS Cut Line= 4
2447102.36420844552389.9455573632447219.70943015552315.271325367
2447441.59857665552157.3886634342447569.61154578552057.111837612
#Sta/Elev= 30
       0 2010.72     8.3 2000.36    14.1 1994.42    45.9 1964.76      72  1942.6
   114.2 1911.41  146.261890.792   153.5 1886.55   167.4 1873.72   170.2 1871.94
   173.1 1871.01     188 1871.44   201.8 1870.09   213.2 1863.81  226.341858.922
   231.2 1857.03   236.1 1856.48   290.1 1855.52   313.6  1855.7  327.771858.923
   339.2 1862.38   356.7 1864.53  367.691870.633   398.1    1895     423 1918.08
   448.2 1938.52   458.6 1948.02   463.7 1950.78   473.8 1953.31     574 1953.21
#Mann= 5 ,-1 , 0
       0      .1       0  146.26     .06       0  226.34    .045       0
  327.77     .06       0  367.69      .1       0
Bank Sta=226.34,327.77
XS Rating Curve= 0 ,0
Exp/Cntr(USF)=0,0
Exp/Cntr=0.3,0.1

Type RM Length L Ch R = 1 ,168900  ,264.9,267.4,270
XS GIS Cut Line= 4
2447213.78680604552660.200361856 2447373.1282552552562.644372575
2447656.04062411552387.0435918682447769.85594494552302.495067824
#Sta/Elev= 30
       0 2046.22    16.2 2033.19    38.6 2012.17    79.1 1976.94   129.6 1937.57
   141.3 1930.96   174.7 1906.13  180.251903.553   188.7 1900.69   199.4 1892.42
     217 1882.44   235.8 1869.05   263.4 1869.41  287.831865.455  321.341857.837
   339.4 1854.48   372.3 1853.75   400.6 1853.99  410.981857.837   419.4 1863.02
   452.2 1894.35   460.9 1906.15     467 1916.43   481.2  1932.8   495.7 1945.81
   513.6 1958.37   527.6 1965.29   540.2 1967.62  614.211967.862   661.6 1965.05
#Mann= 6 ,-1 , 0
       0      .1       0  180.25     .06       0  287.83      .1       0
  321.34    .045       0  410.98      .1       0  614.21     .05       0
Bank Sta=321.34,410.98
XS Rating Curve= 0 ,0
Exp/Cntr(USF)=0,0
Exp/Cntr=0.3,0.1