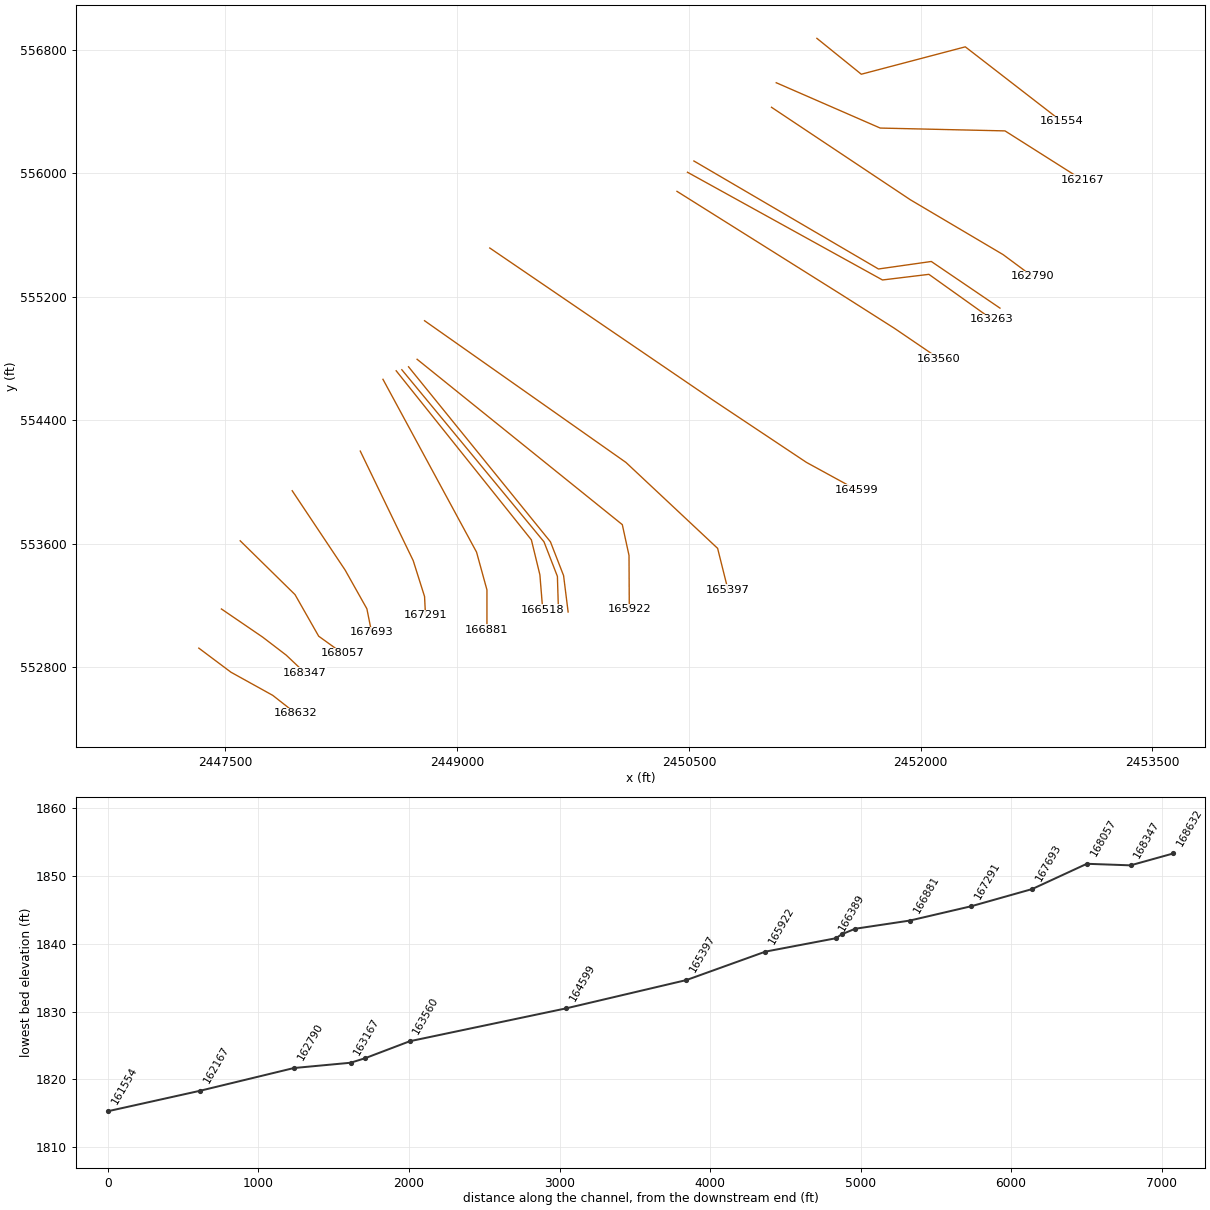
HEC-RAS study SFSBPOTOMC.prj: SFSBPOTOMC

--- SFSBPOTOMC.g01 (geometry) --- (continued)

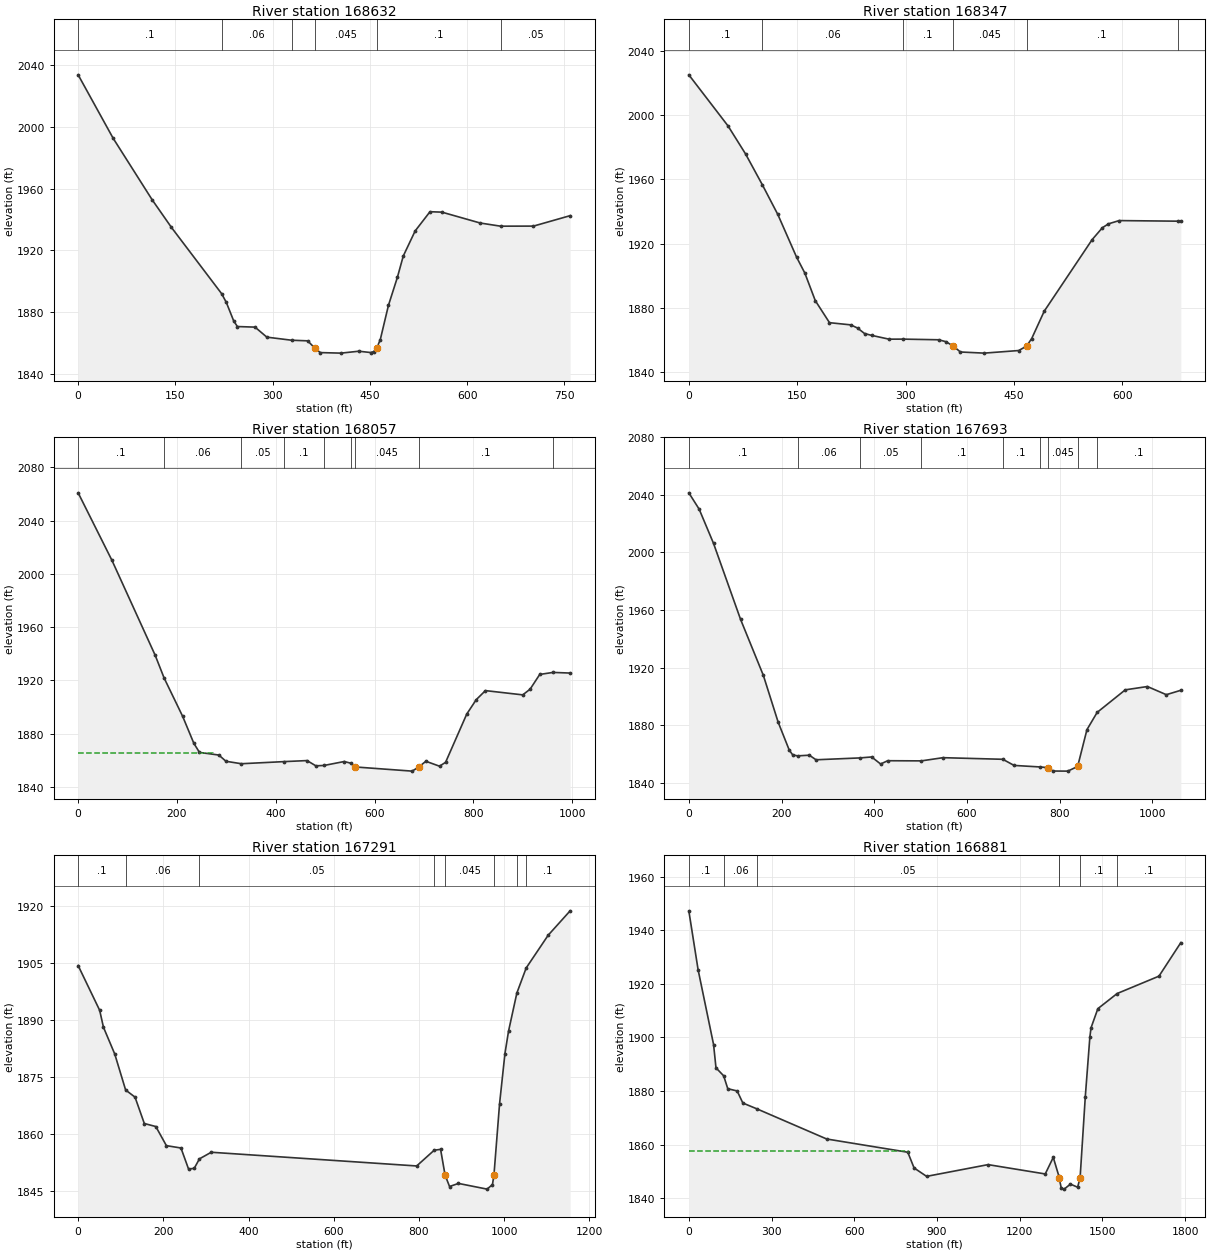
Type RM Length L Ch R = 1 ,168632  ,292.6,285.1,276.9
XS GIS Cut Line= 4
2447327.60212687552923.6015329162447535.72157067552767.511950066
2447805.62647434552617.9260998342447955.21232458552500.858912697
#Sta/Elev= 30
       0  2033.9    53.9 1992.79   114.2 1952.78   143.9 1934.87  221.221891.917
   228.5 1886.23   239.9 1874.19   245.6 1870.56   272.8 1870.18     291 1863.68
  329.06 1861.69     354 1861.28  364.521856.738   373.4 1853.66   405.4 1853.31
   432.8 1854.55   451.2 1853.69   455.7 1854.25  460.581856.742   465.9 1862.01
   478.5 1884.28   492.3 1902.47   501.4 1916.35   519.7 1932.59   542.6 1945.07
   560.9  1944.8   620.1 1937.73  651.41 1935.69   702.2 1935.74   758.7 1942.51
#Mann= 6 ,-1 , 0
       0      .1       0  221.22     .06       0  329.06      .1       0
  364.52    .045       0  460.58      .1       0  651.41     .05       0
Bank Sta=364.52,460.58
XS Rating Curve= 0 ,0
Exp/Cntr(USF)=0,0
Exp/Cntr=0.3,0.1

Type RM Length L Ch R = 1 ,168347  ,323.3,290.2,273.1
XS GIS Cut Line= 4
2447473.93611079553177.2471050482447740.58914816552995.142591723
 2447893.4268647552878.0754045852448013.74591814552764.260083757
#Sta/Elev= 30
       0 2025.37    54.3 1993.43    78.5 1975.99  101.711956.744   123.2 1938.14
   149.1 1911.55   160.6 1901.53     175 1884.37   194.7 1870.57   224.1  1869.2
   233.5 1867.23   243.2  1863.8   252.9 1862.65   277.1 1860.27  296.541860.298
   345.8 1859.89   355.8 1858.71  366.191855.905   375.9 1852.26   408.8 1851.55
   456.6 1853.17   467.41855.903   474.6 1860.65   491.9 1877.71   558.2  1922.4
   572.4 1929.86   580.9 1932.31   595.7 1934.33  676.611933.963     681 1933.95
#Mann= 6 ,-1 , 0
       0      .1       0  101.71     .06       0  296.54      .1       0
  366.19    .045       0   467.4      .1       0  676.61     .05       0
Bank Sta=366.19,467.4
XS Rating Curve= 0 ,0
Exp/Cntr(USF)=0,0
Exp/Cntr=0.3,0.1

Type RM Length L Ch R = 1 ,168057  ,380.9,363.8,364.5
XS GIS Cut Line= 4
2447595.58316828 553618.915846512447950.48285789553270.135117069
2448103.45686203553000.9008697812448256.43086617  552890.7595868
#Sta/Elev= 30
       0 2060.83    68.5 2010.06   155.9 1938.84     174 1921.74   211.6 1892.88
   234.2 1872.66   245.6 1865.83   284.8 1863.86   299.2 1859.17  330.391857.336
  417.361858.936   463.3  1859.7   481.1 1855.77  497.621856.028   538.6    1859
  551.561857.753  561.371854.892     676 1851.78  689.481854.892   703.8 1859.19
   731.4 1855.49   743.7 1858.39   786.6 1894.67   805.8 1905.48   824.4 1912.26
   899.9 1909.06   914.8 1913.35   934.3 1924.41  961.161925.925   995.8 1925.45
#Mann= 9 ,-1 , 0
       0      .1       0     174     .06       0  330.39     .05       0
  417.36      .1       0  497.62     .05       0  551.56      .1       0
  561.37    .045       0  689.48      .1       0  961.16      .1       0
#XS Ineff= 2 , 0
           272.6 1865.22
Permanent Ineff=
       F       F
Bank Sta=561.37,689.48
XS Rating Curve= 0 ,0
Exp/Cntr(USF)=0,0
Exp/Cntr=0.3,0.1

Type RM Length L Ch R = 1 ,167693  ,408.4,402.7,397.5
XS GIS Cut Line= 4
2447932.12597739553943.2207352882448274.78774666553429.228081375
2448415.52383047553178.350714584 2448446.1186313553025.376710444
#Sta/Elev= 30
       0 2041.35    22.3 2029.99    53.3 2006.22   111.7 1953.39   160.8 1914.54
   192.7 1882.07   216.7 1862.62   224.2  1859.3  234.581858.656     260 1859.11
   274.4 1855.93  369.32 1857.23   394.4 1857.89   413.8 1852.99     429 1855.28
  501.641855.168   548.4 1857.39  677.371856.272   701.7 1852.01   756.91850.964
   775.2 1850.48   785.5 1848.12   817.6 1848.05  838.831851.293   858.9 1876.87
  880.87 1888.83   941.6 1904.51   989.3 1906.81  1030.1 1901.15  1061.4 1904.19
#Mann= 9 ,-1 , 0
       0      .1       0  234.58     .06       0  369.32     .05       0
  501.64      .1       0  677.37      .1       0   756.9      .1       0
   775.2    .045       0  838.83      .1       0  880.87      .1       0
Bank Sta=775.2,838.83
XS Rating Curve= 0 ,0
Exp/Cntr(USF)=0,0
Exp/Cntr=0.3,0.1

Type RM Length L Ch R = 1 ,167291  ,413.9,409.3,405.8
XS GIS Cut Line= 4
2448372.69110931554200.2170622442448715.35287859553490.417683031
2448788.78040058553257.8971967382448794.89936074553135.517993425
#Sta/Elev= 30
       0  1904.4    50.5 1892.62    59.4 1888.16    85.9 1881.11  111.441871.631
   133.5 1869.75   155.3 1862.81   182.3 1862.01   207.1 1856.98   241.3 1856.36
   259.1 1850.83   272.4    1851  284.681853.503   312.4 1855.24   794.5 1851.63
  835.621855.779   850.6    1856   861.11849.236   871.6 1846.22   892.6 1847.03
   959.7 1845.53   972.3 1846.72  975.831849.238     989 1868.01  1001.6 1881.21
    1010  1887.1 1029.621897.179 1051.491903.771  1103.1 1912.39  1154.6 1918.81
#Mann= 8 ,-1 , 0
       0      .1       0  111.44     .06       0  284.68     .05       0
  835.62      .1       0   861.1    .045       0  975.83      .1       0
 1029.62      .1       0 1051.49      .1       0
Bank Sta=861.1,975.83
XS Rating Curve= 0 ,0
Exp/Cntr(USF)=0,0
Exp/Cntr=0.3,0.1

Type RM Length L Ch R = 1 ,166881  ,363.5,363.8,362
XS GIS Cut Line= 4
2448519.54615329554665.2580348322449125.32320969553545.488324522
2449192.63177151553300.7299178972449192.63177151553043.733590941
#Sta/Elev= 30
       0 1947.23    33.6 1925.28    89.7 1897.36    98.5 1888.66  126.341885.682
   141.2 1880.87   175.3 1880.03   195.9 1875.53  248.851873.269   499.9 1862.11
     794 1857.17   816.8 1851.31   862.2 1848.17  1085.1 1852.55  1292.4 1849.07
  1321.5 1855.25 1341.451848.394 1342.831847.634  1350.5 1843.78    1361 1843.41
  1383.8 1845.28  1409.8 1844.12  1418.81847.634  1437.6 1877.83  1454.2 1900.13
  1458.4 1903.58  1483.2 1910.73 1553.131916.378  1704.8 1922.86    1784 1935.36
#Mann= 7 ,-1 , 0
       0      .1       0  126.34     .06       0  248.85     .05       0
 1341.45      .1       0 1342.83    .045       0  1418.8      .1       0
 1553.13      .1       0
#XS Ineff= 2 , 0
          794.52 1857.71
Permanent Ineff=
       F       F
Bank Sta=1342.83,1418.8
XS Rating Curve= 0 ,0
Exp/Cntr(USF)=0,0
Exp/Cntr=0.3,0.1

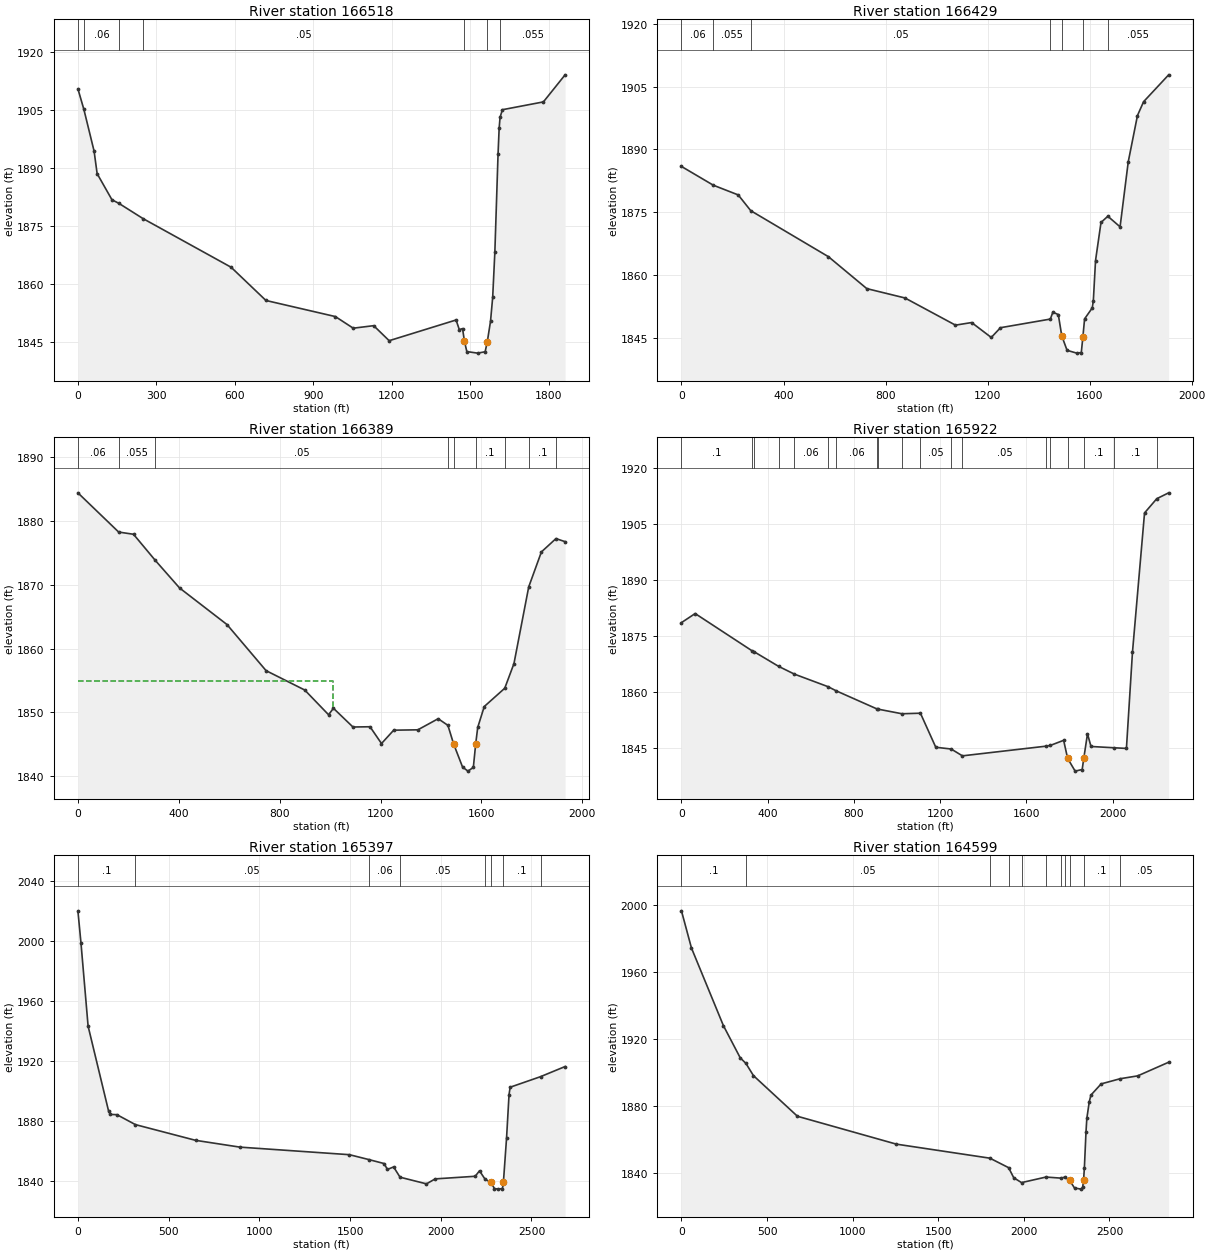
Type RM Length L Ch R = 1 ,166518  ,81.9,89,93.6
XS GIS Cut Line= 4
2448605.21159561554720.3286763222449480.22289929553625.034806675
2449535.29354078553398.6332805472449553.65042128553172.231754419
#Sta/Elev= 30
       0 1910.46   22.841905.138    61.9 1894.36    73.5 1888.55   130.2  1881.8
  156.841880.868  248.641876.955   585.5 1864.38   718.6  1855.8     984 1851.64
  1052.3 1848.64  1130.4 1849.29  1189.6 1845.41  1445.3 1850.76  1457.6 1848.28
    1470 1848.53  1477.5 1845.21  1486.4  1842.6  1527.6  1842.2  1556.4 1842.55
  1564.6 1845.12    1577 1850.44  1585.2 1856.59  1593.5 1868.22  1605.8 1893.69
  1609.9 1900.22 1613.391903.072  1622.3 1905.06  1779.1 1907.08    1862 1914.07
#Mann= 7 ,-1 , 0
       0      .1       0   22.84     .06       0  156.84    .055       0
  248.64     .05       0  1477.5    .045       0  1564.6      .1       0
 1613.39    .055       0
Bank Sta=1477.5,1564.6
XS Rating Curve= 0 ,0
Exp/Cntr(USF)=0,0
Exp/Cntr=0.3,0.1

Type RM Length L Ch R = 1 ,166429  ,38.9,39.2,39.3
XS GIS Cut Line= 4
2448641.68924221554727.1220336112449561.82813111553612.538700268
2449648.63368669553388.5803669542449655.57813114553164.622033626
#Sta/Elev= 30
       0 1885.95  124.831881.469   222.5 1879.15  271.641875.386   576.1  1864.4
   726.5 1856.78     876 1854.55    1074 1848.06  1137.4 1848.68  1214.3 1845.12
  1250.4 1847.45 1445.921849.511  1455.7 1851.16  1477.1 1850.58  1490.6  1845.5
  1511.4 1842.05  1549.3 1841.38  1567.2 1841.52 1573.431845.276  1580.1 1849.56
  1610.1 1852.17  1614.4 1853.92    1623 1863.49  1644.4 1872.57 1671.181874.057
  1719.2 1871.53  1751.2 1887.05  1787.3  1898.1  1811.3  1901.41909.579 1907.82
#Mann= 7 ,-1 , 0
       0     .06       0  124.83    .055       0  271.64     .05       0
 1445.92      .1       0  1490.6    .045       0 1573.43      .1       0
 1671.18    .055       0
Bank Sta=1490.6,1573.43
XS Rating Curve= 0 ,0
Exp/Cntr(USF)=0,0
Exp/Cntr=0.3,0.1

Type RM Length L Ch R = 1 ,166389  ,477.5,467.4,461.7
XS GIS Cut Line= 4
2448685.09202001554746.219255835 2449603.4947978553612.538700268
2449688.56424221553393.7887002682449718.07813114553157.677589163
#Sta/Elev= 30
       0 1884.45  161.591878.298   220.5 1877.95  306.89 1873.85     403 1869.53
   591.1 1863.79   746.1 1856.56   899.4 1853.52   993.9 1849.64  1013.1 1850.66
  1090.5 1847.72  1158.2 1847.76  1203.7 1845.13    1252 1847.22  1347.9 1847.28
  1428.4 1849.02 1466.991847.981 1489.661845.062  1525.2 1841.43  1546.6  1840.8
  1567.9 1841.39 1577.12 1845.06  1585.2 1847.65  1611.1 1850.93  1692.41853.802
  1728.9 1857.67 1787.391869.694  1837.7 1875.18  1895.41877.2711931.663 1876.79
#Mann= 9 ,-1 , 0
       0     .06       0  161.59    .055       0  306.89     .05       0
 1466.99      .1       0 1489.66    .045       0 1577.12      .1       0
  1692.4    .055       0 1787.39      .1       0  1895.4    .055       0
#XS Ineff= 2 , 0
          1010.3    1855
Permanent Ineff=
       F       F
Bank Sta=1489.66,1577.12
XS Rating Curve= 0 ,0
Exp/Cntr(USF)=0,0
Exp/Cntr=0.3,0.1

Type RM Length L Ch R = 1 ,165922  ,501.8,524.6,541.5
XS GIS Cut Line= 4
2448740.64757556554794.8303669542450068.77257556553723.649811402
2450112.17535335553523.9970336112450113.91146445553175.038700268
#Sta/Elev= 30
       0 1878.65    63.6 1881.08  329.461871.017  336.591870.857   450.91866.912
  524.171864.831  679.521861.479  718.881860.327  908.141855.472  913.581855.428
 1022.451854.214 1108.29 1854.36  1179.5 1845.23 1251.081844.755    13031842.927
 1692.411845.533 1711.151845.731  1772.5 1847.09 1790.921842.258  1825.8 1838.83
  1858.5 1839.26  1865.91842.258  1883.1 1848.84  1899.4 1845.44 2006.81 1845.09
  2063.7 1844.92  2091.7  1870.7  2147.7 1908.06 2204.361911.8742259.545 1913.45
#Mann= 19 ,-1 , 0
       0      .1       0  329.46    .055       0  336.59     .06       0
   450.9     .05       0  524.17     .06       0  679.52     .05       0
  718.88     .06       0  908.14     .05       0  913.58     .06       0
 1022.45    .055       0 1108.29     .05       0 1251.08    .055       0
    1303     .05       0 1692.41      .1       0 1711.15     .05       0
 1790.92    .045       0  1865.9      .1       0 2006.81      .1       0
 2204.36     .05       0
Bank Sta=1790.92,1865.9
XS Rating Curve= 0 ,0
Exp/Cntr(USF)=0,0
Exp/Cntr=0.3,0.1

Type RM Length L Ch R = 1 ,165397  ,788.9,798.6,798.2
XS GIS Cut Line= 4
2448788.78040058555044.6335651012450092.11891585554126.789540257
2450685.65805192553569.9641651852450752.96661374553300.729917897
#Sta/Elev= 30
       0 2020.27    17.1 1998.61    56.2 1943.37   168.7 1886.92   178.5 1884.47
   215.1  1884.3  316.84 1877.68   648.6 1867.19   892.6 1862.66  1496.7 1857.61
 1602.791854.384  1687.5 1851.71  1706.2 1847.78  1740.2 1849.44 1775.661842.597
  1921.3 1838.15  1969.4 1841.47    2190 1843.21  2213.7 1846.86    22451841.125
  2277.8  1839.2  2295.5 1835.03  2317.5 1834.64  2340.1 1835.04 2345.431839.226
  2362.8 1868.71  2376.5  1897.7  2382.6 1902.61 2550.041909.654  2685.5 1916.41
#Mann= 8 ,-1 , 0
       0      .1       0  316.84     .05       0 1602.79     .06       0
 1775.66     .05       0    2245      .1       0  2277.8    .045       0
 2345.43      .1       0 2550.04     .05       0
Bank Sta=2277.8,2345.43
XS Rating Curve= 0 ,0
Exp/Cntr(USF)=0,0
Exp/Cntr=0.3,0.1

Type RM Length L Ch R = 1 ,164599  ,1037.4,1039.2,1039.6
XS GIS Cut Line= 4
  2449210.988652555515.7934978542450655.06325109554530.640911188
2451260.84030749554126.7895402572451585.14519627553949.339695454
#Sta/Elev= 30
       0 1996.73    58.4 1974.53   245.1 1928.13   343.5 1908.88  376.341905.611
   420.7 1898.26   677.6 1873.99  1255.5 1857.34 1801.741848.956 1910.871843.291
    1941 1837.26 1986.581834.365 2129.12 1837.68 2218.551837.025 2238.25 1837.62
  2266.9 1835.82  2266.9 1835.81  2295.9 1831.12  2336.1 1830.47  2343.8 1831.77
 2348.631835.636  2353.5 1843.11  2363.1 1864.87  2367.9 1872.73  2382.2 1882.75
  2391.9 1886.66  2451.5 1893.34 2562.531896.423  2665.3 1898.14  2845.8 1906.28
#Mann= 11 ,-1 , 0
       0      .1       0  376.34     .05       0 1801.74     .06       0
 1910.87    .055       0 1986.58     .05       0 2129.12      .1       0
 2218.55     .05       0 2238.25      .1       0  2266.9    .045       0
 2348.63      .1       0 2562.53     .05       0
Bank Sta=2266.9,2348.63
XS Rating Curve= 0 ,0
Exp/Cntr(USF)=0,0
Exp/Cntr=0.3,0.1

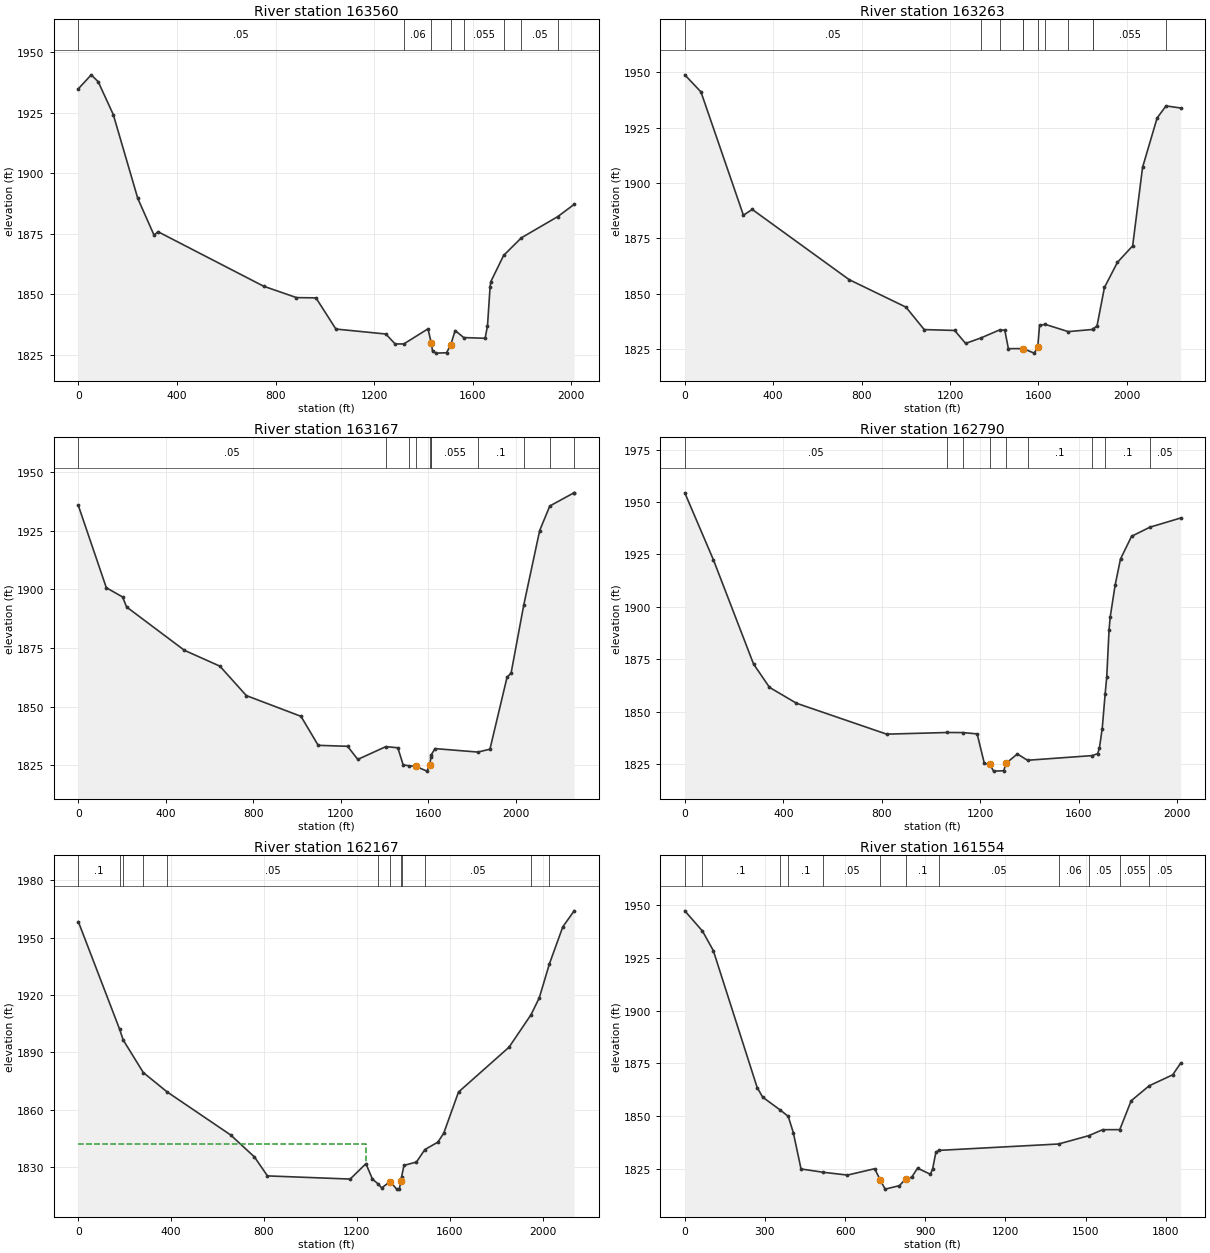
Type RM Length L Ch R = 1 ,163560  ,285.7,296.4,326.3
XS GIS Cut Line= 4
 2450422.5427648555882.9311077922451493.36079378555209.845489573
2451829.90360289554995.6818837762452117.49473068554799.875158476
#Sta/Elev= 30
       0 1934.97    52.4 1940.74    80.6 1937.88     142 1924.25   241.2 1889.62
   307.3 1874.39   323.3 1875.84   751.5 1853.31     885 1848.59   964.1 1848.48
  1044.9 1835.58  1247.6 1833.53  1285.3 1829.41 1320.481829.419  1418.6 1835.67
 1432.16 1829.62  1437.1 1826.39  1451.3 1825.62  1493.8 1825.78 1511.051829.072
  1528.7 1834.97 1563.671832.054  1650.3 1831.76    1660 1836.86  1670.6 1853.17
  1673.5  1855.2 1725.561866.049 1797.451873.324 1944.791882.078  2011.6 1887.15
#Mann= 8 ,-1 , 0
       0     .05       0 1320.48     .06       0 1432.16    .045       0
 1511.05    .035       0 1563.67    .055       0 1725.56     .06       0
 1797.45     .05       0 1944.79     .06       0
Bank Sta=1432.16,1511.05
XS Rating Curve= 0 ,0
Exp/Cntr(USF)=0,0
Exp/Cntr=0.5,0.3

Type RM Length L Ch R = 1 ,163263  ,93.4,96.4,92.9
XS GIS Cut Line= 4
2450490.64757556556006.6359225062451752.80035332555308.719255835
2452053.14757559555345.1775891632452459.39757559555055.247033611
#Sta/Elev= 30
       0 1948.83    73.2  1941.1   265.2 1885.43   305.3 1888.02   743.4 1856.34
  1001.1 1843.88  1083.4 1833.76  1221.3 1833.36  1270.8 1827.51  1339.91829.971
 1424.871833.613  1448.2 1833.45  1464.4 1825.15 1528.611825.156  1532.2 1825.14
  1581.2 1823.12  1597.3 1825.69  1605.4 1835.73    16321836.081 1735.38 1832.84
  1845.51833.809  1849.3 1834.05  1865.8 1835.53  1899.1 1852.77  1958.1 1864.16
  2026.9 1871.58  2071.6 1907.02  2137.6 1929.36 2177.871934.785  2243.9 1933.85
#Mann= 11 ,-1 , 0
       0     .05       0  1339.9     .06       0 1424.87    .055       0
 1528.61    .035       0  1532.2    .045       0  1597.3    .055       0
    1632    .035       0 1735.38    .055       0  1845.5      .1       0
  1849.3    .055       0 2177.87      .1       0
Bank Sta=1532.2,1597.3
XS Rating Curve= 0 ,0
Exp/Cntr(USF)=0,0
Exp/Cntr=0.5,0.3

Type RM Length L Ch R = 1 ,163167  ,396.1,376.8,351.3
XS GIS Cut Line= 4
2450532.31424224556079.5525891782451726.75868666555379.899811387
2452068.77257556555428.5109225062452513.21701998555126.427589163
#Sta/Elev= 30
       0 1935.73     128 1900.66   202.2 1896.72   220.7 1892.46   484.9 1873.98
   647.2 1867.22   768.2 1854.66    1018 1845.82  1096.8 1833.45  1231.3 1833.04
  1277.6 1827.44 1405.991832.897  1460.8 1832.41  1485.3 1825.11 1510.011824.769
  1542.6 1824.48  1594.3 1822.45  1606.5 1824.94  1612.41828.577 1614.031829.434
  1630.7 1832.06 1827.011830.578    1882 1831.81  1960.3  1862.5  1978.8 1864.29
 2036.981893.447  2109.5 1925.06 2155.751935.513 2265.331941.105  2267.1 1941.13
#Mann= 11 ,-1 , 0
       0     .05       0 1405.99     .06       0 1510.01    .055       0
  1542.6    .045       0  1606.5    .055       0  1612.4     .06       0
 1614.03    .055       0 1827.01      .1       0 2036.98    .055       0
 2155.75      .1       0 2265.33     .05       0
Bank Sta=1542.6,1606.5
XS Rating Curve= 0 ,0
Exp/Cntr(USF)=0,0
Exp/Cntr=0.5,0.3

Type RM Length L Ch R = 1 ,162790  ,609.7,623.1,637.5
XS GIS Cut Line= 4
2451034.43878136556427.5185625322451933.92592571555827.860466301
2452533.58402194555472.9607766952452723.27178707555332.224692885
#Sta/Elev= 30
       0 1954.37   116.5 1922.36   279.2 1872.77   343.9 1861.62   453.5 1854.05
   819.9  1839.3 1067.041840.093 1129.421840.046  1187.5 1839.43  1216.7 1825.36
    1240 1824.85    1240 1824.84    1254 1821.67  1295.5 1821.85  1305.1 1825.44
    1351 1829.85 1392.151826.853 1654.881829.073    1677    1830  1683.9 1832.46
  1695.6 1841.96 1707.42 1858.36  1714.1 1866.78  1723.4 1889.06  1728.1  1895.2
  1748.1 1910.38  1769.9 1922.83  1814.9 1933.65 1889.291937.984  2014.1 1942.36
#Mann= 9 ,-1 , 0
       0     .05       0 1067.04     .06       0 1129.42     .05       0
    1240    .045       0  1305.1    .055       0 1392.15      .1       0
 1654.88      .1       0 1707.42      .1       0 1889.29     .05       0
Bank Sta=1240,1305.1
XS Rating Curve= 0 ,0
Exp/Cntr(USF)=0,0
Exp/Cntr=0.3,0.1

Type RM Length L Ch R = 1 ,162167  ,611.5,612.7,604.3
XS GIS Cut Line= 4
2451065.03358219556586.6115268392451738.11920041556292.901438889
2452545.82194227556274.5445583922453047.57667585555956.358629779
#Sta/Elev= 30
       0 1958.41  177.391902.213  193.291896.441  279.911879.372  382.441869.247
   656.5 1846.67     759 1835.16   814.8 1825.25  1171.2 1823.59  1239.1 1831.63
  1267.1 1823.63  1292.61820.921  1307.2 1818.93  1343.3 1822.31  1371.6 1818.32
  1383.2 1818.49  1390.41822.728 1392.881824.796  1403.2 1830.77  1456.8  1832.5
 1493.151839.056  1549.1 1842.91  1574.6 1847.65  1638.1 1869.17    1856 1892.68
 1950.591909.678  1986.2 1918.54  2029.51936.209  2087.6 1955.73  2136.4 1964.07
#Mann= 12 ,-1 , 0
       0      .1       0  177.39      .1       0  193.29     .05       0
  279.91      .1       0  382.44     .05       0  1292.6      .1       0
  1343.3    .045       0  1390.4      .1       0 1392.88     .06       0
 1493.15     .05       0 1950.59      .1       0  2029.5      .1       0
#XS Ineff= 2 , 0
          1239.1    1842
Permanent Ineff=
       F       F
Bank Sta=1343.3,1390.4
XS Rating Curve= 0 ,0
Exp/Cntr(USF)=0,0
Exp/Cntr=0.3,0.1

Type RM Length L Ch R = 1 ,161554  ,496.9,490.7,485.2
XS GIS Cut Line= 4
2451328.14886931556874.202654623 2451615.7399971556641.682168329
2452288.82561531556819.1320131332452912.95955221556335.734160048
#Sta/Elev= 30
       0 1947.43   66.191937.811   106.6 1928.59   270.8 1863.54   291.4 1858.97
  356.051852.957  387.111849.858   406.1  1842.1     435 1824.87   516.11823.339
   608.7 1821.97   710.5 1824.99   731.9 1819.51   749.7  1815.3   803.2 1816.95
  827.351820.295   848.7 1820.89   870.9 1825.25     919 1822.37   927.3 1824.86
   939.7 1832.89  950.891833.696 1398.531836.721 1511.591840.676  1563.6 1843.52
 1627.661843.547  1670.4 1857.26 1737.721864.367  1825.9 1869.59  1855.4  1875.1
#Mann= 12 ,-1 , 0
       0      .1       0   66.19      .1       0  356.05     .05       0
  387.11      .1       0   516.1     .05       0   731.9    .045       0
  827.35      .1       0  950.89     .05       0 1398.53     .06       0
 1511.59     .05       0 1627.66    .055       0 1737.72     .05       0
Bank Sta=731.9,827.35
XS Rating Curve= 0 ,0
Exp/Cntr(USF)=0,0
Exp/Cntr=0.3,0.1