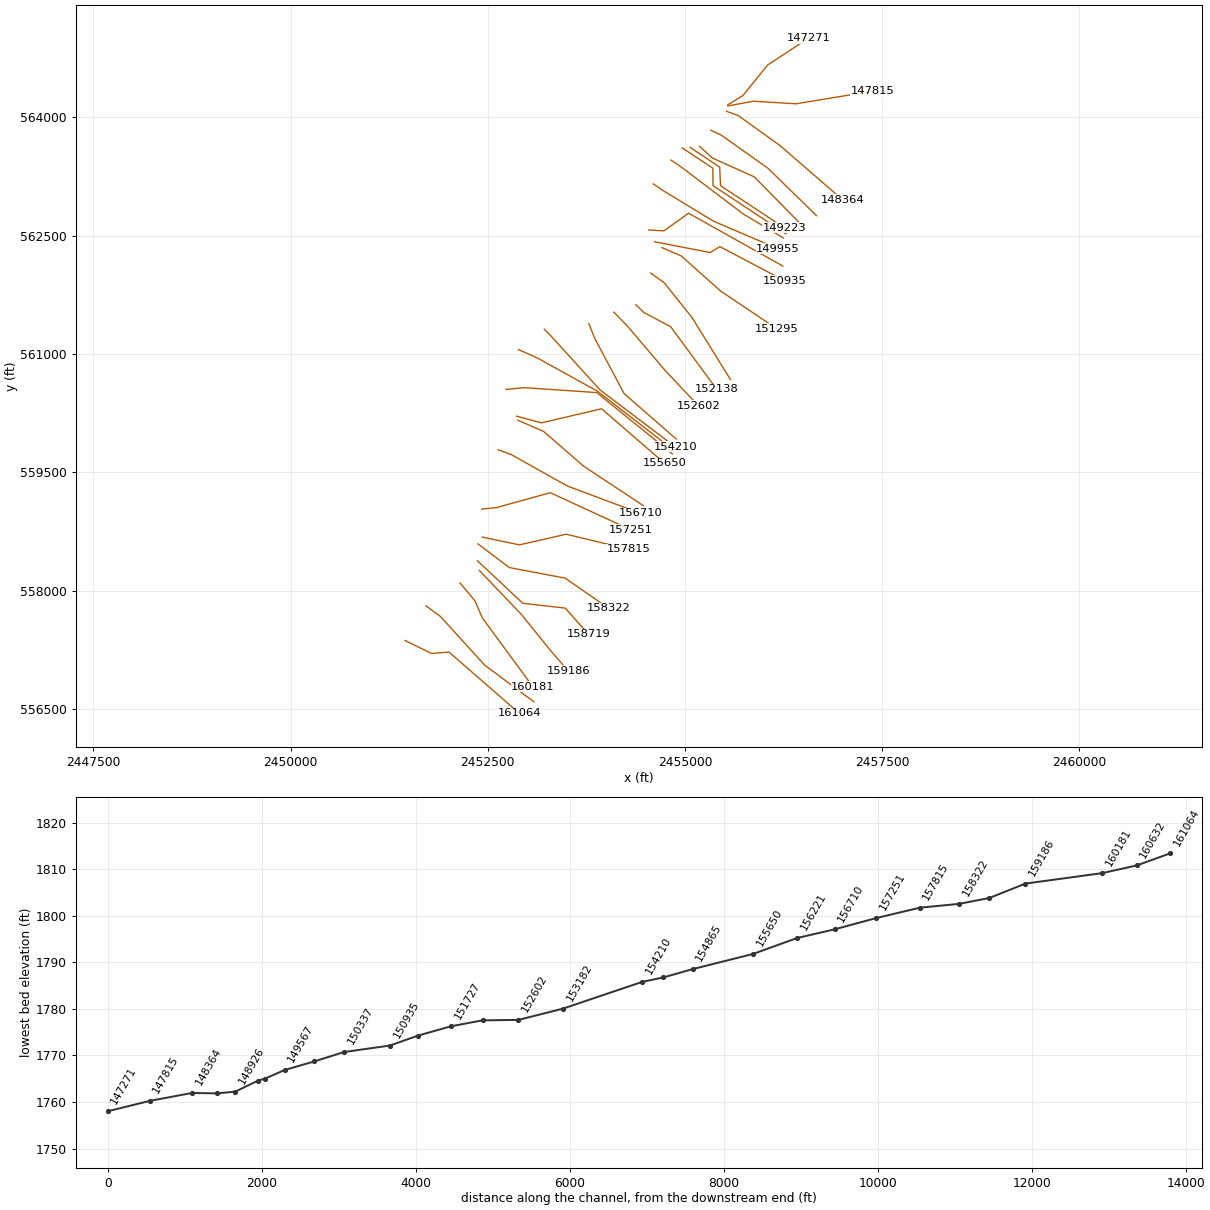
HEC-RAS study SFSBPOTOMC.prj: SFSBPOTOMC

--- SFSBPOTOMC.g01 (geometry) --- (continued)

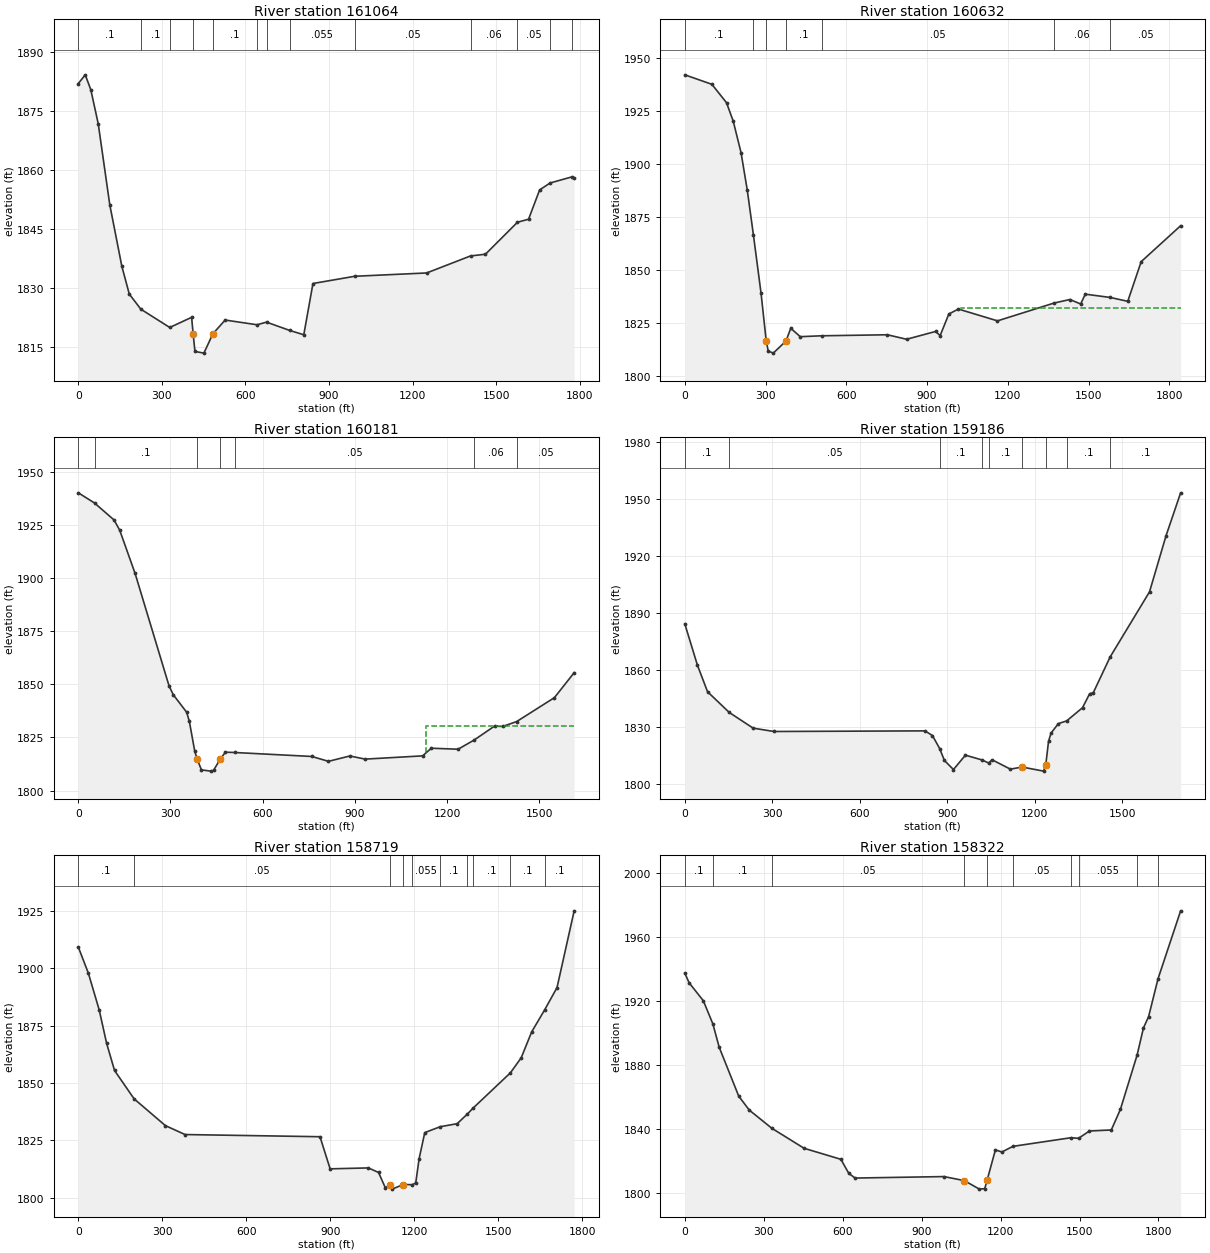
Type RM Length L Ch R = 1 ,161064  ,460,431.2,390.1
XS GIS Cut Line= 4
2451450.52807262557369.8384280392451787.07088173557204.626503567
 2452007.3534477557222.9833840642452900.72163188556445.875443029
#Sta/Elev= 30
       0 1881.92    24.8 1884.13    44.8 1880.35    71.5 1871.67   112.9 1851.09
   156.2 1835.45   182.9  1828.4  224.371824.554  328.191819.902   406.7 1822.48
  412.241818.195   418.7 1813.81   450.8 1813.38     483 1818.29   527.1 1821.79
  641.561820.592  675.611821.258  758.421819.159   809.4 1818.05   842.3 1831.08
  992.161832.917  1250.5 1833.76 1407.891838.085  1461.5 1838.52 1576.511846.656
  1616.3 1847.42    1656 1854.86 1693.381856.627 1774.021858.227    1780 1857.96
#Mann= 13 ,-1 , 0
       0      .1       0  224.37      .1       0  328.19     .05       0
  412.24    .045       0     483      .1       0  641.56     .05       0
  675.61      .1       0  758.42    .055       0  992.16     .05       0
 1407.89     .06       0 1576.51     .05       0 1693.38    .055       0
 1774.02     .05       0
Bank Sta=412.24,483
XS Rating Curve= 0 ,0
Exp/Cntr(USF)=0,0
Exp/Cntr=0.3,0.1

Type RM Length L Ch R = 1 ,160632  ,460.6,450.9,435.2
XS GIS Cut Line= 4
2451713.64335975557810.4035599642451897.21216471 557675.78643632
2452460.15649995557057.7714595922453084.29043685556592.730487004
#Sta/Elev= 30
       0  1942.1   100.6 1937.63   155.1 1928.92   179.9 1920.24   208.9 1905.43
   232.2  1887.6  254.861866.607   283.2 1839.12  302.511816.478     310 1811.81
   328.5  1810.8  375.711816.478   393.6 1822.53     429 1818.56  508.531818.981
   752.6 1819.46     824 1817.34   931.6 1821.02   948.6 1819.07   980.9 1829.27
  1016.5 1831.59  1161.6 1826.02 1371.171834.405  1430.5  1836.1  1470.6 1833.98
  1487.7 1838.62 1579.861837.074  1645.5 1835.25  1695.4 1853.96  1841.9  1870.9
#Mann= 7 ,-1 , 0
       0      .1       0  254.86      .1       0  302.51    .045       0
  375.71      .1       0  508.53     .05       0 1371.17     .06       0
 1579.86     .05       0
#XS Ineff= 2 , 0
                          1027.4         1831.88
Permanent Ineff=
       F       F
Bank Sta=302.51,375.71
XS Rating Curve= 0 ,0
Exp/Cntr(USF)=0,0
Exp/Cntr=0.3,0.1

Type RM Length L Ch R = 1 ,160181  ,980.2,995.1,1012
XS GIS Cut Line= 4
2452148.08953151558097.9946877482452337.77729664 557871.59316162
2452429.56169912557657.4295558232453072.05251652556782.418252139
#Sta/Elev= 30
       0 1940.09   52.721935.294   116.2 1927.33   134.7  1922.5   184.8 1902.14
   295.4  1849.2   309.2 1845.05   352.7 1836.83   361.4 1832.52   378.8  1818.6
  386.12 1815.05   400.6 1809.72     431 1809.14     440 1809.45   462.4 1814.95
   478.9 1818.05  508.741817.908   759.8 1816.04   814.2 1813.75   883.9 1816.27
   933.5 1814.79  1120.5 1816.32  1149.1 1819.92  1236.2 1819.45  1288.71823.802
  1355.1 1830.37  1380.9 1830.14 1426.911832.476  1549.7 1843.72  1613.9 1855.47
#Mann= 7 ,-1 , 0
       0      .1       0   52.72      .1       0  386.12    .045       0
   462.4      .1       0  508.74     .05       0  1288.7     .06       0
 1426.91     .05       0
#XS Ineff= 2 , 0
                         1130.02         1830.27
Permanent Ineff=
       F       F
Bank Sta=386.12,462.4
XS Rating Curve= 0 ,0
Exp/Cntr(USF)=0,0
Exp/Cntr=0.3,0.1

Type RM Length L Ch R = 1 ,159186  ,432.4,467.2,498.8
XS GIS Cut Line= 4
2452392.84793813558257.0876520552452925.19747254557700.262276983
2453286.21612231557253.5781848922453518.73660861556984.343937604
#Sta/Elev= 30
       0 1884.35    43.3 1862.62      78 1848.65  152.54 1837.74   234.3 1829.51
   305.6 1827.74   823.6 1828.07   849.3 1825.61  874.171818.727   890.4 1812.49
   921.3 1807.73   962.4 1815.29 1019.29 1812.78 1041.931811.175    1054 1812.86
  1116.7 1807.93  1156.4 1809.06  1230.4  1806.9    12381810.298  1247.4 1822.57
    1256 1826.91  1281.3  1831.9 1309.521833.309  1363.9 1840.24  1388.3 1847.56
  1400.9 1848.14  1458.8 1866.97  1593.7 1901.17  1650.4 1930.69  1700.4 1953.24
#Mann= 9 ,-1 , 0
       0      .1       0  152.54     .05       0  874.17      .1       0
 1019.29    .055       0 1041.93      .1       0  1156.4    .045       0
    1238    .055       0 1309.52      .1       0  1458.8      .1       0
Bank Sta=1156.4,1238
XS Rating Curve= 0 ,0
Exp/Cntr(USF)=0,0
Exp/Cntr=0.3,0.1

Type RM Length L Ch R = 1 ,158719  ,395,396.9,392.7
XS GIS Cut Line= 4
2452368.37209747558379.4668553672452943.55435304557840.998360792
2453482.02284761557779.8087591362453775.73293556557449.384910192
#Sta/Elev= 30
       0 1909.24      36 1897.82    74.5 1881.92   101.1 1867.32   129.4 1855.49
  199.341843.141     311 1831.49   381.3 1827.59   863.6 1826.64   899.8 1812.65
  1036.7 1813.05  1072.9 1811.06  1097.1  1804.4  1113.2 1805.67  1121.2 1803.81
  1161.4 1805.81 1193.711805.748  1205.8 1806.53  1217.8 1817.03    1238 1828.43
 1293.141830.997  1353.7 1832.31 1390.741836.574 1410.641839.104 1543.941854.457
  1582.6    1861  1619.9 1872.27  1666.81881.985  1710.7 1891.62  1771.9 1925.05
#Mann= 10 ,-1 , 0
       0      .1       0  199.34     .05       0  1113.2    .045       0
  1161.4     .05       0 1193.71    .055       0 1293.14      .1       0
 1390.74    .055       0 1410.64      .1       0 1543.94      .1       0
  1666.8      .1       0
Bank Sta=1113.2,1161.4
XS Rating Curve= 0 ,0
Exp/Cntr(USF)=0,0
Exp/Cntr=0.3,0.1

Type RM Length L Ch R = 1 ,158322  ,482.2,507.6,520
XS GIS Cut Line= 4
2452374.49105763558593.630461164 2452772.2234684558293.801413049
2453482.02284761558159.1842894052454026.61030235557779.808759136
#Sta/Elev= 30
       0 1937.28    16.4 1931.26    70.4 1920.05  106.691905.585   130.7 1891.04
   204.9 1860.56   244.9 1851.85  331.241840.442   453.4 1828.01   593.1 1821.14
   623.2 1812.38   647.2 1809.45   984.9 1810.37  1062.5 1807.83  1119.5 1802.54
  1139.8 1802.85 1149.161808.291  1180.3 1827.02    1205 1825.71 1247.251829.234
  1467.61834.607  1496.41834.226  1537.3 1838.78  1620.7 1839.44  1655.3 1852.26
 1718.611886.032    1743 1903.11  1762.5 1910.11 1798.131933.637  1884.2 1976.13
#Mann= 10 ,-1 , 0
       0      .1       0  106.69      .1       0  331.24     .05       0
  1062.5    .045       0 1149.16     .06       0 1247.25     .05       0
  1467.6    .035       0  1496.4    .055       0 1718.61      .1       0
 1798.13     .12       0
Bank Sta=1062.5,1149.16
XS Rating Curve= 0 ,0
Exp/Cntr(USF)=0,0
Exp/Cntr=0.3,0.1

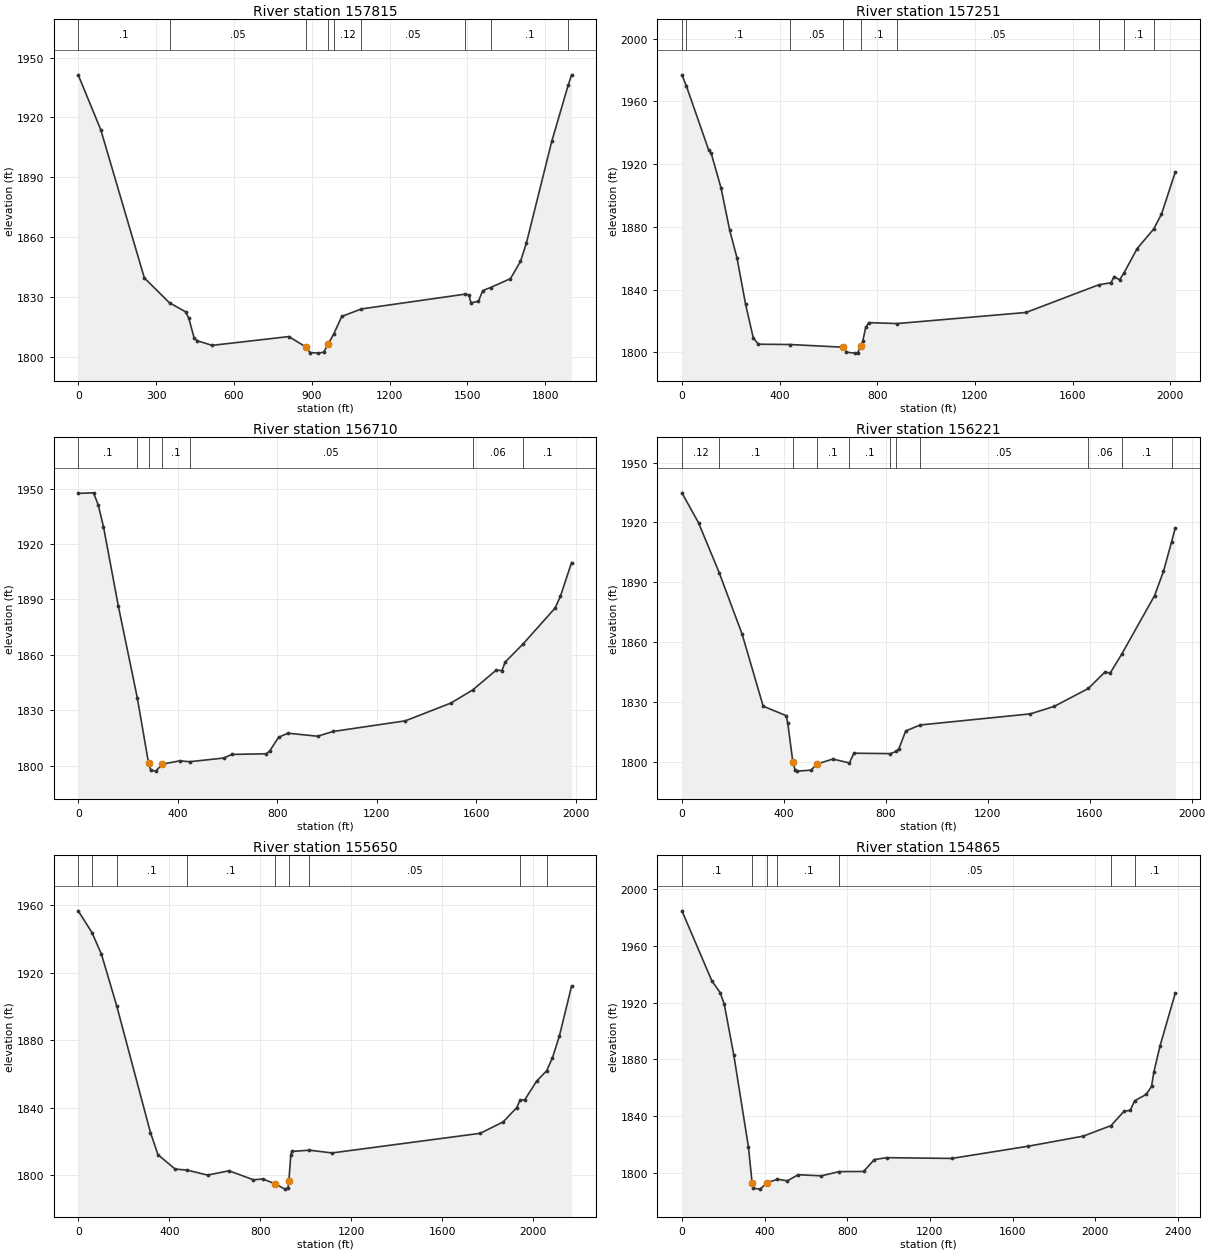
Type RM Length L Ch R = 1 ,157815  ,562,564.1,567.3
XS GIS Cut Line= 4
2452429.56169912558679.2959034832452900.72163188558581.392540833
2453494.26076794558716.0096644772454283.60662931558526.321899342
#Sta/Elev= 30
       0 1941.37      87 1913.83     255 1839.45  352.021826.965   413.6 1822.48
   426.1 1819.34   446.5  1809.5   458.8 1807.94   516.1 1805.62   811.8 1810.03
   877.1 1804.87   893.5 1802.02   925.5 1801.72   946.8 1802.22   962.3 1806.09
  984.671811.184  1015.8 1820.13 1091.651823.903 1490.041831.298  1505.8 1830.94
  1514.1    1827  1542.9 1827.73  1559.3 1833.12 1589.641834.657  1666.3 1839.11
  1704.8 1847.75    1728 1857.12  1825.4 1908.01 1888.431936.054  1901.7 1941.41
#Mann= 9 ,-1 , 0
       0      .1       0  352.02     .05       0   877.1    .045       0
   962.3     .05       0  984.67     .12       0 1091.65     .05       0
 1490.04     .06       0 1589.64      .1       0 1888.43      .1       0
Bank Sta=877.1,962.3
XS Rating Curve= 0 ,0
Exp/Cntr(USF)=0,0
Exp/Cntr=0.3,0.1

Type RM Length L Ch R = 1 ,157251  ,553.7,540.6,508.4
XS GIS Cut Line= 4
2452423.44273896559034.1955930892452607.01154393559052.552473586
2453292.33508248559242.2402387212454314.20143014558771.080305967
#Sta/Elev= 30
       0 1977.01   17.851970.047   109.6 1929.05   119.9 1926.98   160.1 1904.86
   195.9 1877.72   225.2 1860.46   260.9 1830.57   292.1  1809.3   312.9 1805.19
   444.51804.986   660.8 1803.28     674 1800.12   707.2  1799.5   719.6 1799.66
   731.7 1803.76   740.4 1806.93   752.8 1815.95   765.3 1818.96  881.711818.359
  1409.2 1825.43 1707.191843.078  1757.1 1844.39  1770.4 1848.33  1792.4 1846.25
 1810.281850.532  1864.6  1866.2 1932.241878.635  1964.2 1888.11  2020.8 1914.93
#Mann= 9 ,-1 , 0
       0     .12       0   17.85      .1       0   444.5     .05       0
   660.8    .045       0   731.7      .1       0  881.71     .05       0
 1707.19     .06       0 1810.28      .1       0 1932.24      .1       0
Bank Sta=660.8,731.7
XS Rating Curve= 0 ,0
Exp/Cntr(USF)=0,0
Exp/Cntr=0.3,0.1

Type RM Length L Ch R = 1 ,156710  ,488.3,489,485.7
XS GIS Cut Line= 4
2452631.48738459559786.8276934622452796.69930906559725.638091805
2453506.49868828 559327.905681042454436.58063345558979.124951599
#Sta/Elev= 30
       0 1947.46    61.6 1947.75    80.3  1941.3   101.6  1929.4   161.4 1886.38
  237.321836.898   282.6 1801.56   291.4 1797.65   311.5 1797.08   338.4 1800.87
   407.8 1802.64  448.771802.185   585.2 1804.17   617.5 1806.13   755.7 1806.48
     770 1808.06   805.6 1815.44   843.4 1817.61   962.6 1815.97  1024.3 1818.55
  1314.8  1824.3  1498.4 1833.95  1585.71841.016  1680.5 1851.79  1703.5 1851.49
  1716.3 1856.13 1788.291865.946  1916.7 1885.34  1938.5 1891.79  1983.1 1909.97
#Mann= 7 ,-1 , 0
       0      .1       0  237.32      .1       0   282.6    .045       0
   338.4      .1       0  448.77     .05       0  1585.7     .06       0
 1788.29      .1       0
Bank Sta=282.6,338.4
XS Rating Curve= 0 ,0
Exp/Cntr(USF)=0,0
Exp/Cntr=0.3,0.1

Type RM Length L Ch R = 1 ,156221  ,532.4,570.9,587.8
XS GIS Cut Line= 4
2452882.36475138560160.0842635652453206.66964016560019.348179756
2453714.54333391 559578.783047832454473.29439444559077.028314249
#Sta/Elev= 30
       0 1934.85    65.1 1919.82  146.221894.766   235.9 1864.02   318.7 1827.82
   409.2 1823.02   415.3 1819.19  435.141799.805   443.6 1795.96   450.3 1795.21
   506.8 1795.69   528.4 1798.72   591.9 1801.26  657.241799.314   674.3  1804.2
  817.921803.992  840.711805.108   851.4  1806.5   877.9 1815.36  934.69 1818.37
  1366.8 1823.94  1460.8 1827.71 1594.451836.688  1658.1 1844.75  1681.2 1844.62
 1725.271853.879  1854.4 1883.31  1889.3  1895.5 1921.281910.363  1935.5 1917.27
#Mann= 11 ,-1 , 0
       0     .12       0  146.22      .1       0  435.14    .045       0
   528.4      .1       0  657.24      .1       0  817.92     .05       0
  840.71      .1       0  934.69     .05       0 1594.45     .06       0
 1725.27      .1       0 1921.28      .1       0
Bank Sta=435.14,528.4
XS Rating Curve= 0 ,0
Exp/Cntr(USF)=0,0
Exp/Cntr=0.3,0.1

Type RM Length L Ch R = 1 ,155650  ,783.8,785.1,747.3
XS GIS Cut Line= 4
  2452863.989514560211.8384286462453180.70077322560127.084711392
 2453943.4842285560305.5135898222454741.95345948559614.101685906
#Sta/Elev= 30
       0 1956.53   60.48 1943.65   102.2 1930.82     1691900.344   317.5 1825.25
   350.5 1812.16   425.9 1803.66  479.151803.058   568.2 1800.09   662.7 1802.65
   769.5 1797.33   812.1 1797.81     864 1794.95   908.7 1791.79   921.5 1792.56
   925.6 1796.61   933.8 1811.76   937.9 1814.11 1016.171814.828  1115.5 1813.22
  1766.4 1824.83  1866.9 1831.57  1926.4 1840.01 1941.591844.497  1962.1 1844.71
  2014.3 1855.75  2058.31861.897  2083.8  1869.6  2113.6 1882.22  2167.5  1911.9
#Mann= 9 ,-1 , 0
       0      .1       0   60.48     .12       0     169      .1       0
  479.15      .1       0     864    .045       0   925.6      .1       0
 1016.17     .05       0 1941.59     .06       0  2058.3      .1       0
Bank Sta=864,925.6
XS Rating Curve= 0 ,0
Exp/Cntr(USF)=0,0
Exp/Cntr=0.3,0.1

Type RM Length L Ch R = 1 ,154865  ,390.6,378.5,356.7
XS GIS Cut Line= 4
2452730.16785518560550.8532976622452962.12539714560573.156907466
2453881.03412105560510.7068000162454840.08934261559734.541178847
#Sta/Elev= 30
       0  1984.8   145.2 1935.27   185.4 1927.06   205.1 1918.76   250.8 1883.26
   321.9 1818.32  339.481793.084   345.9 1789.19     378 1788.53  412.761793.083
  462.44 1795.52   510.3 1794.38   562.3 1798.68   674.7 1797.91  761.681800.897
   879.1 1800.98   931.3 1809.37   991.4 1810.72  1305.9 1810.18    1676  1818.8
    1943 1825.93    20771833.349  2139.3 1843.39    2170 1844.15 2191.421850.896
  2247.4 1855.36  2272.9 1860.97  2284.2 1871.14  2314.1 1889.61  2387.8 1926.72
#Mann= 7 ,-1 , 0
       0      .1       0  339.48    .045       0  412.76      .1       0
  462.44      .1       0  761.68     .05       0    2077     .06       0
 2191.42      .1       0
Bank Sta=339.48,412.76
XS Rating Curve= 0 ,0
Exp/Cntr(USF)=0,0
Exp/Cntr=0.3,0.1

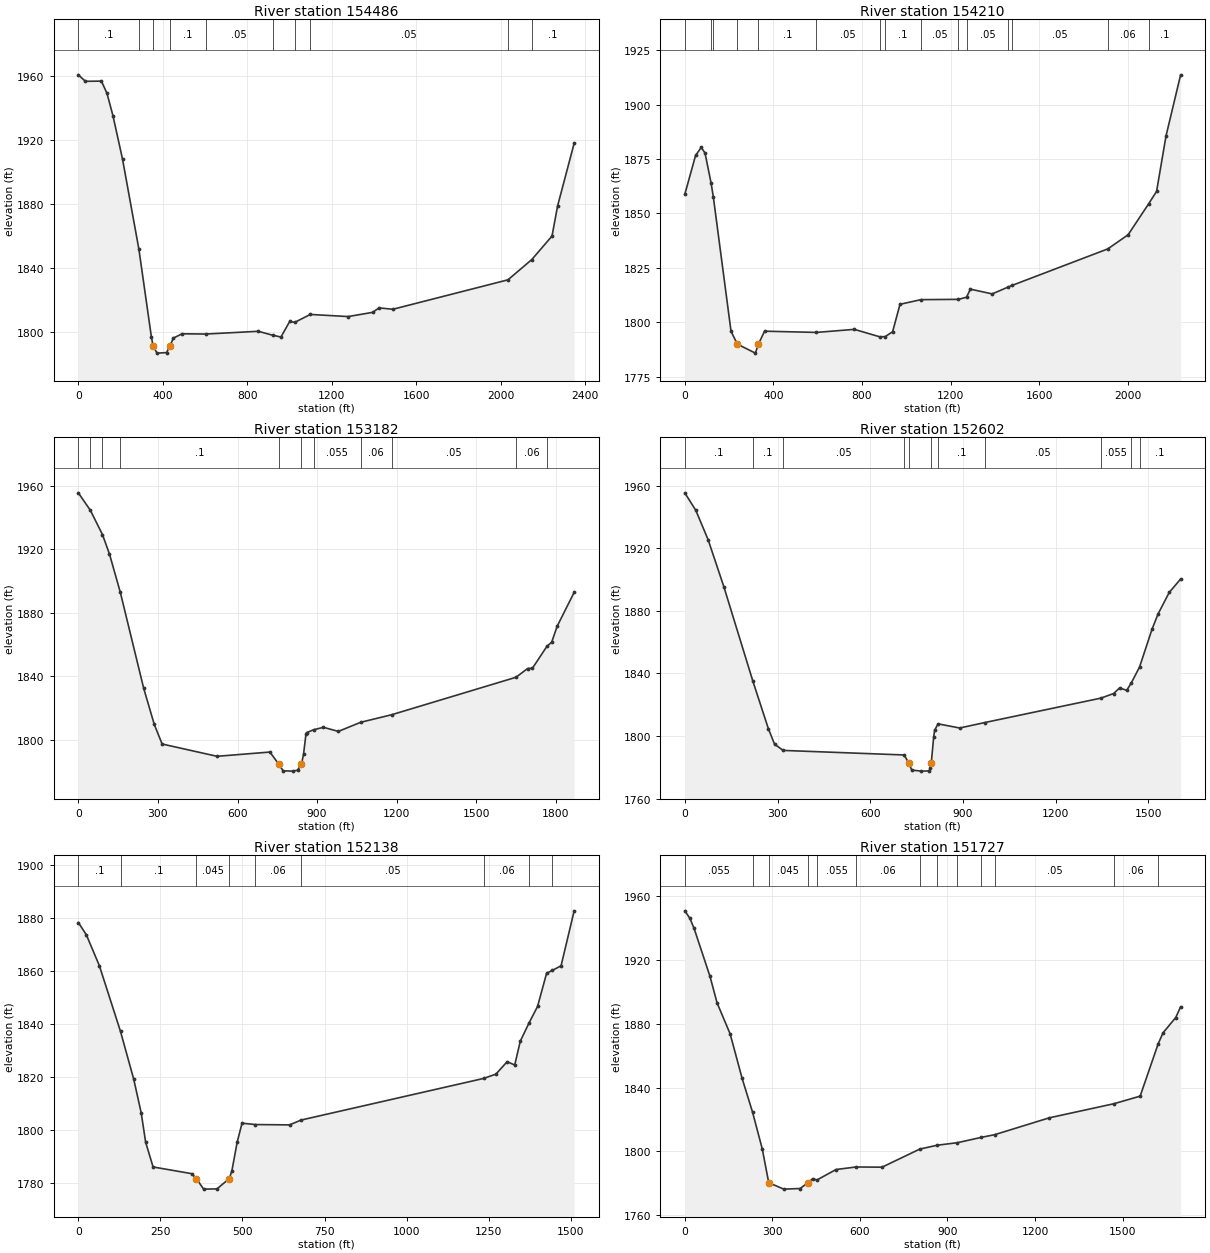
Type RM Length L Ch R = 1 ,154486  ,293.6,276.1,262.2
XS GIS Cut Line= 4
2452890.75384577561054.9148792262453122.71138773560952.318274129
2453889.95556497560528.549687859 2454853.7329068559782.782102563
#Sta/Elev= 30
       0  1960.8    33.4 1956.75   109.2 1956.87   135.6 1949.28   163.8 1935.34
   209.3 1908.09  286.861851.755     346 1796.95  353.911791.495   372.4 1786.75
   418.2 1787.09  434.671791.496   450.2 1796.16   491.3 1798.84  603.341798.683
   852.3 1800.41  919.821797.977   959.8 1796.83  1001.2 1806.55 1025.311806.007
 1098.861810.946  1277.8 1809.62  1394.1 1812.25  1424.5 1815.04  1490.2 1814.19
 2035.141832.593 2148.171845.279  2243.9 1859.99  2270.1 1878.73  2348.7    1918
#Mann= 10 ,-1 , 0
       0      .1       0  286.86      .1       0  353.91    .045       0
  434.67      .1       0  603.34     .05       0  919.82      .1       0
 1025.31      .1       0 1098.86     .05       0 2035.14     .06       0
 2148.17      .1       0
Bank Sta=353.91,434.67
XS Rating Curve= 0 ,0
Exp/Cntr(USF)=0,0
Exp/Cntr=0.3,0.1

Type RM Length L Ch R = 1 ,154210  ,1042.8,1028.2,1011.5
XS GIS Cut Line= 4
 2453216.3865489561313.636752949 2453296.6795442561233.343757656
 2453921.1806187560546.392575702 2454875.7751183559823.755618061
#Sta/Elev= 30
       0 1858.74    48.6 1876.61    74.3 1880.34    91.3 1877.75  118.481864.074
  128.661857.735   208.8 1795.82  237.231789.916   318.8 1785.79  332.491789.916
   360.1 1795.87  594.611795.312   765.6 1796.71  880.081793.302  905.241793.379
   938.6 1795.65   971.9 1808.23 1066.591810.365  1235.81810.503 1272.321811.484
  1289.7  1815.2  1388.2    1813  1460.61816.171 1478.051816.911 1910.181833.679
  2002.1 1840.18 2095.251854.488  2130.6  1860.1  2173.4 1885.67  2239.2 1913.68
#Mann= 15 ,-1 , 0
       0      .1       0  118.48     .12       0  128.66      .1       0
  237.23    .045       0  332.49      .1       0  594.61     .05       0
  880.08      .1       0  905.24      .1       0 1066.59     .05       0
  1235.8     .06       0 1272.32     .05       0  1460.6     .06       0
 1478.05     .05       0 1910.18     .06       0 2095.25      .1       0
Bank Sta=237.23,332.49
XS Rating Curve= 0 ,0
Exp/Cntr(USF)=0,0
Exp/Cntr=0.3,0.1

Type RM Length L Ch R = 1 ,153182  ,569.1,579.7,583.7
XS GIS Cut Line= 4
2453781.69270303 561385.76102637 2453851.0817113561207.332147941
 2454227.7648991560498.5729919562454886.96047774559923.635494794
#Sta/Elev= 30
       0 1955.76   45.63 1944.64   90.891929.438   117.4 1917.12  158.331892.874
   246.3 1832.37   286.2 1809.54   315.8 1797.17   522.8 1789.41   721.9 1792.09
  755.631784.442   771.8 1780.24     808 1780.05   826.1 1780.63  841.011784.441
   848.8  1790.7   857.8 1803.19     860 1804.32  886.611806.151   923.7 1807.72
   980.1 1805.13 1064.341810.891  1181.31815.672 1649.161839.283  1693.3 1844.81
  1711.7 1845.06 1766.131858.837  1784.1 1861.46  1804.8 1871.55  1868.8 1892.93
#Mann= 11 ,-1 , 0
       0      .1       0   45.63      .1       0   90.89      .1       0
  158.33      .1       0  755.63    .045       0  841.01      .1       0
  886.61    .055       0 1064.34     .06       0  1181.3     .05       0
 1649.16     .06       0 1766.13      .1       0
Bank Sta=755.63,841.01
XS Rating Curve= 0 ,0
Exp/Cntr(USF)=0,0
Exp/Cntr=0.3,0.1

Type RM Length L Ch R = 1 ,152602  ,453.7,464.7,475.6
XS GIS Cut Line= 4
2454098.89959801561529.4954006612454272.37211871561351.066522231
2454748.18246119560790.9980982712455174.42922632560339.969544463
#Sta/Elev= 30
       0 1955.39    35.7 1944.16    75.3 1925.53   126.2 1895.51  220.561834.899
   270.5 1804.68   290.4 1794.85  318.171790.854  709.661787.945  724.311782.929
   734.4 1778.28   765.3 1777.62     790 1777.74   794.9 1779.41  797.551782.926
   805.4 1799.67   808.5  1803.8  819.581807.818   889.4 1805.17  970.641808.651
 1346.291824.248  1387.4 1827.18  1406.8 1830.75  1430.1 1829.22 1445.251834.201
 1471.321844.072  1512.2 1868.51  1531.7 1878.17  1567.3 1891.74  1604.3 1900.33
#Mann= 11 ,-1 , 0
       0      .1       0  220.56      .1       0  318.17     .05       0
  709.66      .1       0  724.31    .045       0  797.55      .1       0
  819.58      .1       0  970.64     .05       0 1346.29    .055       0
 1445.25     .06       0 1471.32      .1       0
Bank Sta=724.31,797.55
XS Rating Curve= 0 ,0
Exp/Cntr(USF)=0,0
Exp/Cntr=0.3,0.1

Type RM Length L Ch R = 1 ,152138  ,436.4,411,376.6
XS GIS Cut Line= 4
2454376.45563112 561623.666197612454480.53914354561524.539042927
2454817.57146946561346.110164497 2455402.4216821560553.092927032
#Sta/Elev= 30
       0  1878.2    24.3  1873.6    63.9 1861.96  128.461837.075   168.9 1818.96
   191.5 1806.34   205.1 1795.21   227.7  1785.9   345.4 1783.37  359.721781.486
   381.6 1777.53   422.3 1777.62   459.71781.484   467.6 1784.35   483.9 1795.29
   498.7 1802.43  539.611801.911   643.4 1801.79  678.571803.612 1234.421819.324
    1272 1820.95  1306.3 1825.66  1329.3 1824.39  1346.3  1833.4 1373.381840.389
  1398.9 1846.51  1426.4 1859.02 1443.781860.128  1470.5 1861.86  1510.4 1882.62
#Mann= 9 ,-1 , 0
       0      .1       0  128.46      .1       0  359.72    .045       0
   459.7      .1       0  539.61     .06       0  678.57     .05       0
 1234.42     .06       0 1373.38     .12       0 1443.78      .1       0
Bank Sta=359.72,459.7
XS Rating Curve= 0 ,0
Exp/Cntr(USF)=0,0
Exp/Cntr=0.3,0.1

Type RM Length L Ch R = 1 ,151727  ,419.4,431.7,440.4
XS GIS Cut Line= 4
2454564.79722502562025.1311740772454738.26974572561901.222230723
2455090.17114484561460.1063923832455575.89420279560677.001870386
#Sta/Elev= 30
       0 1950.99    17.6 1946.25    31.9  1939.9    86.4 1909.81   110.5 1893.23
   155.3 1873.75   196.5 1845.74  232.321824.468   265.3 1801.61  287.631780.285
     339 1776.25   395.3 1776.64  421.811780.286   438.4 1782.82  452.83 1781.99
   518.1 1788.55  586.921790.161   675.8 1790.03  805.391801.408  865.071803.819
   933.9  1805.4 1016.391808.757 1062.431810.466  1249.4 1821.04 1470.371829.871
  1560.3 1834.63 1621.691867.282  1638.7  1874.4  1682.2 1883.99    1699 1890.75
#Mann= 13 ,-1 , 0
       0    .055       0  232.32     .06       0  287.63    .045       0
  421.81     .06       0  452.83    .055       0  586.92     .06       0
  805.39    .055       0  865.07     .06       0   933.9     .05       0
 1016.39     .06       0 1062.43     .05       0 1470.37     .06       0
 1621.69     .05       0
Bank Sta=287.63,421.81
XS Rating Curve= 0 ,0
Exp/Cntr(USF)=0,0
Exp/Cntr=0.3,0.1

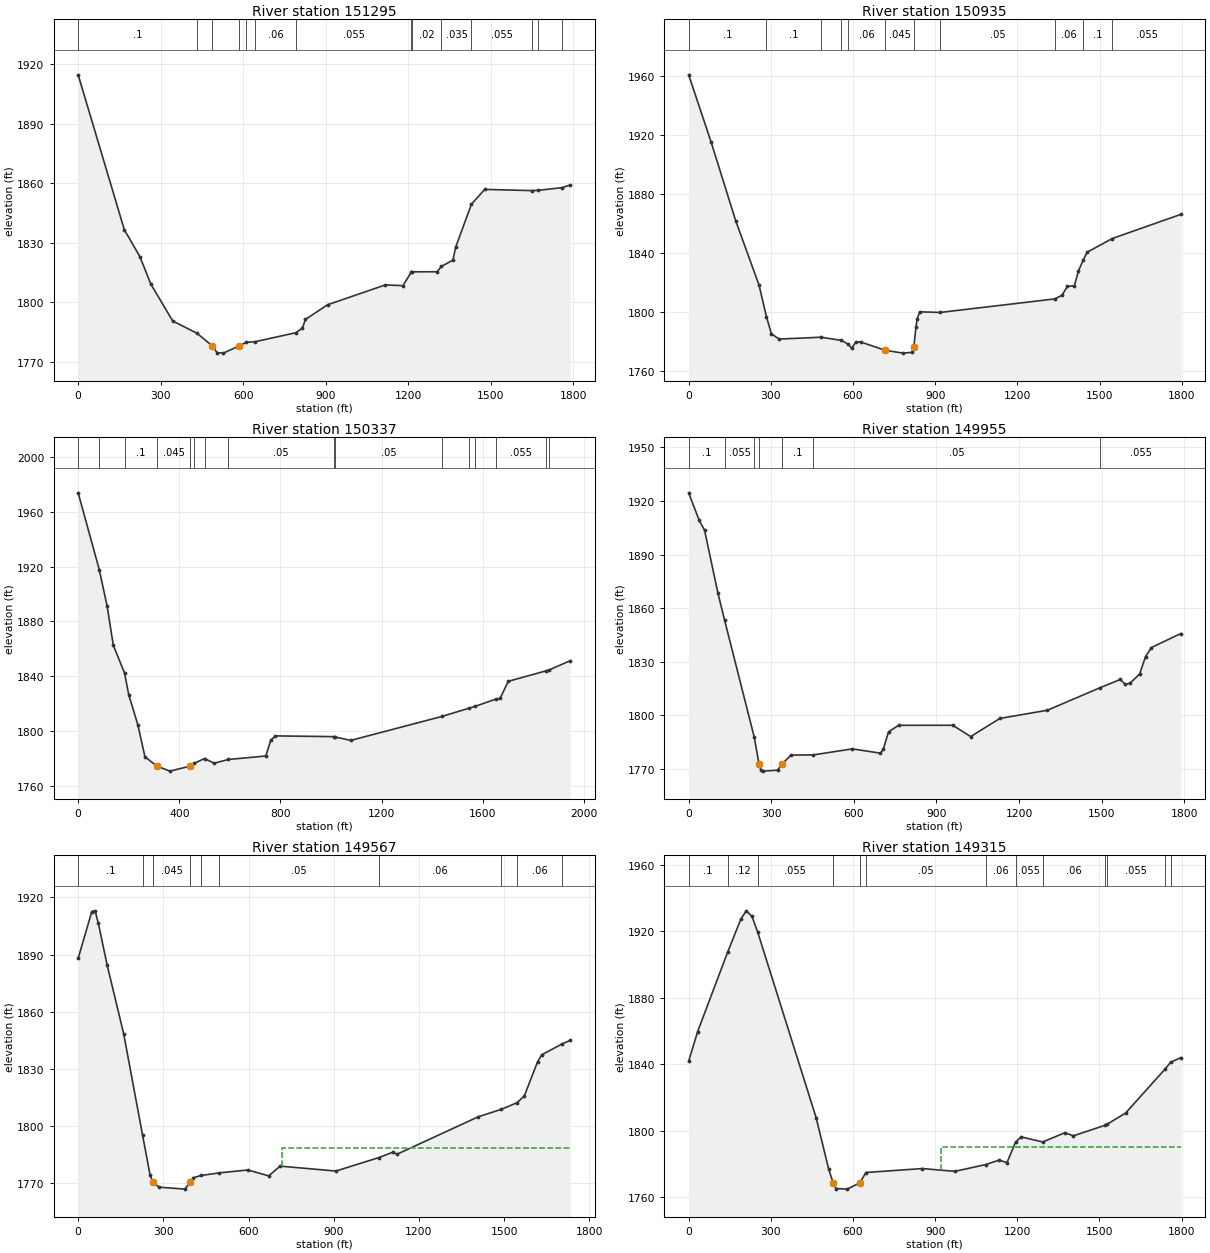
Type RM Length L Ch R = 1 ,151295  ,277.6,359.7,404.3
XS GIS Cut Line= 4
2454708.53159931562347.2944267972454951.39312829 562243.21091438
2455451.98525944561797.1387183052456160.74441542561321.328375826
#Sta/Elev= 30
       0 1914.58   167.8 1836.46   224.4  1822.9   264.2 1809.02   343.7 1790.44
   431.91784.248  487.561777.854   504.8 1774.45   527.5 1774.23  584.491777.854
  611.571779.692  643.411780.001  791.241784.528   815.2 1786.85   825.9 1791.22
   906.3 1798.61  1116.3 1808.63  1180.5 1808.26 1210.791815.127 1211.491815.248
  1304.4 1815.26 1320.081817.957    1362 1821.15  1371.7 1827.58 1429.371849.389
  1477.6 1856.81 1647.941856.197 1672.231856.341 1757.231857.659  1788.4 1859.01
#Mann= 14 ,-1 , 0
       0      .1       0   431.9     .06       0  487.56    .045       0
  584.49     .06       0  611.57    .055       0  643.41     .06       0
  791.24    .055       0 1210.79    .035       0 1211.49     .02       0
 1320.08    .035       0 1429.37    .055       0 1647.94     .05       0
 1672.23     .06       0 1757.23     .05       0
Bank Sta=487.56,584.49
XS Rating Curve= 0 ,0
Exp/Cntr(USF)=0,0
Exp/Cntr=0.3,0.1

Type RM Length L Ch R = 1 ,150935  ,593.3,598.3,597.4
XS GIS Cut Line= 4
2454614.36080238 562421.639792832455319.46702001562285.339626223
2455441.78990966562360.3328077642456269.46701998561924.922959551
#Sta/Elev= 30
       0 1961.03    81.9  1915.4   171.5 1862.09   257.1 1818.18  283.931796.919
   301.9 1785.24   330.3 1781.66  482.661782.921  557.591780.788  582.021778.198
   595.2 1775.53   611.5 1779.78   627.8 1779.71   717.4 1774.05   782.8 1772.12
   815.8 1772.64  822.171776.272   829.9 1790.04   834.6 1795.51   843.6 1800.19
  917.681799.726 1336.681808.919  1363.1  1811.4  1382.5 1817.39  1408.4 1817.87
  1423.1 1827.95 1441.441835.641  1454.8  1840.6 1546.191849.8971796.858  1866.3
#Mann= 11 ,-1 , 0
       0      .1       0  283.93      .1       0  482.66     .06       0
  557.59      .1       0  582.02     .06       0   717.4    .045       0
  822.17    .055       0  917.68     .05       0 1336.68     .06       0
 1441.44      .1       0 1546.19    .055       0
Bank Sta=717.4,822.17
XS Rating Curve= 0 ,0
Exp/Cntr(USF)=0,0
Exp/Cntr=0.3,0.1

Type RM Length L Ch R = 1 ,150337  ,441.7,382,317
XS GIS Cut Line= 4
2454540.01543635562570.3305248342454733.31338798562560.417809366
2455045.56392524562783.4539074032456240.04613917562114.345613292
#Sta/Elev= 30
       0 1973.96   83.54 1917.82   114.9 1890.97   138.9 1862.74  183.45 1842.34
   200.2 1826.43   236.5 1804.29   264.1 1781.23  310.641774.435   362.7 1770.72
  443.951774.435   459.11776.389  499.841779.936   537.6 1776.49  593.651779.214
   742.1 1781.78     762 1793.31   780.4 1796.45 1011.841795.903 1016.541795.665
  1078.1 1793.16 1439.431810.683 1545.151816.648 1570.691818.072 1650.871823.224
  1668.8 1823.84  1701.1 1836.31 1850.111843.928 1862.31 1844.58  1946.4  1851.4
#Mann= 16 ,-1 , 0
       0     .12       0   83.54      .1       0  183.45      .1       0
  310.64    .045       0  443.95     .06       0   459.1    .055       0
  499.84     .06       0  593.65     .05       0 1011.84      .1       0
 1016.54     .05       0 1439.43     .06       0 1545.15    .055       0
 1570.69     .06       0 1650.87    .055       0 1850.11     .06       0
 1862.31     .05       0
Bank Sta=310.64,443.95
XS Rating Curve= 0 ,0
Exp/Cntr(USF)=0,0
Exp/Cntr=0.3,0.1

Type RM Length L Ch R = 1 ,149955  ,378.2,387.9,384.5
XS GIS Cut Line= 4
2454599.49172916563155.1807374652454713.48795705563075.879013718
2455357.81446249 562684.326752722456180.56984636562332.425353595
#Sta/Elev= 30
       0 1924.54    38.1 1909.14    57.6 1903.68   106.3 1868.36  130.791853.066
  238.181787.754  255.781772.583     262 1769.17   271.5 1768.72   322.9 1769.25
  338.151772.585   371.8  1777.7  452.531777.799   594.4 1781.18   696.6 1778.78
   706.7 1780.85   726.1 1790.76   762.9 1794.37   959.1  1794.4  1024.4 1788.08
  1130.4 1798.22  1302.8  1802.8 1495.761815.513  1568.1 1820.07  1585.6  1817.3
    1603 1817.93  1638.2  1823.1  1659.5  1832.8  1680.8 1837.92  1787.7 1845.75
#Mann= 7 ,-1 , 0
       0      .1       0  130.79    .055       0  238.18      .1       0
  255.78    .045       0  338.15      .1       0  452.53     .05       0
 1495.76    .055       0
Bank Sta=255.78,338.15
XS Rating Curve= 0 ,0
Exp/Cntr(USF)=0,0
Exp/Cntr=0.3,0.1

Type RM Length L Ch R = 1 ,149567  ,322.6,252.5,212.4
XS GIS Cut Line= 4
 2454822.5278272563457.5185592492454946.43677055563373.260477768
2455739.45400802562773.541191935 2456245.0024969562471.203370151
#Sta/Elev= 30
       0 1887.97    48.1 1912.57    59.6 1912.96    71.2 1906.37   101.8 1884.69
   160.3 1848.43  227.09 1795.06   253.2 1774.31  264.271770.342   285.6 1767.88
   375.9 1766.86  393.771770.342   405.8 1772.86     4331774.018  497.131775.404
   598.1 1776.91     671 1773.82   711.4 1778.94   907.5 1776.35 1058.971783.415
  1108.1 1786.23  1123.1 1785.19  1408.9 1804.83 1490.611808.769 1545.851812.235
  1571.3  1815.8    1618  1833.7  1632.4 1837.35 1704.351843.098  1733.2 1844.97
#Mann= 10 ,-1 , 0
       0      .1       0  227.09      .1       0  264.27    .045       0
  393.77    .055       0     433      .1       0  497.13     .05       0
 1058.97     .06       0 1490.61    .055       0 1545.85     .06       0
 1704.35     .05       0
#XS Ineff= 2 , 0
                          719.11         1788.42
Permanent Ineff=
       F       F
Bank Sta=264.27,393.77
XS Rating Curve= 0 ,0
Exp/Cntr(USF)=0,0
Exp/Cntr=0.3,0.1

Type RM Length L Ch R = 1 ,149315  ,89.4,91.5,94.9
XS GIS Cut Line= 4
2454963.40535689563611.8993733372455353.23909006563353.766225699
2455355.87310177563132.5092420082456280.41121219 562521.41852515
#Sta/Elev= 30
       0 1841.96    32.8 1859.74  142.381907.496   190.7 1927.32   210.3 1932.29
   231.2 1928.98  251.361919.824   465.5 1807.92   511.4 1776.96  527.681768.766
   538.4 1765.39   578.4 1765.03  624.471768.767  647.311775.015   853.7  1777.4
   972.1 1775.71 1084.611779.803  1133.7 1782.48  1162.2 1780.92 1193.54 1793.24
  1214.1 1796.45  1292.5 1793.36  1373.3  1798.9  1405.1 1797.09 1520.33 1803.39
 1526.471803.875  1595.6 1810.76  1738.21836.939 1760.441841.329  1797.1 1844.02
#Mann= 13 ,-1 , 0
       0      .1       0  142.38     .12       0  251.36    .055       0
  527.68    .045       0  624.47    .055       0  647.31     .05       0
 1084.61     .06       0 1193.54    .055       0  1292.5     .06       0
 1520.33      .1       0 1526.47    .055       0  1738.2      .1       0
 1760.44     .05       0
#XS Ineff= 2 , 0
                          923.08         1790.23
Permanent Ineff=
       F       F
Bank Sta=527.68,624.47
XS Rating Curve= 0 ,0
Exp/Cntr(USF)=0,0
Exp/Cntr=0.3,0.1

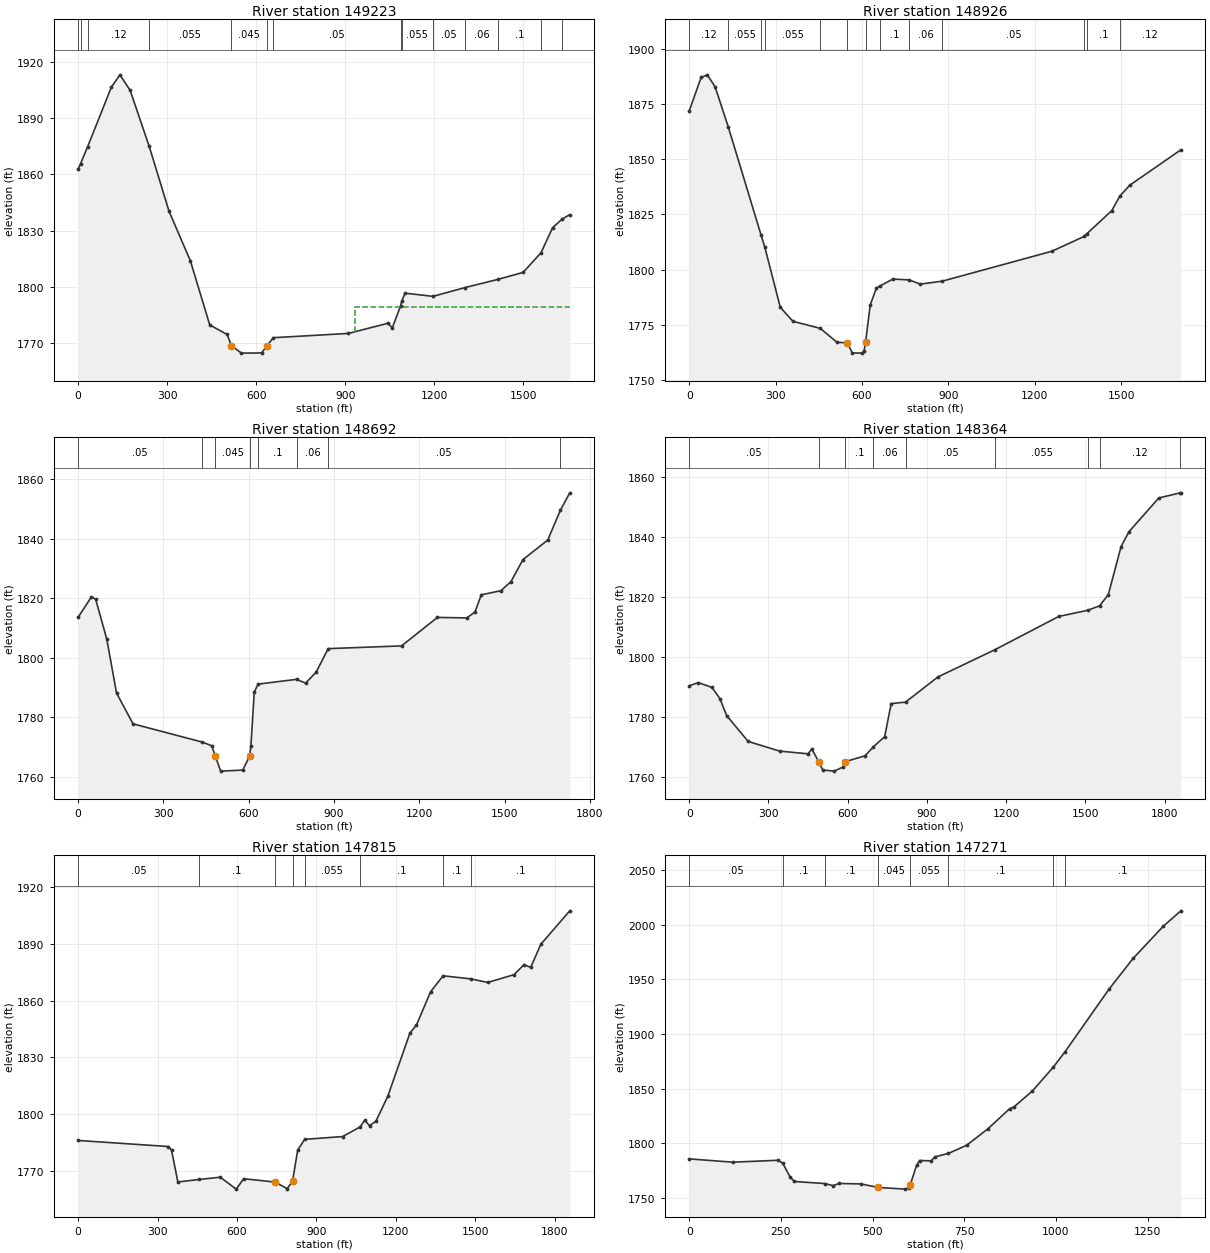
Type RM Length L Ch R = 1 ,149223  ,235.2,297.2,334.6
XS GIS Cut Line= 4
 2455066.1318136563617.1673967592455440.16147651563366.936284252
2455450.69752335563132.5092420082456261.97313022562597.804864757
#Sta/Elev= 30
       0 1862.83    8.041865.686   32.12 1874.85     112 1906.63   140.8 1913.23
   175.1 1904.97   239.21875.168   306.2 1840.39   378.2 1813.88   443.5 1779.63
   502.1 1774.55  516.461768.574   550.2 1764.59   618.2 1764.69  636.251768.573
  657.761772.831   909.9  1775.1  1043.8 1780.54  1058.4 1778.06  1086.51789.865
 1090.461792.406  1101.5 1796.62 1195.361794.909 1304.231799.633  1413.1 1803.93
  1499.1  1807.7 1559.741818.257  1598.3 1831.55 1630.841836.224  1656.3 1838.55
#Mann= 14 ,-1 , 0
       0     .12       0    8.04      .1       0   32.12     .12       0
   239.2    .055       0  516.46    .045       0  636.25    .035       0
  657.76     .05       0  1086.5     .06       0 1090.46    .055       0
 1195.36     .05       0 1304.23     .06       0  1413.1      .1       0
 1559.74    .055       0 1630.84      .1       0
#XS Ineff= 2 , 0
                           933.5         1789.03
Permanent Ineff=
       F       F
Bank Sta=516.46,636.25
XS Rating Curve= 0 ,0
Exp/Cntr(USF)=0,0
Exp/Cntr=0.3,0.1

Type RM Length L Ch R = 1 ,148926  ,246.9,233.9,225.7
XS GIS Cut Line= 4
2455184.34194179563630.9910799442455347.90174702563482.300347919
2455878.23202457 563244.395176682456512.64581455562600.068671239
#Sta/Elev= 30
       0 1871.79    41.4 1887.02    62.7 1888.19    89.7 1882.83  135.281864.762
  249.441815.688  262.241810.309   316.2 1782.95   360.1 1776.62  455.041773.427
   513.3 1767.09   548.6 1766.94   566.1 1762.33     601 1762.22   607.1 1763.15
  612.221767.234   628.3 1783.94   649.5 1791.64  660.631792.502     707 1795.75
  763.431795.359   802.3 1793.46  878.871794.804  1259.1 1808.34 1371.391815.069
 1380.441816.281  1466.8 1826.73 1494.52 1833.23  1528.5 1838.16  1706.5 1854.24
#Mann= 13 ,-1 , 0
       0     .12       0  135.28    .055       0  249.44     .05       0
  262.24    .055       0  455.04     .05       0   548.6    .045       0
  612.22     .05       0  660.63      .1       0  763.43     .06       0
  878.87     .05       0 1371.39     .12       0 1380.44      .1       0
 1494.52     .12       0
Bank Sta=548.6,612.22
XS Rating Curve= 0 ,0
Exp/Cntr(USF)=0,0
Exp/Cntr=0.3,0.1

Type RM Length L Ch R = 1 ,148692  ,327.9,327.6,325.6
XS GIS Cut Line= 4
2455328.07631608563834.2017470452455456.94161717563774.725454235
2456051.70454527563353.4350468312456666.29290431562753.715760998
#Sta/Elev= 30
       0 1813.55      47 1820.44    61.8  1819.6     101 1806.15   135.1  1788.1
   193.2 1777.74  436.531771.616   470.2 1770.36   482.11767.011   501.5 1761.85
   579.2 1762.19  603.84 1767.01   607.9 1770.36   619.6 1788.42  633.171791.099
  768.321792.692   800.2 1791.42   837.5 1795.15  879.711803.014  1137.9 1803.94
  1263.9 1813.51    1367 1813.34  1395.6 1815.27  1418.5 1821.11  1487.3 1822.49
  1522.5 1825.51  1564.9 1832.94  1651.9  1839.5  1696.6 1849.54  1729.5 1855.38
#Mann= 8 ,-1 , 0
       0     .05       0  436.53      .1       0   482.1    .045       0
  603.84      .1       0  633.17      .1       0  768.32     .06       0
  879.71     .05       0  1696.6     .12       0
Bank Sta=482.1,603.84
XS Rating Curve= 0 ,0
Exp/Cntr(USF)=0,0
Exp/Cntr=0.3,0.1

Type RM Length L Ch R = 1 ,148364  ,527.5,549.1,562
XS GIS Cut Line= 4
2455529.80331279564074.083126137 2455677.0505196564019.665680143
2456203.61933525563641.944584415 2457001.7020053562950.372973738
#Sta/Elev= 30
       0  1790.4    34.4  1791.5    86.3 1789.85   116.1 1786.17   141.7 1780.49
   223.1 1771.84   342.2 1768.62   449.5 1767.71   464.3 1769.27   491.3 1764.94
   505.6 1762.31   548.6 1761.93     583 1763.33   590.7  1765.1   666.1 1767.06
  697.271770.063   739.9 1773.42   764.6 1784.47  818.931784.964   941.5 1793.37
 1158.551802.519  1399.2 1813.57 1508.751815.611 1553.421817.112  1586.4 1820.83
  1634.8 1836.87  1664.8 1841.86  1777.7 1853.11 1858.951854.822    1861 1854.77
#Mann= 9 ,-1 , 0
       0     .05       0   491.3    .045       0   590.7      .1       0
  697.27     .06       0  818.93     .05       0 1158.55    .055       0
 1508.75     .05       0 1553.42     .12       0 1858.95    .055       0
Bank Sta=491.3,590.7
XS Rating Curve= 0 ,0
Exp/Cntr(USF)=0,0
Exp/Cntr=0.3,0.1

Type RM Length L Ch R = 1 ,147815  ,507.1,544.1,573.4
XS GIS Cut Line= 4
2455543.46214144564142.9855018012455866.00962062564202.616128204
2456408.10622429564170.0903319842457381.16962787564330.008830066
#Sta/Elev= 30
       0 1785.99   340.8 1782.78   352.8 1780.91   376.8 1764.02  456.551765.329
   537.1 1766.53   597.2 1760.23   625.3 1765.73   744.3 1763.97   789.6 1760.47
  809.931764.445   829.6 1780.93  855.851786.577   999.4 1788.06 1064.611793.099
    1083  1796.7  1100.8 1793.79  1125.1  1796.2  1169.7 1809.35  1253.6 1842.87
  1277.9 1847.02  1331.8 1864.76 1378.871873.129 1483.631871.505  1547.6 1869.63
    1647 1873.75  1684.5 1879.06  1709.6 1877.56  1747.9 1889.81  1857.2 1907.52
#Mann= 8 ,-1 , 0
       0     .05       0  456.55      .1       0   744.3    .045       0
  809.93      .1       0  855.85    .055       0 1064.61      .1       0
 1378.87      .1       0 1483.63      .1       0
Bank Sta=744.3,809.93
XS Rating Curve= 0 ,0
Exp/Cntr(USF)=0,0
Exp/Cntr=0.3,0.1

Type RM Length L Ch R = 1 ,147271  ,295,293.5,290.4
XS GIS Cut Line= 4
2455540.75165842564156.5379168932455733.19595272564273.088686681
2456047.61198285564660.6877583022456562.60375633564999.498135592
#Sta/Elev= 30
       0 1785.69   119.2 1782.68   242.8 1784.44  255.431781.544   275.7 1768.78
   287.1    1765  368.96 1763.14   392.1 1761.27   409.4 1763.18   468.7 1762.77
   514.6 1759.56   589.4 1758.01   598.1 1758.96  602.561761.746   619.8 1779.67
   628.3  1784.2   659.6 1783.93   670.3 1787.58   706.9 1790.73   756.6 1798.17
   814.6 1813.26   873.6  1831.6   885.8 1833.36   935.9 1847.91  992.521869.598
  1023.5 1883.16  1144.4 1940.93  1210.2 1969.15  1292.8 1998.72  1340.5 2012.78
#Mann= 8 ,-1 , 0
       0     .05       0  255.43      .1       0  368.96      .1       0
   514.6    .045       0  602.56    .055       0   706.9      .1       0
  992.52    .055       0  1023.5      .1       0
Bank Sta=514.6,602.56
XS Rating Curve= 0 ,0
Exp/Cntr(USF)=0,0
Exp/Cntr=0.3,0.1