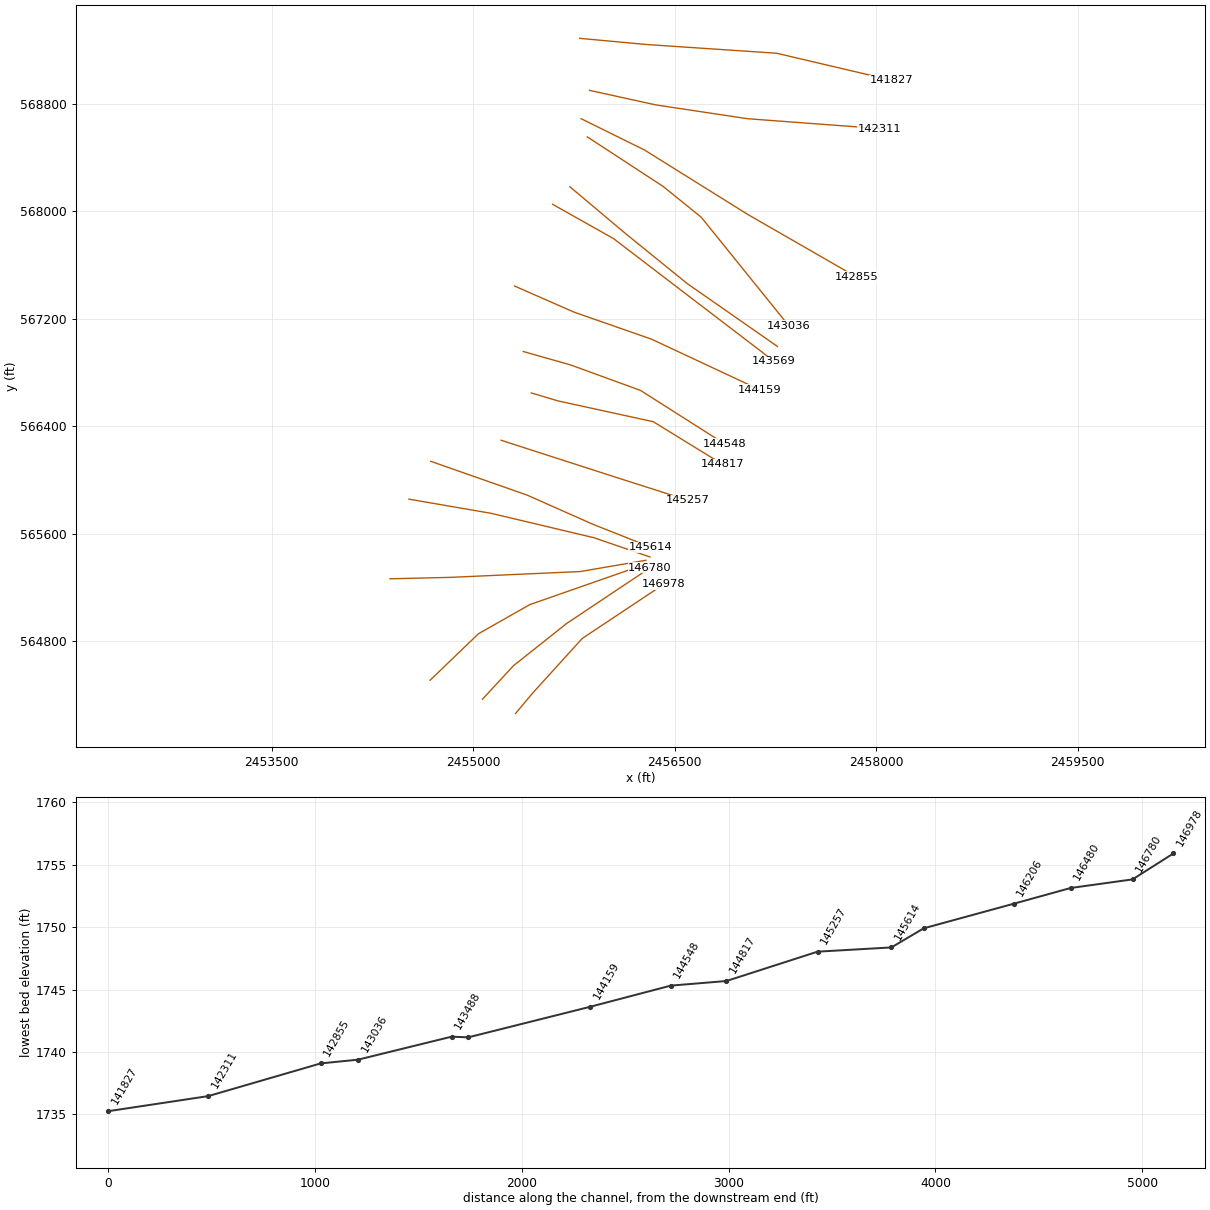
HEC-RAS study SFSBPOTOMC.prj: SFSBPOTOMC

--- SFSBPOTOMC.g01 (geometry) --- (continued)

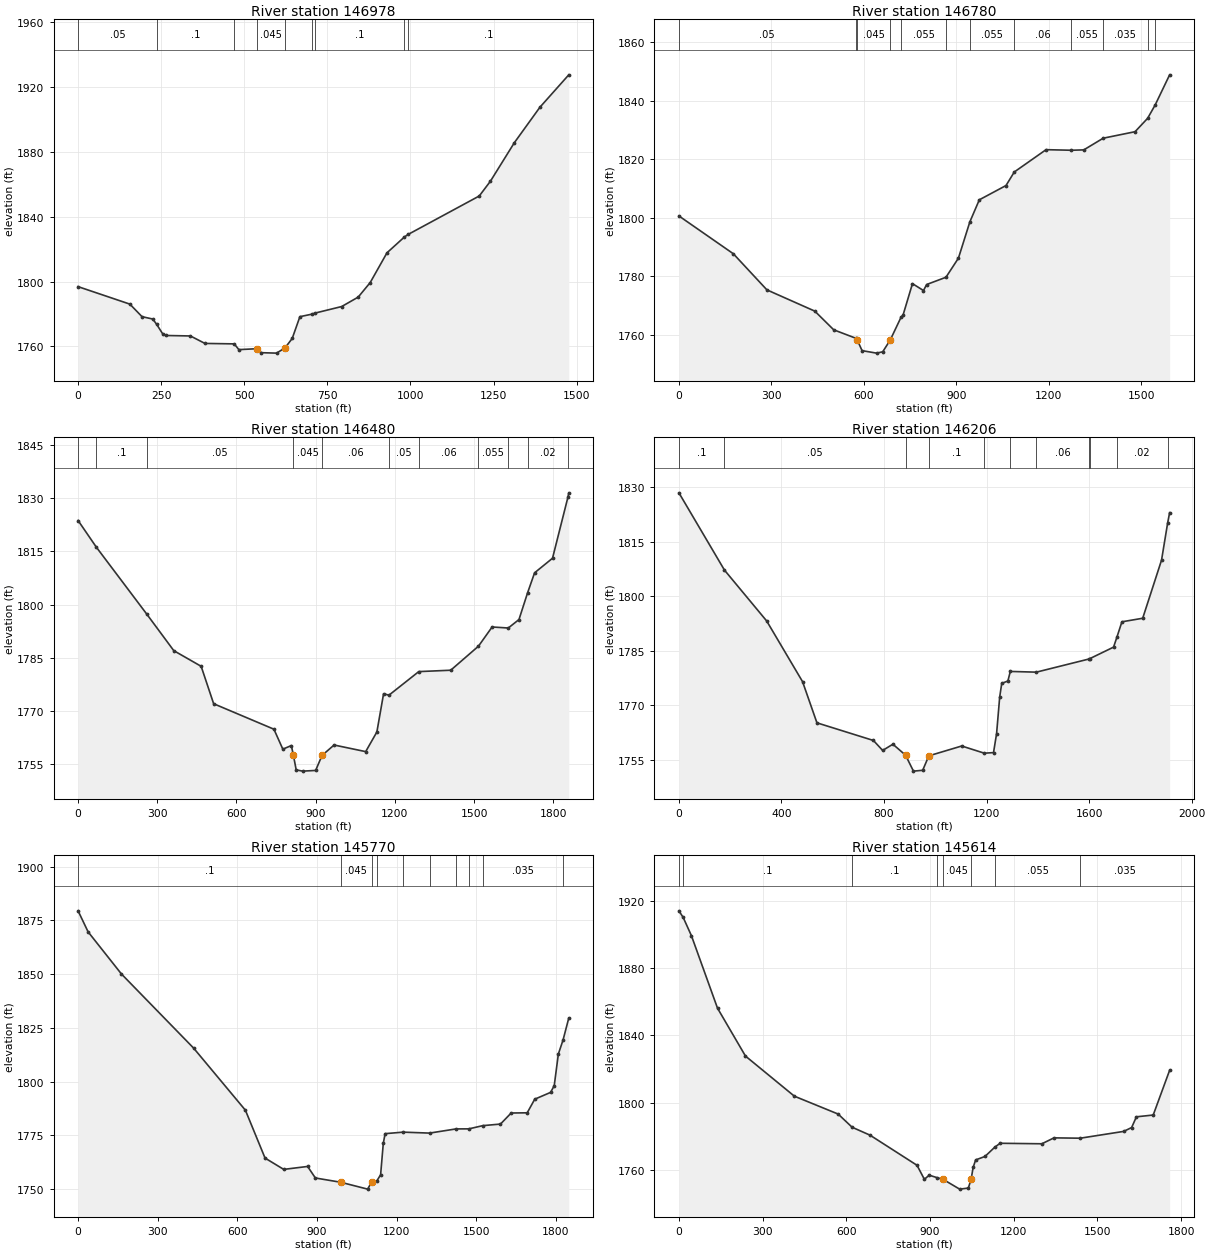
Type RM Length L Ch R = 1 ,146978  ,210.6,197.6,188.6
XS GIS Cut Line= 4
 2455315.7815679564259.5362715892455443.17426976564411.323320615
2455811.79996026564817.8957733642456418.94815636565221.757743095
#Sta/Elev= 30
       0 1796.89   155.8 1786.11   192.4 1778.37   224.6 1776.92  236.181773.715
   254.2  1767.9     263 1766.78     338 1766.48   381.6 1761.88  469.731761.605
   483.7 1758.06   537.4 1758.61   551.5 1756.17   597.1  1755.9  622.421759.093
   644.2 1764.95   667.3 1778.37  703.291779.922  713.771780.629   793.1 1784.63
   842.7 1790.44   878.8  1799.4   929.3 1817.75  981.881827.526  993.221829.113
  1206.9 1852.78  1240.5  1861.9  1312.4 1885.61  1389.4  1907.5  1476.2 1927.47
#Mann= 9 ,-1 , 0
       0     .05       0  236.18      .1       0  469.73      .1       0
   537.4    .045       0  622.42    .055       0  703.29     .06       0
  713.77      .1       0  981.88     .06       0  993.22      .1       0
Bank Sta=537.4,622.42
XS Rating Curve= 0 ,0
Exp/Cntr(USF)=0,0
Exp/Cntr=0.3,0.1

Type RM Length L Ch R = 1 ,146780  ,305,299.5,288.1
XS GIS Cut Line= 4
2455069.12761323564365.2451093042455299.51866979 564614.60954699
2455695.24919047564929.0255771162456315.94980166 565343.72947892
#Sta/Elev= 30
       0 1800.69   176.5 1787.77   285.4 1775.43   440.7 1768.17     502 1761.79
  572.85 1758.94  578.371758.304     594 1754.67   640.9 1753.82   660.9 1754.27
  685.331758.304  720.361766.073   726.8 1766.78   757.4 1777.56   793.2  1775.2
   803.4 1777.26  866.04 1779.74   906.5 1786.27  943.461798.644   974.2  1806.2
  1060.8 1811.08 1087.611815.704  1190.7 1823.33 1273.15 1823.13  1313.1 1823.26
 1375.911827.246  1479.3 1829.47 1520.061834.044 1544.571838.614  1591.4  1848.9
#Mann= 12 ,-1 , 0
       0     .05       0  572.85      .1       0  578.37    .045       0
  685.33    .035       0  720.36    .055       0  866.04     .06       0
  943.46    .055       0 1087.61     .06       0 1273.15    .055       0
 1375.91    .035       0 1520.06     .02       0 1544.57    .055       0
Bank Sta=578.37,685.33
XS Rating Curve= 0 ,0
Exp/Cntr(USF)=0,0
Exp/Cntr=0.3,0.1

Type RM Length L Ch R = 1 ,146480  ,295.1,274.9,243.3
XS GIS Cut Line= 4
 2454678.8180586564506.1902262572455039.31230003564853.132052603
2455421.49040562565069.9706940692456288.84497148565373.544792121
#Sta/Elev= 30
       0 1823.67    69.51816.132  260.821797.258   362.5 1787.04   466.2 1782.63
   513.5  1772.1   741.8 1764.93   775.6 1759.31   807.8 1760.33  815.691757.555
   826.2 1753.48   850.4 1753.13   899.8 1753.32  924.211757.556   969.7 1760.48
  1089.4 1758.62  1131.8 1764.15  1157.2 1774.92 1177.461774.501 1290.471781.141
  1411.5 1781.53  1516.51788.291  1568.3  1793.7 1629.511793.413    1670 1795.79
 1702.551803.301  1729.2 1808.95  1797.1 1813.05 1855.541830.262  1858.7 1831.46
#Mann= 11 ,-1 , 0
       0      .1       0    69.5      .1       0  260.82     .05       0
  815.69    .045       0  924.21     .06       0 1177.46     .05       0
 1290.47     .06       0  1516.5    .055       0 1629.51    .035       0
 1702.55     .02       0 1855.54    .055       0
Bank Sta=815.69,924.21
XS Rating Curve= 0 ,0
Exp/Cntr(USF)=0,0
Exp/Cntr=0.3,0.1

Type RM Length L Ch R = 1 ,146206  ,441.3,435.3,426.1
XS GIS Cut Line= 4
2454380.66492658 565262.414988372454833.31559064565273.256920443
2455798.24754516565316.6246487362456286.13448846565400.649622304
#Sta/Elev= 30
       0 1828.51  177.661807.227   342.2 1793.23   482.2 1776.51   538.3 1765.17
   758.6 1760.31   794.6 1757.57   834.6 1759.28  883.871756.267   914.7 1751.87
   950.7  1752.1   974.7 1756.08  1102.9 1758.79 1191.07 1756.81    1227 1756.97
    1239 1762.23    1251 1772.24    1259 1776.02    1283  1776.7 1292.521779.324
 1393.981779.127 1600.381782.766 1603.16 1782.87  1695.2 1786.02 1708.19 1788.75
  1727.7 1792.99  1808.8 1793.97  1882.3 1809.98 1906.151820.236  1913.8 1823.05
#Mann= 11 ,-1 , 0
       0      .1       0  177.66     .05       0  883.87    .045       0
   974.7      .1       0 1191.07     .06       0 1292.52     .05       0
 1393.98     .06       0 1600.38    .055       0 1603.16    .035       0
 1708.19     .02       0 1906.15    .035       0
Bank Sta=883.87,974.7
XS Rating Curve= 0 ,0
Exp/Cntr(USF)=0,0
Exp/Cntr=0.3,0.1

Type RM Length L Ch R = 1 ,145770  ,167.7,156.1,143.5
XS GIS Cut Line= 4
2454521.61004353565856.0107693832455134.17920567565750.301931669
2455898.53541684565568.6995694412456315.94980166565425.043969469
#Sta/Elev= 30
       0  1879.5    37.7 1869.72   163.5 1850.07   435.5 1815.54   630.4 1786.65
   704.4 1764.36   774.8 1759.09   864.8 1760.46     894 1755.09   989.9 1753.09
  1090.9  1749.9  1106.6 1753.32 1125.051753.625  1139.8 1756.59  1149.8 1771.15
  1156.7 1775.73 1224.631776.438 1324.211775.994 1423.981777.939 1472.261777.965
 1524.771779.463  1591.4  1780.2  1631.7 1785.35  1692.1 1785.44  1720.4 1791.78
  1780.2 1794.95  1793.9  1798.1  1809.4 1812.81 1827.111819.343  1848.7 1829.59
#Mann= 10 ,-1 , 0
       0      .1       0   989.9    .045       0  1106.6      .1       0
 1125.05     .06       0 1224.63    .055       0 1324.21     .06       0
 1423.98    .055       0 1472.26     .06       0 1524.77    .035       0
 1827.11    .055       0
Bank Sta=989.9,1106.6
XS Rating Curve= 0 ,0
Exp/Cntr(USF)=0,0
Exp/Cntr=0.3,0.1

Type RM Length L Ch R = 1 ,145614  ,349.9,357,362.1
XS GIS Cut Line= 4
2454684.23902463566137.9010032892455402.51702449565885.826082585
2455890.40396779565668.987441119 2456321.3707677565498.227010964
#Sta/Elev= 30
       0 1914.31   15.341910.368    44.9 1899.46   138.3 1856.27   238.6  1827.7
   413.9 1803.78   570.7 1793.13  620.681785.277     685 1780.54   853.4 1762.58
   879.7 1754.23     897 1756.67  926.261755.169  946.961754.178  1006.1 1748.37
  1037.2 1748.99 1047.211754.174  1054.5 1761.31  1063.5 1765.79    1097 1767.85
 1131.661773.324  1151.1 1775.71  1300.8 1775.41  1344.3 1778.94 1438.351778.736
    1594 1782.79  1622.5 1785.09  1639.7 1791.49  1699.9 1792.55  1758.7 1819.23
#Mann= 8 ,-1 , 0
       0      .1       0   15.34      .1       0  620.68      .1       0
  926.26      .1       0  946.96    .045       0 1047.21     .06       0
 1131.66    .055       0 1438.35    .035       0
Bank Sta=946.96,1047.21
XS Rating Curve= 0 ,0
Exp/Cntr(USF)=0,0
Exp/Cntr=0.3,0.1

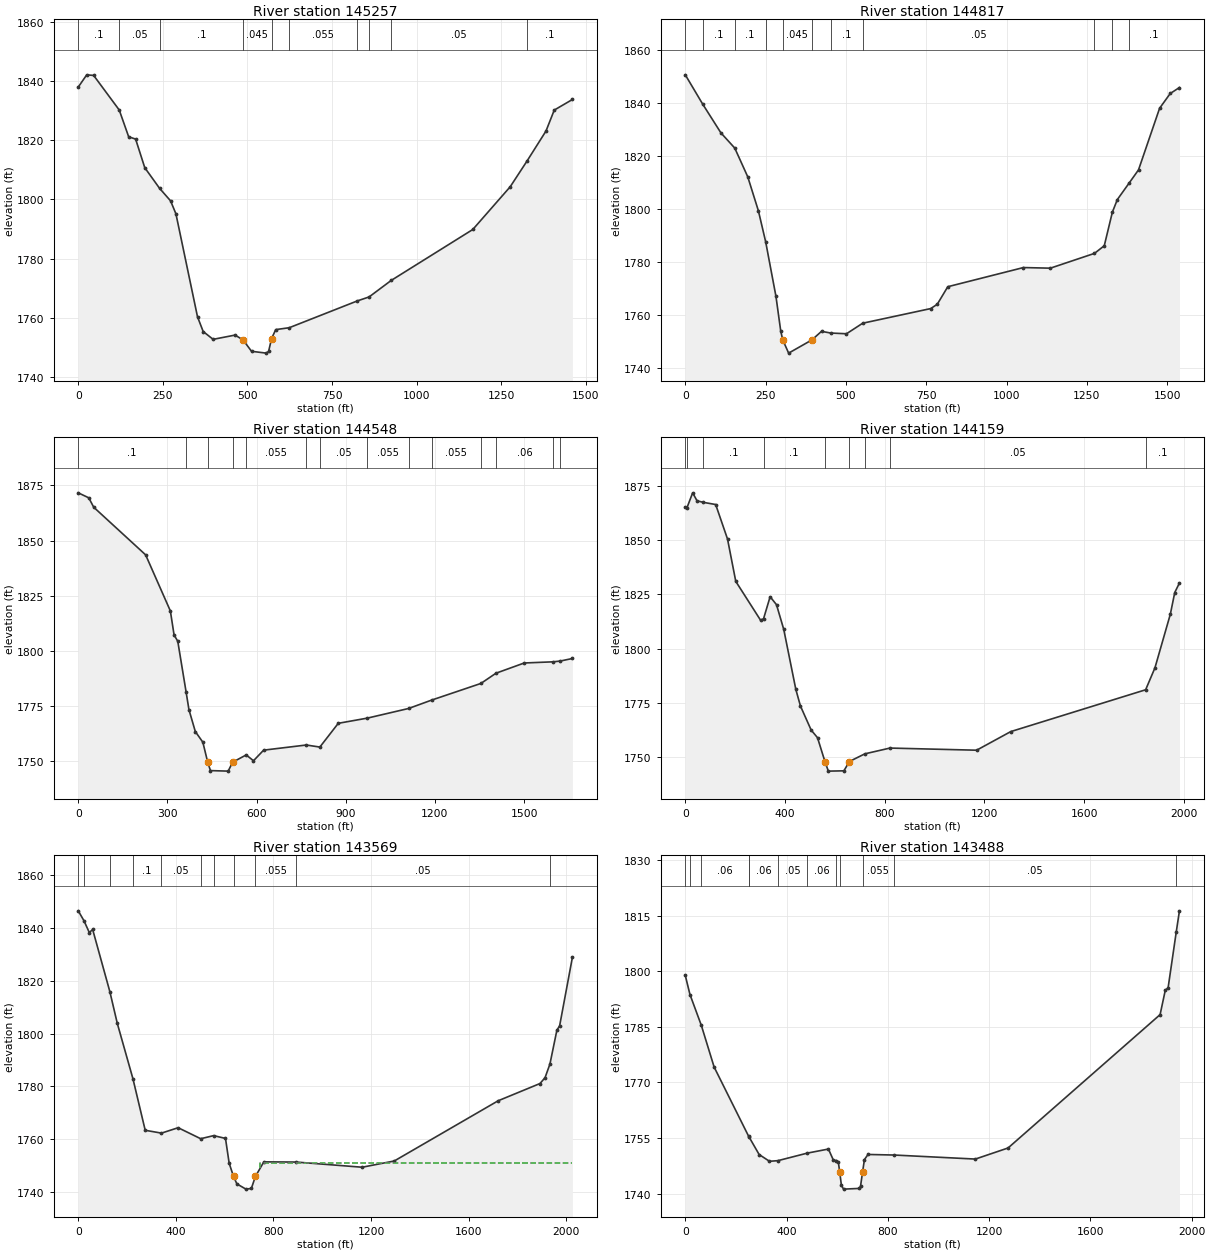
Type RM Length L Ch R = 1 ,145257  ,430.8,440.5,438.6
XS GIS Cut Line= 4
2455207.36224717566295.1090183522455483.83151504566205.663078747
2456080.13777907566013.2187844462456597.84003557565847.879320328
#Sta/Elev= 30
       0 1837.98    25.1 1842.12    45.6 1841.91  121.191830.218     149 1821.18
   169.6 1820.39   196.6 1810.73  240.461803.736   272.9 1799.51   288.7 1795.13
   352.5 1760.31   369.3 1755.33   398.7 1752.69   463.5 1754.13     487 1752.51
   512.2 1748.65   555.7 1748.03   562.6 1748.59  571.511752.962   583.7 1755.98
  623.541756.617  824.481765.664  859.71 1767.03  924.941772.602  1166.2 1789.83
  1276.8 1804.28 1326.621813.001  1382.6 1823.13    1407  1830.2  1460.6 1833.78
#Mann= 10 ,-1 , 0
       0      .1       0  121.19     .05       0  240.46      .1       0
     487    .045       0  571.51     .06       0  623.54    .055       0
  824.48     .05       0  859.71     .06       0  924.94     .05       0
 1326.62      .1       0
Bank Sta=487,571.51
XS Rating Curve= 0 ,0
Exp/Cntr(USF)=0,0
Exp/Cntr=0.3,0.1

Type RM Length L Ch R = 1 ,144817  ,273.2,269.1,261
XS GIS Cut Line= 4
2455432.33233769566647.4718107342455632.90808105566587.841184331
2456340.34414883566433.3436522872456855.33592231566116.217139142
#Sta/Elev= 30
       0  1850.7   53.881839.703     111 1828.78  154.02 1823.05   194.5 1812.19
   227.5 1799.41  250.161787.714   282.2 1767.12   297.1 1754.01  303.381750.671
   321.7 1745.68  394.191750.671     424  1753.9  452.78 1753.26   501.8 1752.99
  552.241756.969   763.9 1762.49   784.3 1764.11   817.1 1770.74  1052.5 1777.97
  1136.4 1777.74 1273.741783.321  1304.2  1786.2 1329.411798.875  1344.9 1803.63
 1381.171809.785  1410.8 1814.83  1476.4 1838.07  1509.6 1843.66  1538.2  1845.9
#Mann= 11 ,-1 , 0
       0     .05       0   53.88      .1       0  154.02      .1       0
  250.16      .1       0  303.38    .045       0  394.19     .06       0
  452.78      .1       0  552.24     .05       0 1273.74      .1       0
 1329.41      .1       0 1381.17      .1       0
Bank Sta=303.38,394.19
XS Rating Curve= 0 ,0
Exp/Cntr(USF)=0,0
Exp/Cntr=0.3,0.1

Type RM Length L Ch R = 1 ,144548  ,393.6,388.6,391.4
XS GIS Cut Line= 4
2455372.70171129566956.4668748242455725.06450367566856.179003146
2456245.47724319566666.4451918632456871.59882042566268.004188169
#Sta/Elev= 30
       0 1871.67    35.4  1869.4      52 1865.14   226.7  1843.5   309.9 1818.04
   322.4 1807.12   334.8 1804.28  362.85 1781.24   372.4 1773.22   393.8 1763.29
   419.2 1758.44  435.521749.349   444.8 1745.55   504.4 1745.31  519.311749.348
  565.041752.667   589.5 1750.02   623.6 1754.83  767.27 1757.17   812.81756.233
   874.8 1767.02   972.91769.386  1111.41773.755 1189.111777.575 1354.591785.123
 1405.321789.766  1500.4 1794.41 1597.78 1794.94 1621.531795.292  1662.4 1796.45
#Mann= 14 ,-1 , 0
       0      .1       0  362.85      .1       0  435.52    .045       0
  519.31     .06       0  565.04    .055       0  767.27     .06       0
   812.8     .05       0   972.9    .055       0  1111.4     .05       0
 1189.11    .055       0 1354.59     .05       0 1405.32     .06       0
 1597.78      .1       0 1621.53     .06       0
Bank Sta=435.52,519.31
XS Rating Curve= 0 ,0
Exp/Cntr(USF)=0,0
Exp/Cntr=0.3,0.1

Type RM Length L Ch R = 1 ,144159  ,604.3,589.8,572.7
XS GIS Cut Line= 4
2455307.65011885567444.3538181222455752.16933385567249.199040803
2456326.79173374567048.6232974472457131.80519018566671.866157899
#Sta/Elev= 30
       0 1865.08    6.311864.756    29.6 1871.74    47.1 1868.06    72.91867.347
   121.9 1866.36   169.4 1850.49   202.6 1830.97   302.2 1813.07  314.051813.778
   340.4 1823.91     366 1820.24   395.1 1808.86   443.6 1781.23   462.1 1773.59
   505.1 1762.52   530.6 1759.01  560.241748.048   574.1 1743.62   636.5 1743.76
  658.441748.049  720.361751.574  821.221754.239  1169.1 1753.25    1306 1761.82
 1847.271781.076  1884.6 1791.17  1946.4 1815.87  1964.1 1825.85  1982.9 1830.24
#Mann= 9 ,-1 , 0
       0    .055       0    6.31      .1       0    72.9      .1       0
  314.05      .1       0  560.24    .045       0  658.44      .1       0
  720.36    .055       0  821.22     .05       0 1847.27      .1       0
Bank Sta=560.24,658.44
XS Rating Curve= 0 ,0
Exp/Cntr(USF)=0,0
Exp/Cntr=0.5,0.3

Type RM Length L Ch R = 1 ,143569  ,82.3,81.2,79.5
XS GIS Cut Line= 4
2455591.23785332568053.2562928652456044.36285335567798.047959536
2456605.97148466567368.4602936212457240.22451091 566883.28383334
#Sta/Elev= 30
       0  1846.4   23.731842.608    45.3 1838.18    59.1 1839.34  129.541815.839
   160.1 1803.83  224.251782.885   274.5 1763.42  341.161762.346   409.6 1764.39
  501.951760.232  554.911761.396   603.6 1760.35   618.7 1750.95  636.481745.978
   650.3 1743.15   687.3 1741.17   709.6 1741.42  726.381745.977   760.8 1751.48
     8931751.407  1163.9 1749.45  1295.5 1751.81  1721.6 1774.59  1892.9  1781.1
  1913.6 1783.31 1933.591788.467  1962.1 1801.25  1973.4 1802.94  2025.7  1828.8
#Mann= 11 ,-1 , 0
       0      .1       0   23.73      .1       0  129.54     .06       0
  224.25      .1       0  341.16     .05       0  501.95    .055       0
  554.91     .06       0  636.48    .045       0  726.38    .055       0
     893     .05       0 1933.59      .1       0
#XS Ineff= 2 , 0
             616 1750.88     746         1750.88
Permanent Ineff=
       F       F
Bank Sta=636.48,726.38
XS Rating Curve= 0 ,0
Exp/Cntr(USF)=0,0
Exp/Cntr=0.5,0.3

Type RM Length L Ch R = 1 ,143488  ,450.8,452.1,451.1
XS GIS Cut Line= 4
2455719.64353767568184.3156821282456131.63695642567837.373855785
2456593.32118669 567462.63129288 2457264.6188581566994.413637102
#Sta/Elev= 30
       0 1798.85   18.431793.719   63.411785.382   113.9 1774.15   249.91755.512
  251.281755.354   291.7 1750.55   332.5 1748.73  365.631748.896  481.361750.925
   565.3 1752.03   585.2    1749  596.48 1748.94   604.4 1748.52  609.991745.809
   616.5 1742.29     625 1741.22   686.9 1741.41     692 1741.94  700.151745.811
   707.5 1749.19   721.7 1750.57  825.511750.415  1145.6 1749.33  1274.9 1752.32
  1875.3 1788.29  1895.8 1794.87  1906.9 1795.51 1939.161810.617  1951.7 1816.29
#Mann= 12 ,-1 , 0
       0      .1       0   18.43    .055       0   63.41     .06       0
   249.9     .05       0  251.28     .06       0  365.63     .05       0
  481.36     .06       0  596.48     .05       0  609.99    .045       0
  700.15    .055       0  825.51     .05       0 1939.16      .1       0
Bank Sta=609.99,700.15
XS Rating Curve= 0 ,0
Exp/Cntr(USF)=0,0
Exp/Cntr=0.5,0.3

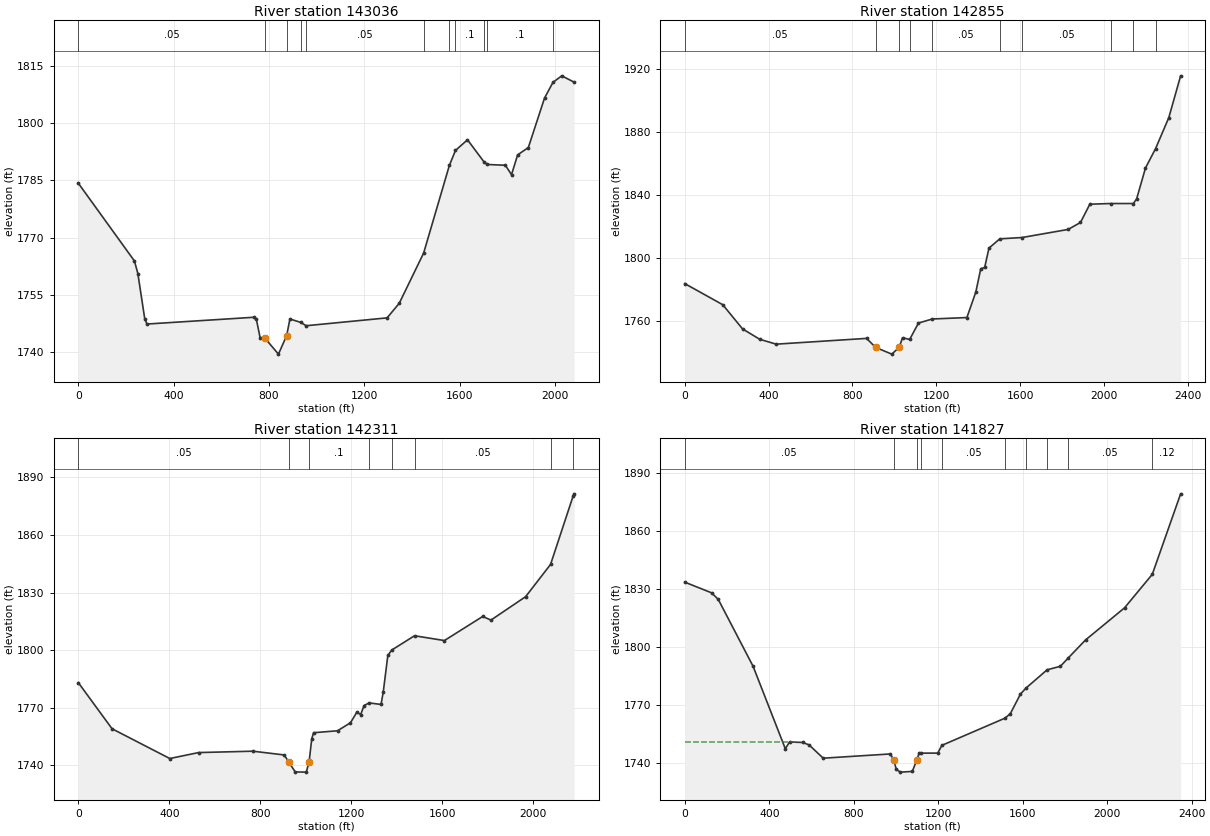
Type RM Length L Ch R = 1 ,143036  ,170.3,180.4,185.2
XS GIS Cut Line= 4
2455849.74672251568555.6518556362456413.52719033568187.026165144
2456698.12790725567956.6351085862457351.35431467567146.200686107
#Sta/Elev= 30
       0 1784.25   235.4 1763.84   249.8 1760.54   278.7 1748.66   287.9 1747.28
   737.4 1749.06   747.2 1748.49   762.7 1743.73   781.9 1743.64   839.8 1739.38
  874.351744.256   887.9 1748.61  933.021747.713  956.381746.838  1295.7  1748.9
  1346.7 1752.73 1449.171765.934 1557.14 1788.95 1582.641792.854  1633.1 1795.66
 1702.041789.881 1716.121789.171  1792.1 1788.97  1817.8 1786.49  1843.5 1791.69
  1888.5 1793.63  1956.5 1806.63 1991.86 1810.74  2028.7 1812.45  2080.7 1810.78
#Mann= 11 ,-1 , 0
       0     .05       0   781.9    .045       0  874.35     .06       0
  933.02    .055       0  956.38     .05       0 1449.17      .1       0
 1557.14     .05       0 1582.64      .1       0 1702.04     .05       0
 1716.12      .1       0 1991.86      .1       0
Bank Sta=781.9,874.35
XS Rating Curve= 0 ,0
Exp/Cntr(USF)=0,0
Exp/Cntr=0.3,0.1

Type RM Length L Ch R = 1 ,142855  ,514.9,544,559.6
XS GIS Cut Line= 4
 2455803.6685112568691.1760065522456275.29255639568458.074466976
2457047.78021661567975.6084897142457852.79367306567512.115893581
#Sta/Elev= 30
       0 1783.84   181.2 1770.44   275.6 1755.08   357.8 1748.49   436.2 1745.41
   867.6 1749.07  909.94 1743.37   987.6 1739.08 1022.76 1743.37  1038.9 1749.48
 1073.051748.406  1114.9 1758.79 1180.77 1761.38    1346  1762.3  1388.5 1778.45
  1412.1 1793.24  1430.9 1794.08  1451.3 1806.37 1502.971812.257 1609.161813.097
  1829.1 1818.23    1888 1822.64  1932.6 1834.25  2033.91834.678 2140.081834.671
  2155.7 1837.54  2198.2 1857.24 2246.271869.523  2309.5 1889.22  2365.8 1915.73
#Mann= 10 ,-1 , 0
       0     .05       0  909.94    .045       0 1022.76     .06       0
 1073.05    .055       0 1180.77     .05       0 1502.97    .055       0
 1609.16     .05       0  2033.9    .055       0 2140.08    .035       0
 2246.27      .1       0
Bank Sta=909.94,1022.76
XS Rating Curve= 0 ,0
Exp/Cntr(USF)=0,0
Exp/Cntr=0.3,0.1

Type RM Length L Ch R = 1 ,142311  ,480.1,484.7,487.1
XS GIS Cut Line= 4
2455866.00962062568902.5936819822456359.31752996568794.174361249
2457042.35925058568691.1760065532458023.55410321568617.992965058
#Sta/Elev= 30
       0 1783.09   148.3 1759.05   402.1 1743.55   528.6 1746.65   767.6 1747.37
     905 1745.41  923.961741.968   953.5 1736.56  1002.1 1736.46  1014.71741.971
  1026.3 1753.93  1034.4    1757  1139.6 1758.01  1196.5  1762.2  1224.3 1767.67
  1241.3 1766.47  1256.4 1771.17 1278.551772.526  1330.8 1771.73  1340.6  1778.3
  1360.7 1797.28 1378.241800.114 1477.931807.527  1609.4 1805.03  1777.8 1817.59
  1813.9 1815.69  1966.4 1827.89 2076.051844.705 2175.74 1880.52  2179.8 1881.49
#Mann= 8 ,-1 , 0
       0     .05       0  923.96    .045       0  1014.7      .1       0
 1278.55    .055       0 1378.24      .1       0 1477.93     .05       0
 2076.05     .12       0 2175.74      .1       0
Bank Sta=923.96,1014.7
XS Rating Curve= 0 ,0
Exp/Cntr(USF)=0,0
Exp/Cntr=0.3,0.1

Type RM Length L Ch R = 1 ,141827  ,545.4,542.5,538.1
XS GIS Cut Line= 4
2455792.82657913569290.192753603 2456291.5554545569244.114542291
2457259.19789204569179.0629498512458113.00004282568978.487206495
#Sta/Elev= 30
       0 1833.38   126.5 1827.89   158.6 1824.45   323.3 1789.93   475.9 1747.33
     496 1750.81   557.6 1750.58   588.2 1749.34   655.3 1742.45   973.1 1744.64
  989.331741.531  1001.5 1736.65  1021.2 1735.25  1077.3 1735.61 1098.571741.531
  1109.4 1745.05 1117.63 1745.06  1197.6 1745.08 1217.381749.085 1516.561763.153
  1541.4 1765.46  1589.4 1775.58 1616.121778.732 1715.68 1788.11  1778.4 1789.92
 1815.241794.177  1897.5 1803.53  2082.1 1820.11 2213.491837.412  2347.7 1879.01
#Mann= 10 ,-1 , 0
       0     .05       0  989.33    .045       0 1098.57      .1       0
 1117.63      .1       0 1217.38     .05       0 1516.56     .06       0
 1616.12     .05       0 1715.68     .06       0 1815.24     .05       0
 2213.49     .12       0
#XS Ineff= 2 , 0
          534.25  1750.7
Permanent Ineff=
       F       F
Bank Sta=989.33,1098.57
XS Rating Curve= 0 ,0
Exp/Cntr(USF)=0,0
Exp/Cntr=0.3,0.1