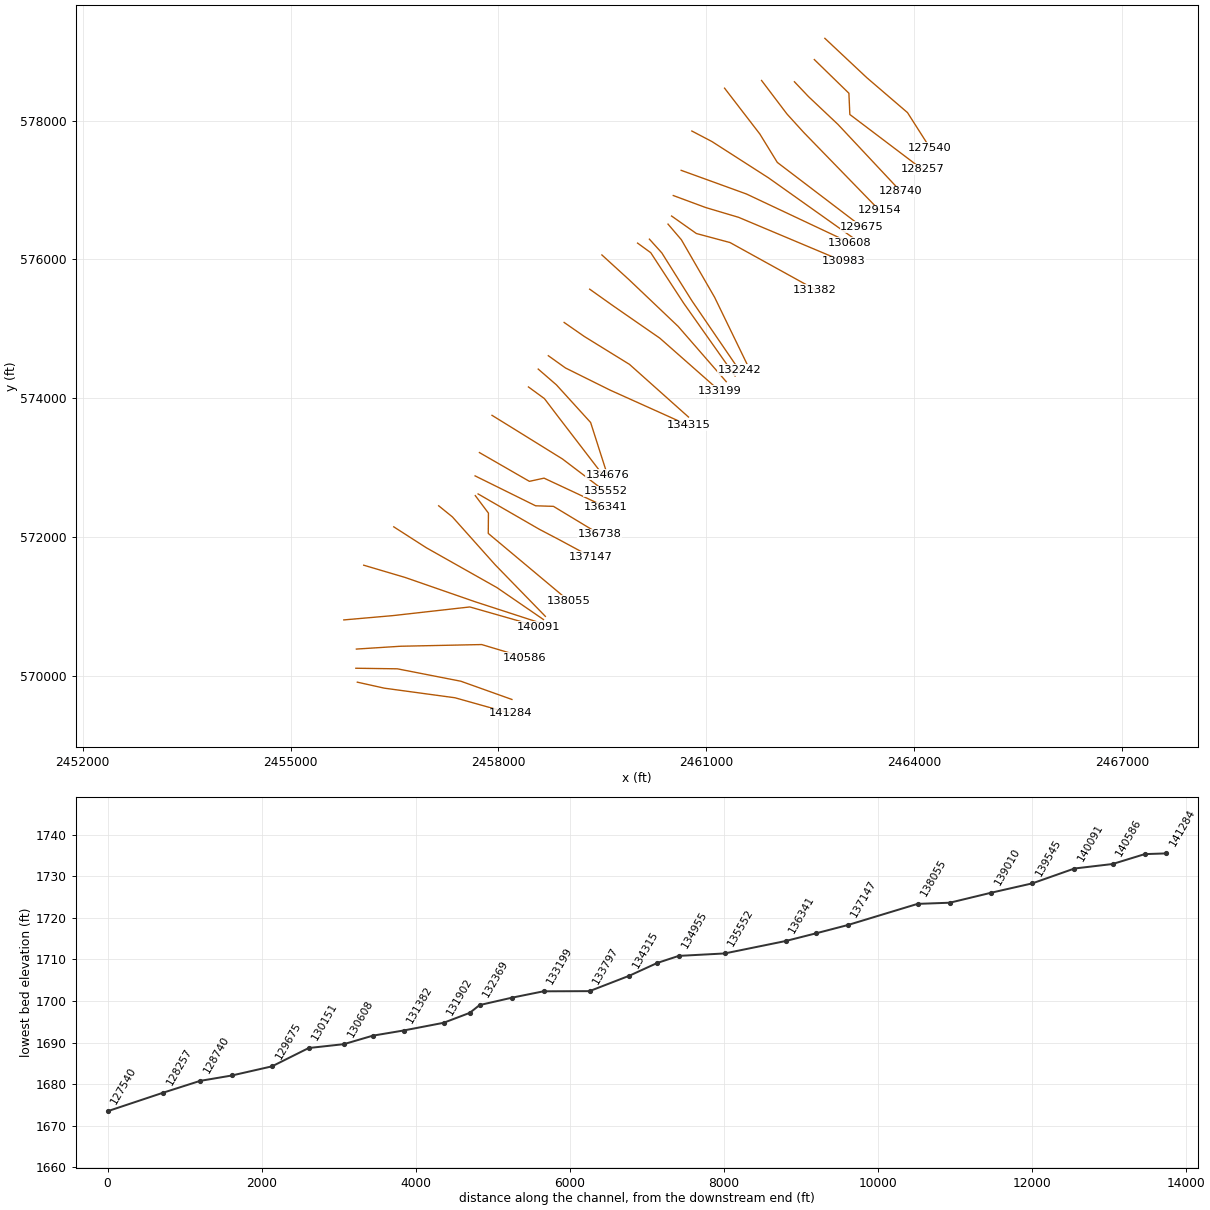
HEC-RAS study SFSBPOTOMC.prj: SFSBPOTOMC

--- SFSBPOTOMC.g01 (geometry) --- (continued)

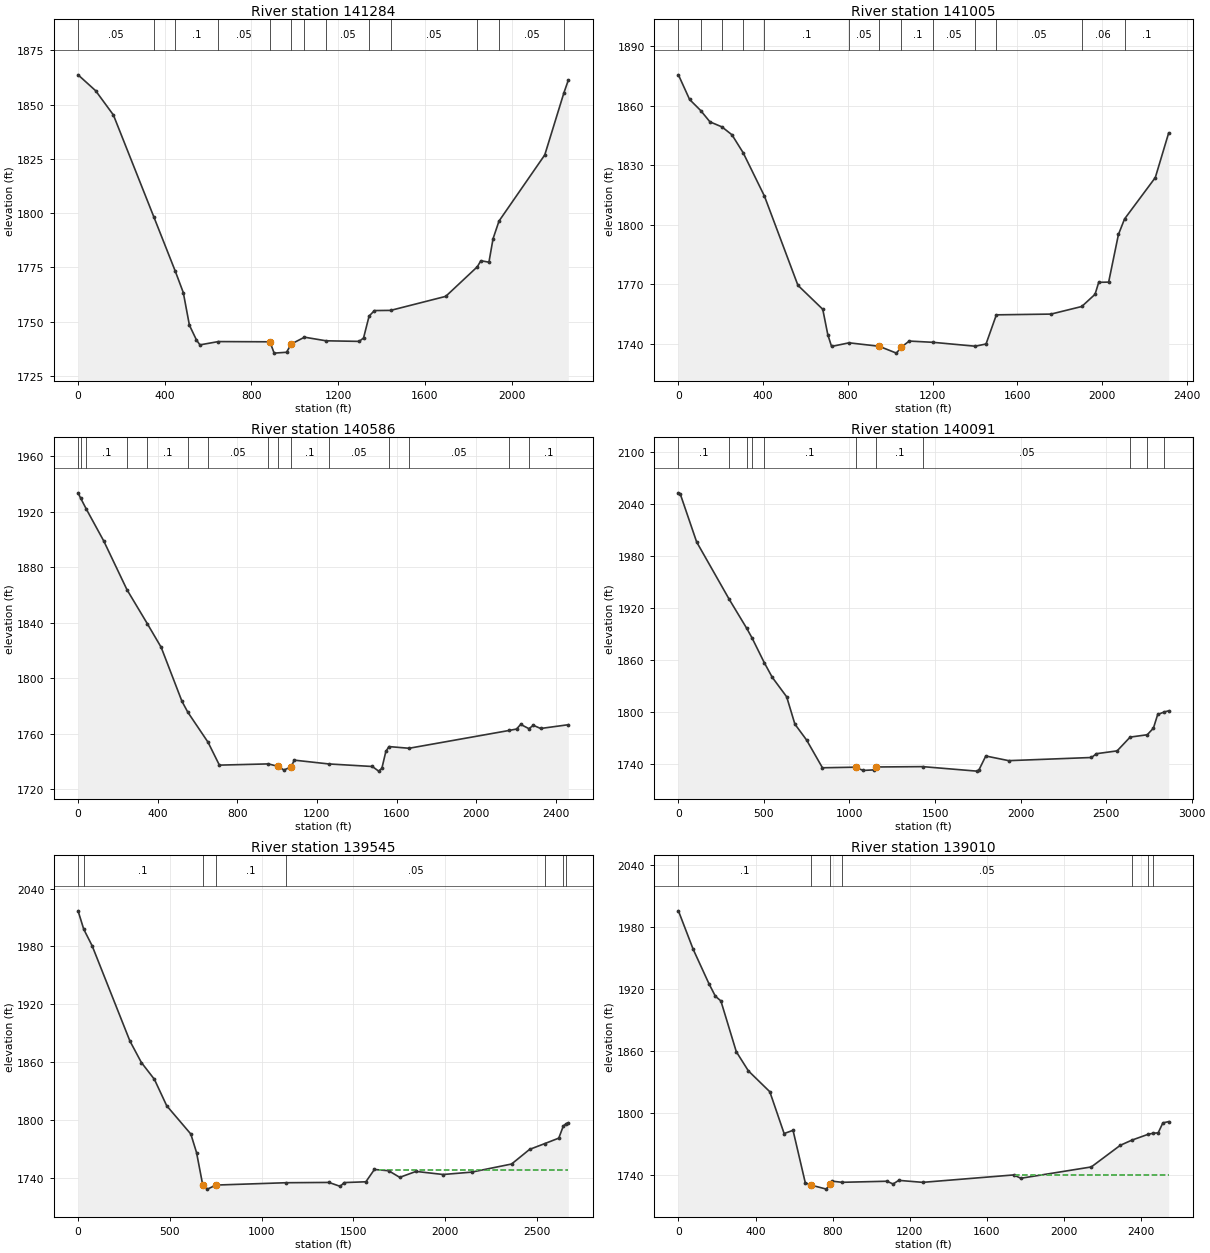
Type RM Length L Ch R = 1 ,141284  ,282,279.4,275.9
XS GIS Cut Line= 4
2455963.58700928569905.4723987632456353.89656392569818.736942176
2457373.03817881569680.5023082422458175.34115224569455.532217721
#Sta/Elev= 30
       0  1863.7    81.1 1856.38     163  1845.2  349.041798.364  448.451773.234
   485.5 1763.36   513.7 1748.33     546 1741.57   562.2 1739.27  647.161740.793
   885.1 1740.69   904.6 1735.47   961.8 1735.87   983.4 1739.66 1044.561742.817
 1143.911741.154  1296.8 1740.88    1317 1742.45 1342.611752.552  1367.3 1755.08
 1442.041755.163    1696 1761.62 1841.841775.264    1858 1778.04  1895.4 1777.38
  1914.4  1788.2  1941.81796.318  2152.9 1826.79 2241.651855.549  2261.6 1861.26
#Mann= 13 ,-1 , 0
       0     .05       0  349.04      .1       0  448.45      .1       0
  647.16     .05       0   885.1    .045       0   983.4      .1       0
 1044.56      .1       0 1143.91     .05       0 1342.61      .1       0
 1442.04     .05       0 1841.84     .06       0  1941.8     .05       0
 2241.65      .1       0
Bank Sta=885.1,983.4
XS Rating Curve= 0 ,0
Exp/Cntr(USF)=0,0
Exp/Cntr=0.3,0.1

Type RM Length L Ch R = 1 ,141005  ,409.8,418.2,426.4
XS GIS Cut Line= 4
2455941.90314514570106.0481421192456540.91989219570097.916693064
2457457.06315238569919.0248138542458194.31453337569656.107961077
#Sta/Elev= 30
       0 1875.52    52.8  1863.1  105.141857.531   148.9 1851.83  205.551849.286
   252.9  1845.3  305.951836.224  406.351814.395   564.4 1769.46   681.6  1757.4
   705.5 1744.59   723.2 1738.66  805.811740.494   947.6 1738.76  1029.4  1735.3
  1053.3 1738.38    1090 1741.38 1203.28 1740.74 1402.021738.778  1452.7 1739.91
 1501.381754.592  1759.5 1754.97  1904.81758.798  1967.5 1764.95  1984.7 1770.97
  2031.7 1771.09  2077.9 1795.07 2106.771802.908    2252 1823.75  2315.2 1846.28
#Mann= 13 ,-1 , 0
       0      .1       0  105.14     .05       0  205.55      .1       0
  305.95      .1       0  406.35      .1       0  805.81     .05       0
   947.6    .045       0  1053.3      .1       0 1203.28     .05       0
 1402.02      .1       0 1501.38     .05       0  1904.8     .06       0
 2106.77      .1       0
Bank Sta=947.6,1053.3
XS Rating Curve= 0 ,0
Exp/Cntr(USF)=0,0
Exp/Cntr=0.3,0.1

Type RM Length L Ch R = 1 ,140586  ,496.9,495.2,494.6
XS GIS Cut Line= 4
2455950.03459419570382.517409988 2456586.9981035570423.174655263
2457757.92676742570447.5690024282458384.04834465570260.545674163
#Sta/Elev= 30
       0 1933.65   12.571929.924   41.971921.797     129 1898.94  245.71 1863.77
  347.591839.344   417.6 1822.21   521.8 1783.33  551.33 1775.43  653.071753.741
     710 1737.25     9561738.132  1006.1 1736.31  1034.1 1733.72  1070.1 1735.96
  1086.1 1740.84 1258.941738.112  1478.2 1736.26  1510.2 1732.92  1526.2 1734.91
  1546.2 1747.11 1561.871750.623 1662.841749.411 2164.811762.235  2202.7 1763.28
  2223.6 1766.62 2264.971763.548    2287 1765.97  2323.8 1763.68  2462.9 1766.39
#Mann= 15 ,-1 , 0
       0      .1       0   12.57      .1       0   41.97      .1       0
  245.71      .1       0  347.59      .1       0  551.33      .1       0
  653.07     .05       0     956      .1       0  1006.1    .045       0
  1070.1      .1       0 1258.94     .05       0 1561.87      .1       0
 1662.84     .05       0 2164.81     .06       0 2264.97      .1       0
Bank Sta=1006.1,1070.1
XS Rating Curve= 0 ,0
Exp/Cntr(USF)=0,0
Exp/Cntr=0.3,0.1

Type RM Length L Ch R = 1 ,140091  ,552.3,546.8,531.8
XS GIS Cut Line= 4
2455768.43223196570802.6422778292456478.57878277 570864.98338725
2457587.16633726570989.665606093  2458584.624088570705.064889169
#Sta/Elev= 30
       0 2053.24    10.4 2052.14   106.7 1996.42  296.511930.407  398.971896.864
  430.761885.503  501.431857.257   548.4 1840.22   632.7 1817.69   680.9 1786.08
   749.3 1767.74   841.9 1735.72  1035.1 1736.39  1079.3 1732.63  1143.7 1733.29
 1154.38 1736.63 1428.211737.031  1743.5 1731.84  1755.6 1732.79  1796.6 1749.31
  1930.7 1743.93  2414.5 1747.59  2443.6 1751.97  2564.3 1755.23 2640.371771.136
 2740.371773.853  2776.4 1781.46  2801.4 1797.25 2840.381800.186  2865.7 1801.52
#Mann= 11 ,-1 , 0
       0      .1       0  296.51      .1       0  398.97      .1       0
  430.76      .1       0  501.43      .1       0  1035.1    .045       0
 1154.38      .1       0 1428.21     .05       0 2640.37     .06       0
 2740.37    .055       0 2840.38      .1       0
Bank Sta=1035.1,1154.38
XS Rating Curve= 0 ,0
Exp/Cntr(USF)=0,0
Exp/Cntr=0.3,0.1

Type RM Length L Ch R = 1 ,139545  ,534.2,534.1,529.9
XS GIS Cut Line= 4
2456055.74343191571591.3928361622456652.04969594 571415.21143997
2457660.34937876571065.5591306062458595.46602008570761.985032554
#Sta/Elev= 30
       0 2016.91   30.991997.822    76.9  1980.6   282.6  1881.9   345.1  1859.6
   416.1 1842.16   483.2 1814.75   614.6 1785.42   645.8 1766.19  679.431732.724
   705.1 1728.27   751.7 1732.48 1135.881734.921  1367.5 1735.21    1429 1731.12
  1450.2 1735.06  1568.8 1735.89  1615.3 1748.67    1693 1747.32  1753.3 1740.49
  1842.2 1746.63  1990.1 1743.44  2145.7 1745.92  2362.9 1754.31  2461.1 1769.48
 2544.591775.563  2620.1 1781.15 2645.081793.784 2659.741796.056  2672.2 1797.04
#Mann= 8 ,-1 , 0
       0      .1       0   30.99      .1       0  679.43    .045       0
   751.7      .1       0 1135.88     .05       0 2544.59    .035       0
 2645.08     .05       0 2659.74      .1       0
#XS Ineff= 2 , 0
                         1639.73         1748.43
Permanent Ineff=
       F       F
Bank Sta=679.43,751.7
XS Rating Curve= 0 ,0
Exp/Cntr(USF)=0,0
Exp/Cntr=0.3,0.1

Type RM Length L Ch R = 1 ,139010  ,553.2,536.9,524.5
XS GIS Cut Line= 4
2456489.42071484  572144.33137192456958.33427701571843.467756866
 2457977.4758919571268.8453569812458649.67568045570808.063243865
#Sta/Elev= 30
       0 1995.84    76.7 1958.48   158.7 1925.05   191.7 1913.04   220.2 1908.48
   300.2 1859.23   362.8 1840.67   473.9 1820.44   548.1 1779.92   594.3 1783.02
   657.7  1732.3   686.2    1730   767.3 1726.02  784.721730.687   798.6 1733.72
  847.631732.633  1081.1 1733.67  1113.2    1731  1142.2 1734.52  1266.9 1732.59
  1738.3 1739.78  1775.5 1736.55  2140.9 1747.53  2291.2 1768.52 2351.73 1773.55
 2436.431779.245 2461.511780.187  2487.6 1780.61    2512 1790.25  2542.1 1791.47
#Mann= 7 ,-1 , 0
       0      .1       0   686.2    .045       0  784.72      .1       0
  847.63     .05       0 2351.73    .055       0 2436.43    .035       0
 2461.51     .05       0
#XS Ineff= 2 , 0
                         1745.66         1739.73
Permanent Ineff=
       F       F
Bank Sta=686.2,784.72
XS Rating Curve= 0 ,0
Exp/Cntr(USF)=0,0
Exp/Cntr=0.3,0.1

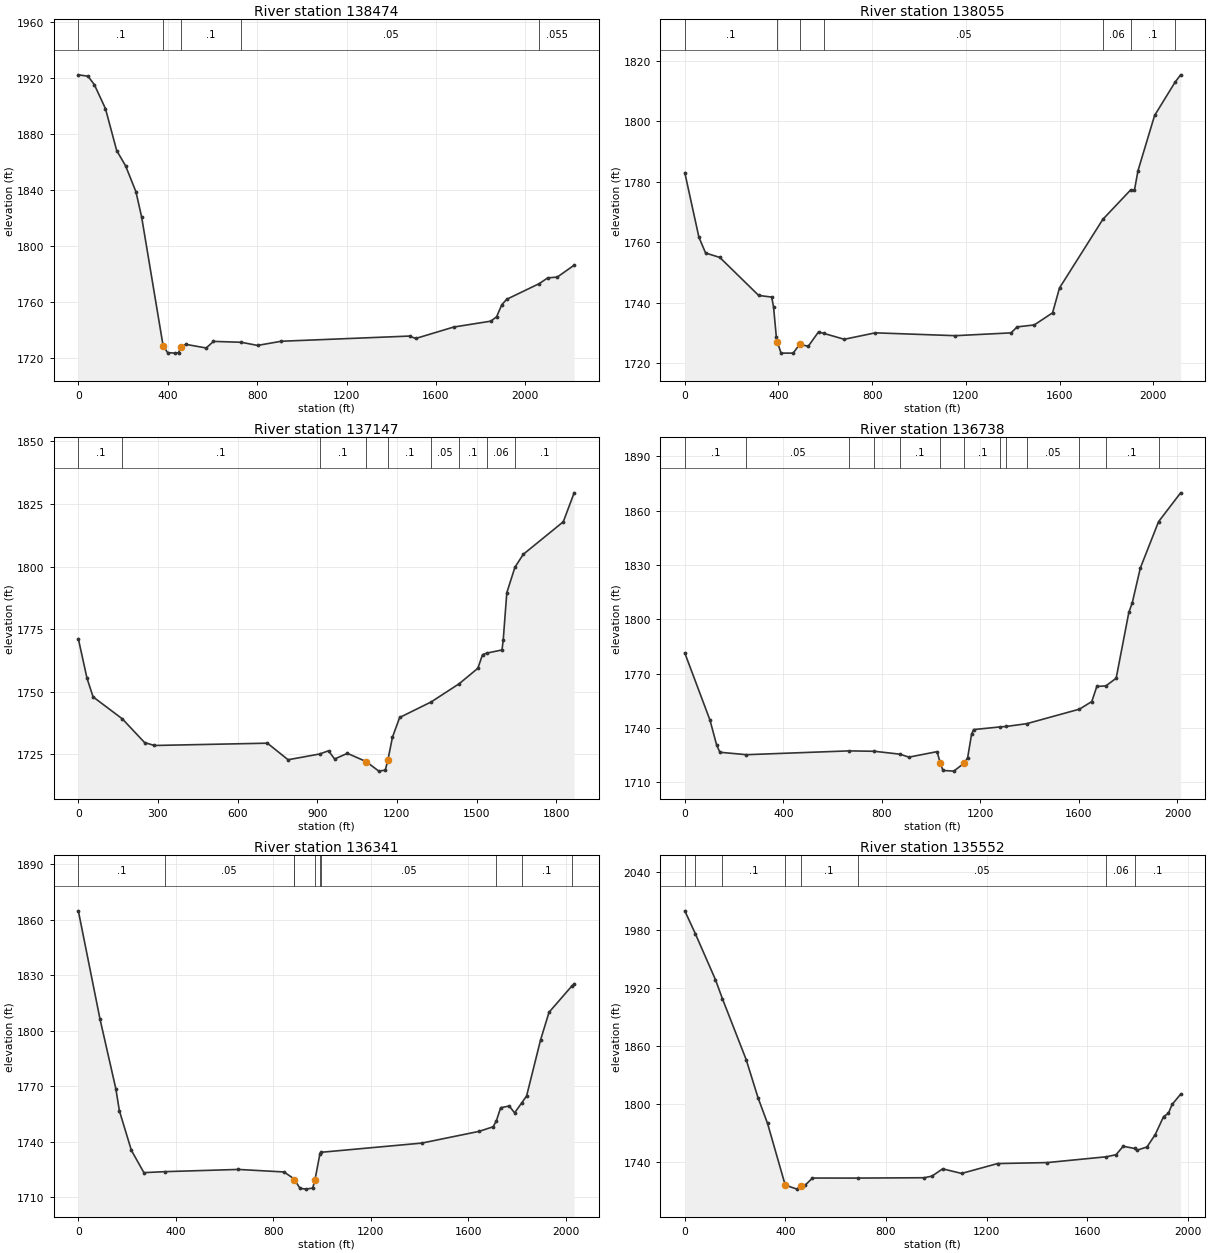
Type RM Length L Ch R = 1 ,138474  ,455.3,418.3,392.9
XS GIS Cut Line= 4
2457137.22615622572447.9054699532457335.09141656572287.986971871
2457953.08154474571596.8138021982458676.78051063570854.141455177
#Sta/Elev= 30
       0 1922.44    43.1 1921.46    71.6 1915.45   121.3 1898.32   171.7 1868.31
   211.6 1857.39   257.8 1838.88   283.3 1820.83  379.26 1728.97   399.4 1723.98
   433.9 1723.62     449 1724.01   457.9 1728.15   481.6 1729.88   572.2 1727.28
   604.7 1732.01  729.33 1731.37   801.7 1729.13     908  1732.1    1482 1735.81
  1509.4 1734.08  1679.1 1742.24    1846 1746.48  1871.5 1749.61  1894.7 1758.17
  1916.7 1762.08  2062.91773.324  2100.2 1777.39    2143 1777.94  2218.5 1786.46
#Mann= 5 ,-1 , 0
       0      .1       0  379.26    .045       0   457.9      .1       0
  729.33     .05       0  2062.9    .055       0
Bank Sta=379.26,457.9
XS Rating Curve= 0 ,0
Exp/Cntr(USF)=0,0
Exp/Cntr=0.3,0.1

Type RM Length L Ch R = 1 ,138055  ,851.9,908.5,946.4
XS GIS Cut Line= 4
2457665.77034479572594.2715529422457855.50415608572342.196632238
2457852.79367306572049.4644662592459010.16992188571081.822028716
#Sta/Elev= 30
       0 1783.01    60.2 1761.69    88.8 1756.44   149.4 1754.99   315.5 1742.41
   370.8 1741.88   378.8  1738.7   390.7 1728.76   394.8 1727.15   410.8 1723.34
   462.8 1723.35   490.8 1726.32   526.8 1725.58   570.8 1730.35  594.031729.851
   680.9 1727.92   813.1 1730.05  1154.8 1729.11  1392.9 1730.04  1418.9 1732.02
  1491.9 1732.66  1570.1 1736.67  1599.7 1744.89 1784.731767.584 1903.841777.341
  1919.5 1777.14  1934.7 1783.66  2005.7 1801.93 2092.821812.907  2116.8 1815.37
#Mann= 7 ,-1 , 0
       0      .1       0   394.8    .045       0   490.8      .1       0
  594.03     .05       0 1784.73     .06       0 1903.84      .1       0
 2092.82     .12       0
Bank Sta=394.8,490.8
XS Rating Curve= 0 ,0
Exp/Cntr(USF)=0,0
Exp/Cntr=0.3,0.1

Type RM Length L Ch R = 1 ,137147  ,384.8,408.6,420.9
XS GIS Cut Line= 4
2457706.42759007572618.6659001072458590.04505404572109.095092662
  2458880.066737571957.308043635 2459338.1383671571710.654088968
#Sta/Elev= 30
       0 1771.15    32.7 1755.35    55.6 1747.91  165.581739.144   249.7 1729.65
   286.6 1728.49   712.2 1729.41     790 1722.79  909.081725.086   942.3 1726.37
   965.4 1723.09  1013.4 1725.35    1084 1722.07  1131.8 1718.24  1156.3 1718.64
 1166.161722.782  1183.3 1731.85  1210.4 1739.68  1329.4 1745.92 1434.421753.166
  1504.9 1759.35  1522.4 1764.77 1539.52 1765.43  1595.7 1766.67  1600.3 1770.51
  1613.9 1789.55 1644.621799.755  1675.9 1804.89  1826.6 1817.89  1867.6 1829.47
#Mann= 9 ,-1 , 0
       0      .1       0  165.58      .1       0  909.08      .1       0
    1084    .045       0 1166.16      .1       0  1329.4     .05       0
 1434.42      .1       0 1539.52     .06       0 1644.62      .1       0
Bank Sta=1084,1166.16
XS Rating Curve= 0 ,0
Exp/Cntr(USF)=0,0
Exp/Cntr=0.3,0.1

Type RM Length L Ch R = 1 ,136738  ,386.5,397,411.8
XS GIS Cut Line= 4
2457663.05986177572878.8722698662458535.83539367572447.905469953
2458793.33128042572439.7740208972459462.82058594572035.912051167
#Sta/Elev= 30
       0 1781.45   102.3 1744.39     129  1730.8   142.4 1726.68  250.31 1725.34
  665.891727.439  769.78 1727.22  873.671725.616   909.7 1723.99  1024.3 1727.02
 1036.791720.807  1048.3 1716.65  1092.3 1716.27 1135.011720.805  1148.4 1723.75
  1164.4 1736.83  1172.4  1739.2 1281.091740.672 1305.731740.931 1388.131742.448
 1602.191750.465  1652.3 1754.66  1672.7    1763 1709.231763.278  1751.2 1767.52
  1802.6 1803.81  1816.6 1809.17  1849.3 1828.32  1923.31853.895  2012.9 1869.81
#Mann= 13 ,-1 , 0
       0      .1       0  250.31     .05       0  665.89      .1       0
  769.78      .1       0  873.67      .1       0 1036.79    .045       0
 1135.01      .1       0 1281.09     .05       0 1305.73      .1       0
 1388.13     .05       0 1602.19     .06       0 1709.23      .1       0
  1923.3      .1       0
Bank Sta=1036.79,1135.01
XS Rating Curve= 0 ,0
Exp/Cntr(USF)=0,0
Exp/Cntr=0.3,0.1

Type RM Length L Ch R = 1 ,136341  ,807.5,789.5,761.2
XS GIS Cut Line= 4
 2457725.4009712573214.9721641392458446.38945407572800.268262335
 2458657.8071295572846.3464736462459552.26652555572428.932088824
#Sta/Elev= 30
       0  1864.9    88.9 1806.41   153.8 1768.78   168.6 1756.74   217.8 1735.37
   269.2 1723.32  353.691723.854   657.2 1725.06   844.4 1723.69  884.82 1720.02
  886.871719.613   909.9 1714.84   934.5 1714.41     962 1714.99  971.531719.611
  991.57 1733.45  994.951734.314  1409.6  1739.3  1645.1 1745.65  1702.5 1748.12
 1715.98 1751.36  1733.4 1758.43  1768.7 1759.37  1790.7 1755.67  1819.21760.902
    1840 1764.81  1897.1 1794.98    1932 1810.04 2025.641824.244  2035.2 1825.33
#Mann= 10 ,-1 , 0
       0      .1       0  353.69     .05       0  884.82      .1       0
  886.87    .045       0  971.53      .1       0  991.57      .1       0
  994.95     .05       0 1715.98     .06       0  1819.2      .1       0
 2025.64      .1       0
Bank Sta=886.87,971.53
XS Rating Curve= 0 ,0
Exp/Cntr(USF)=0,0
Exp/Cntr=0.3,0.1

Type RM Length L Ch R = 1 ,135552  ,607.9,597.1,585.6
XS GIS Cut Line= 4
2457907.00333342573751.6478017672458175.34115224 573586.30833765
 2458923.4344653573122.8157415162459541.42459347572653.902179345
#Sta/Elev= 30
       0  1999.6   42.041975.846   121.9 1928.32  149.491908.623     244 1845.55
   291.2 1805.99   328.9 1779.49   399.2 1715.59   446.2 1711.43   460.4 1714.53
   479.2 1715.67   507.4 1722.91   687.11722.867     952 1723.23   982.6 1724.91
    1025 1732.44  1100.3 1727.69  1243.2  1737.9  1440.4 1738.91 1676.071744.941
  1714.3 1747.09  1742.8 1755.82 1788.541753.506  1797.1  1751.7  1837.3 1755.08
  1870.1 1767.93  1903.2 1786.54  1922.4 1789.93    1937 1799.06    1971 1809.76
#Mann= 8 ,-1 , 0
       0      .1       0   42.04      .1       0  149.49      .1       0
   399.2    .045       0   460.4      .1       0   687.1     .05       0
 1676.07     .06       0 1788.54      .1       0
#XS Ineff= 2 , 0
                         1030.14          1732.1
Permanent Ineff=
       F       F
Bank Sta=399.2,460.4
XS Rating Curve= 0 ,0
Exp/Cntr(USF)=0,0
Exp/Cntr=0.3,0.1

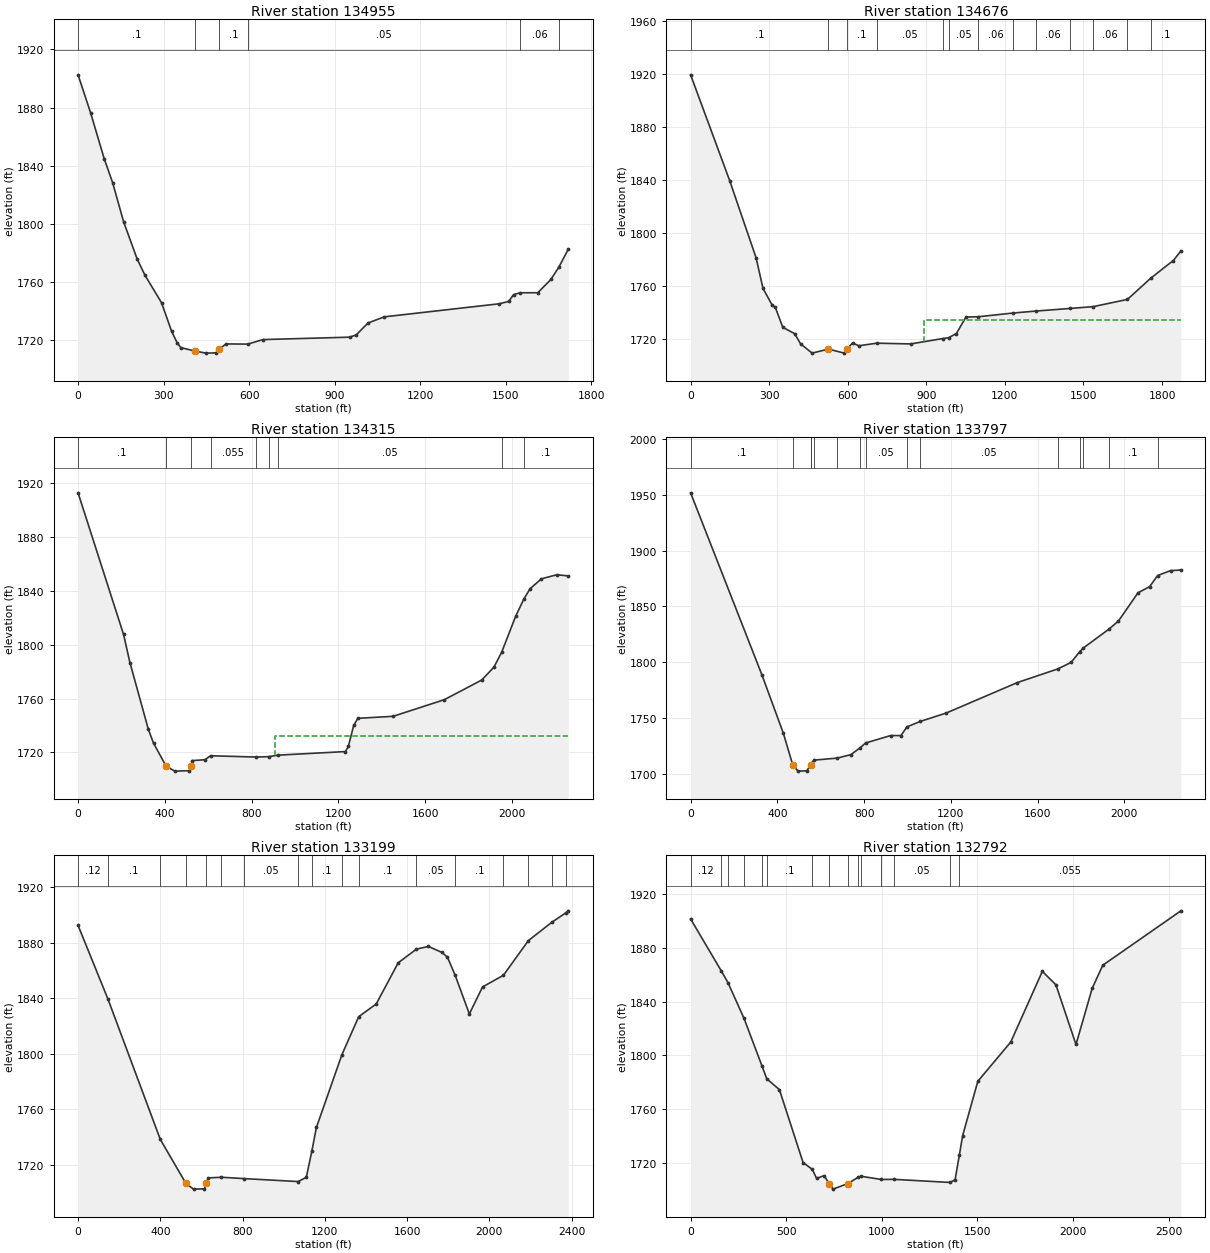
Type RM Length L Ch R = 1 ,134955  ,275.5,278.9,282.3
XS GIS Cut Line= 4
2458432.83703898574160.9307375352458663.22809554573992.880790398
2458852.96190682573743.5163527122459536.00362744572854.477922701
#Sta/Elev= 30
       0 1902.52    44.2 1876.25    91.5 1844.86   121.2 1828.31   159.6 1801.44
   207.1 1775.72   235.1 1764.34   292.7 1745.59   327.9    1726     348 1717.75
   360.5 1714.63   409.9 1712.28   448.5 1710.84   483.2    1711   493.7 1713.37
   518.9 1717.17  595.271717.057   648.7 1720.17   952.4 1721.83   975.7 1723.38
  1016.7 1731.56  1073.5 1735.82    1477 1744.82  1510.2 1746.43  1527.4 1751.08
 1549.851752.401  1612.5 1752.45  1658.5 1761.62 1686.221770.044  1719.6  1782.5
#Mann= 6 ,-1 , 0
       0      .1       0   409.9    .045       0   493.7      .1       0
  595.27     .05       0 1549.85     .06       0 1686.22      .1       0
Bank Sta=409.9,493.7
XS Rating Curve= 0 ,0
Exp/Cntr(USF)=0,0
Exp/Cntr=0.3,0.1

Type RM Length L Ch R = 1 ,134676  ,352,360.2,375.1
XS GIS Cut Line= 4
2458573.78215593574418.4266242762458836.69900871574190.746050736
2459330.00691804573648.6494470712459571.23990668572895.135167976
#Sta/Elev= 30
       0 1919.07   149.4 1839.15   249.8 1781.18   276.4 1757.99   310.9 1745.52
   323.6 1743.57     352  1728.6   397.3 1723.82   419.9 1716.17   463.8 1709.14
   526.1 1712.19   585.6  1709.2  597.371712.305   618.3 1716.75   642.1  1714.7
  710.52 1716.63   839.8 1716.09  964.291720.164  984.881720.774  1014.6 1723.88
  1051.4 1736.36 1098.741736.592 1231.591739.398 1317.791740.864  1449.71742.856
 1536.841744.199 1667.81 1749.66 1755.891765.521  1842.8 1778.99  1871.9 1786.19
#Mann= 13 ,-1 , 0
       0      .1       0   526.1    .045       0  597.37      .1       0
  710.52     .05       0  964.29     .06       0  984.88     .05       0
 1098.74     .06       0 1231.59     .05       0 1317.79     .06       0
  1449.7     .05       0 1536.84     .06       0 1667.81    .055       0
 1755.89      .1       0
#XS Ineff= 2 , 0
                          890.82         1733.78
Permanent Ineff=
       F       F
Bank Sta=526.1,597.37
XS Rating Curve= 0 ,0
Exp/Cntr(USF)=0,0
Exp/Cntr=0.3,0.1

Type RM Length L Ch R = 1 ,134315  ,523.6,518.8,514
XS GIS Cut Line= 4
2458720.14823892574610.8709185772458966.80219359574434.689522386
2459611.89715195574114.8525262232460739.45808757573607.992201796
#Sta/Elev= 30
       0 1912.77   209.6 1807.65   239.1 1786.66   323.8 1737.22   347.7 1726.87
   405.81709.778   445.9 1706.09   512.9 1706.41  520.47 1709.78   526.8  1713.9
   584.3 1714.56  610.661717.498  818.551716.558  877.631716.812   922.51717.967
  1232.4 1720.62  1245.5 1724.45  1270.3 1740.07  1289.4  1745.3  1451.7  1746.8
  1687.9 1759.15  1860.3 1773.76  1916.5 1783.33 1951.761794.278  2017.4 1821.39
 2054.581833.984  2083.2 1841.61  2135.2 1848.91    2206 1851.92  2259.4 1851.06
#Mann= 9 ,-1 , 0
       0      .1       0   405.8    .045       0  520.47      .1       0
  610.66    .055       0  818.55     .05       0  877.63     .06       0
   922.5     .05       0 1951.76      .1       0 2054.58      .1       0
#XS Ineff= 2 , 0
                          905.71         1731.85
Permanent Ineff=
       F       F
Bank Sta=405.8,520.47
XS Rating Curve= 0 ,0
Exp/Cntr(USF)=0,0
Exp/Cntr=0.3,0.1

Type RM Length L Ch R = 1 ,133797  ,600.1,597.3,597.7
XS GIS Cut Line= 4
2458947.82881246575090.6264128212459240.56097844574887.340186446
2459891.07690284574486.1886997342460742.16857059573727.253454603
#Sta/Elev= 30
       0 1951.88   329.5 1788.38   428.1 1736.12  470.741708.093   495.2 1702.37
   535.6 1702.62  554.541708.096  555.631708.574  567.81 1712.21  675.271714.031
   739.6 1717.19  782.731723.464  806.961727.599   922.2 1734.26   969.9 1734.24
  997.651742.048  1058.31746.868  1179.2 1754.49  1506.1 1781.72 1692.511793.953
  1754.5 1799.82 1794.381809.392 1810.281812.681 1928.061829.492  1972.7 1836.87
  2063.2 1862.26  2117.2 1867.82 2153.521877.712  2213.4 1882.15    2261 1882.67
#Mann= 15 ,-1 , 0
       0      .1       0  470.74    .045       0  554.54      .1       0
  555.63     .06       0  567.81    .055       0  675.27      .1       0
  782.73      .1       0  806.96     .05       0  997.65      .1       0
  1058.3     .05       0 1692.51      .1       0 1794.38     .05       0
 1810.28      .1       0 1928.06      .1       0 2153.52      .1       0
Bank Sta=470.74,554.54
XS Rating Curve= 0 ,0
Exp/Cntr(USF)=0,0
Exp/Cntr=0.3,0.1

Type RM Length L Ch R = 1 ,133199  ,415,406.9,398.9
XS GIS Cut Line= 4
2459316.45450295575570.3819070642459652.55439722575331.859401452
2460330.17515181574862.9458392812461192.10875163 574104.01059415
#Sta/Elev= 30
       0  1892.4  145.371839.294  400.091738.144  524.631706.411   561.5 1702.33
   614.2 1702.53  622.951706.406   633.7 1710.41  696.951710.888  806.961709.919
 1070.711707.783  1110.1 1710.86 1136.991729.644  1159.2 1746.74 1283.341799.236
 1365.03 1826.61  1450.1 1835.72  1557.1 1865.43 1646.021875.299  1704.3  1877.2
  1769.9 1872.88  1796.5 1869.52 1834.271856.366  1903.1 1828.57  1967.1    1848
 2068.881856.436 2190.021881.384  2303.51894.551 2371.361901.319  2384.6 1902.87
#Mann= 17 ,-1 , 0
       0     .12       0  145.37      .1       0  400.09      .1       0
  524.63    .045       0  622.95     .06       0  696.95      .1       0
  806.96     .05       0 1070.71      .1       0 1136.99      .1       0
 1283.34     .12       0 1365.03      .1       0 1646.02     .05       0
 1834.27      .1       0 2068.88      .1       0 2190.02      .1       0
  2303.5      .1       0 2371.36      .1       0
Bank Sta=524.63,622.95
XS Rating Curve= 0 ,0
Exp/Cntr(USF)=0,0
Exp/Cntr=0.3,0.1

Type RM Length L Ch R = 1 ,132792  ,434.8,422.9,410.4
XS GIS Cut Line= 4
2459492.63589914  576063.68981642459888.36641982575703.195574962
2460593.09200458575033.7062694362461286.97565727574236.824262048
#Sta/Elev= 30
       0 1901.29  161.011862.601  195.771853.914   279.61827.423  372.451792.533
  398.181782.734   464.5 1774.58   588.2 1720.56  636.761715.457   658.9 1708.73
   698.4 1710.88  723.931704.982   744.8 1700.81  823.031704.981  877.271709.698
  891.321710.364  997.521707.963 1062.631708.072 1358.281705.763  1383.2 1707.84
 1405.241725.916  1422.8 1740.59    1502  1780.8  1674.3 1809.98  1839.4 1862.39
  1910.3 1852.43  2015.4 1808.13  2100.2 1849.83  2155.5 1866.94    2564  1907.3
#Mann= 15 ,-1 , 0
       0     .12       0  161.01      .1       0  195.77     .12       0
   279.6      .1       0  372.45     .12       0  398.18      .1       0
  636.76     .05       0  723.93    .045       0  823.03      .1       0
  877.27     .06       0  891.32    .055       0  997.52      .1       0
 1062.63     .05       0 1358.28      .1       0 1405.24    .055       0
Bank Sta=723.93,823.03
XS Rating Curve= 0 ,0
Exp/Cntr(USF)=0,0
Exp/Cntr=0.5,0.3

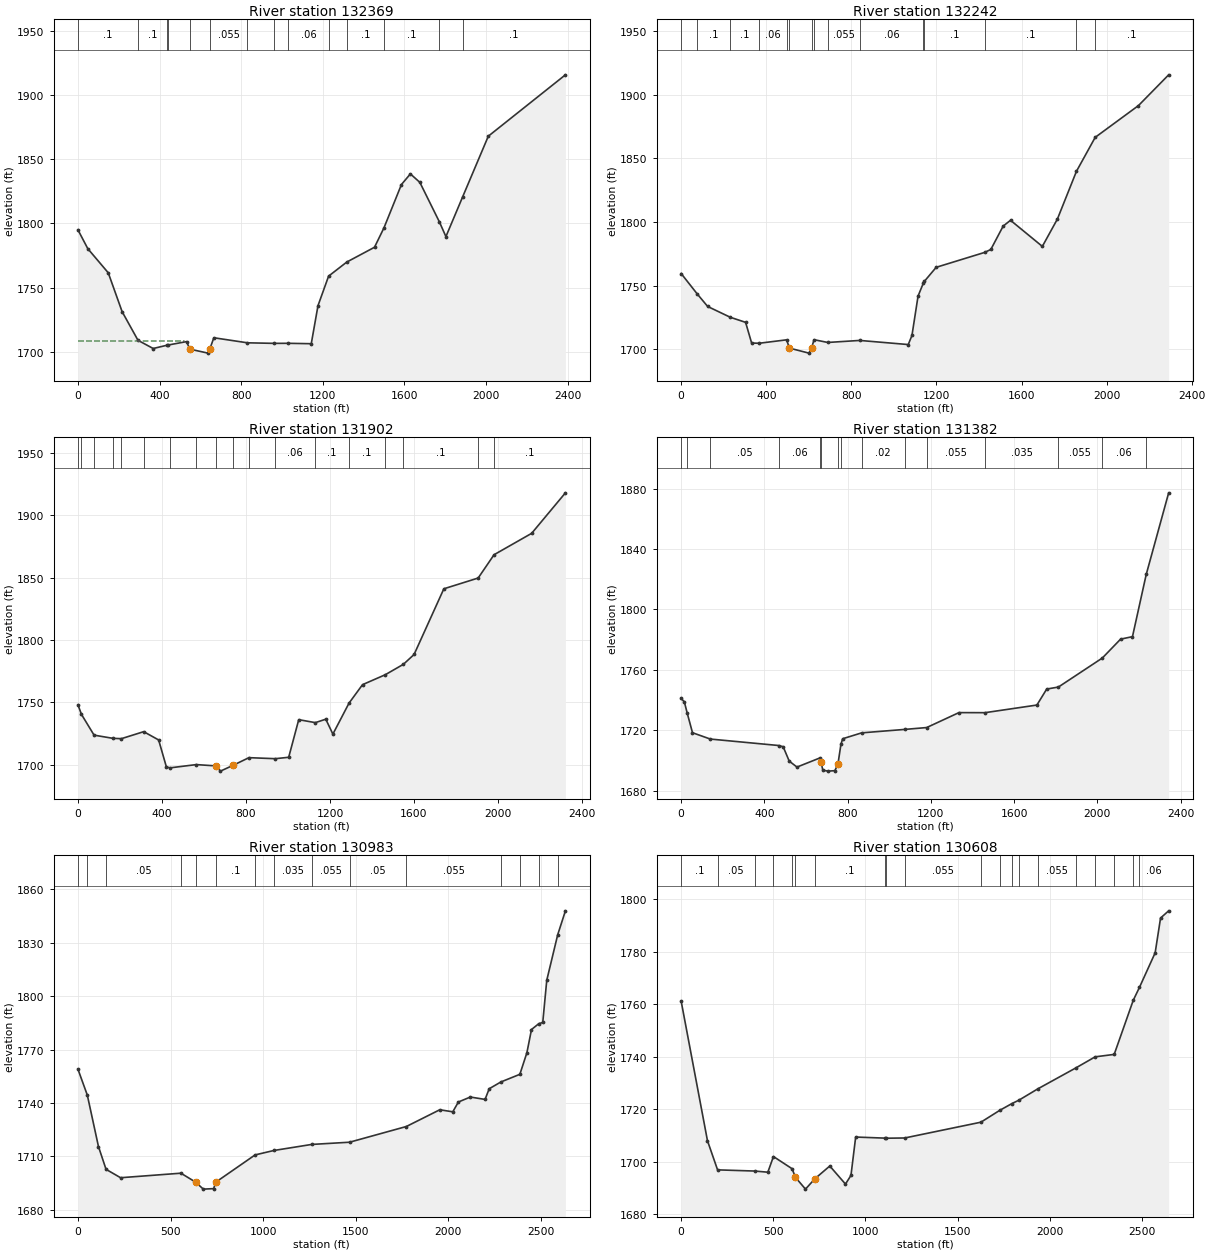
Type RM Length L Ch R = 1 ,132369  ,129.6,127.8,128.8
XS GIS Cut Line= 4
2460007.62767263576234.4502465542460197.36148391 576096.21561262
2460671.69601212575369.8061637082461414.36835914574318.138752598
#Sta/Elev= 30
       0    1795    48.4 1780.32   148.7 1761.53   216.6 1731.31  294.591708.983
     369 1702.62  437.621705.202  442.011705.323   532.5 1707.98  548.761702.121
   637.6 1699.02  646.291702.117   666.3 1710.98  831.161707.049  962.33 1706.62
 1031.671706.657  1143.9 1706.35  1176.9 1735.98 1228.921758.948 1318.041769.896
  1453.9 1781.41 1500.341796.537  1585.9 1830.21  1629.8 1838.49  1676.2  1831.9
 1771.761801.226    1804  1789.7 1885.441820.421  2011.8 1867.84  2389.8 1915.59
#Mann= 14 ,-1 , 0
       0      .1       0  294.59      .1       0  437.62     .05       0
  442.01     .06       0  548.76    .045       0  646.29    .055       0
  831.16     .06       0  962.33    .055       0 1031.67     .06       0
 1228.92      .1       0 1318.04      .1       0 1500.34      .1       0
 1771.76      .1       0 1885.44      .1       0
#XS Ineff= 2 , 0
             520 1708.48     686         1708.48
Permanent Ineff=
       F       F
Bank Sta=548.76,646.29
XS Rating Curve= 0 ,0
Exp/Cntr(USF)=0,0
Exp/Cntr=0.5,0.3

Type RM Length L Ch R = 1 ,132242  ,344.1,340.1,335
XS GIS Cut Line= 4
2460178.38810278576291.3703899392460357.27998199576093.505129601
2460793.66774794 575399.621476912461473.99898554574404.874209184
#Sta/Elev= 30
       0 1759.67   76.461743.439   124.7 1733.78  231.25 1725.29   302.9 1721.33
   331.3 1705.06  366.331704.902  495.551707.591  509.151701.086   600.6 1697.15
  612.731701.089  624.761707.693  689.281705.533  839.531707.118  1067.5 1703.88
  1084.9 1711.01  1113.6 1741.96 1137.831751.867 1143.571753.581  1198.8 1764.54
 1425.971776.209  1455.6 1778.54  1513.7 1796.91  1548.2 1801.47  1697.8 1780.96
  1768.6 1802.45 1858.19 1839.94 1946.281866.605  2149.7 1891.56  2291.6  1915.7
#Mann= 15 ,-1 , 0
       0      .1       0   76.46      .1       0  231.25      .1       0
  366.33     .06       0  495.55    .055       0  509.15    .045       0
  612.73      .1       0  624.76    .035       0  689.28    .055       0
  839.53     .06       0 1137.83      .1       0 1143.57      .1       0
 1425.97      .1       0 1858.19     .12       0 1946.28      .1       0
Bank Sta=509.15,612.73
XS Rating Curve= 0 ,0
Exp/Cntr(USF)=0,0
Exp/Cntr=0.5,0.3

Type RM Length L Ch R = 1 ,131902  ,488.7,519.2,553.4
XS GIS Cut Line= 4
2460446.72592159576508.2090314052460639.17021589576283.238940884
2461118.92571014575453.8311372762461585.12878929574494.320148789
#Sta/Elev= 30
       0 1747.98   16.951740.246   76.961723.607  166.731721.058  207.081720.792
  313.171726.399   384.3 1719.76   421.2 1698.14  438.441697.382  563.721699.998
   656.9 1698.95   678.7 1694.76  740.661699.574  814.261705.556  939.541704.736
  1003.5 1705.86  1051.3 1736.02 1130.43 1733.65  1180.1  1736.4  1213.9 1724.45
 1290.691749.284    1355 1764.09 1463.31 1772.06 1549.521780.414  1600.5  1788.3
  1742.2 1840.97 1905.581849.599 1981.171868.276  2160.3 1885.45    2321 1917.92
#Mann= 18 ,-1 , 0
       0      .1       0   16.95      .1       0   76.96     .06       0
  166.73      .1       0  207.08     .06       0  313.17      .1       0
  438.44     .06       0  563.72      .1       0   656.9    .045       0
  740.66     .06       0  814.26    .055       0  939.54     .06       0
 1130.43      .1       0 1290.69      .1       0 1463.31      .1       0
 1549.52      .1       0 1905.58     .12       0 1981.17      .1       0
Bank Sta=656.9,740.66
XS Rating Curve= 0 ,0
Exp/Cntr(USF)=0,0
Exp/Cntr=0.3,0.1

Type RM Length L Ch R = 1 ,131382  ,399,399,391.9
XS GIS Cut Line= 4
2460498.22509894576624.7598011932460856.00885736576372.684880489
2461341.18531764576242.5816956092462569.03412494575564.960941028
#Sta/Elev= 30
       0 1741.03    15.3 1738.78   29.541731.089    54.5 1718.34     1401714.145
  468.131709.875   490.2 1709.04   519.2 1699.56   556.5 1695.59  667.791701.699
   672.4 1698.77   680.7 1693.53   705.9 1692.91   738.5 1693.21  753.311697.541
  767.621710.564   775.9 1714.34  867.451718.253  1074.31720.525 1179.781721.761
  1334.7 1731.65    14601731.606  1709.3 1736.66  1756.4 1747.24 1812.661748.582
 2023.621767.783  2111.4 1780.29  2168.5 1781.94 2234.58 1823.12  2342.4 1877.16
#Mann= 15 ,-1 , 0
       0      .1       0   29.54     .06       0     140     .05       0
  468.13     .06       0  667.79      .1       0   672.4    .045       0
  753.31      .1       0  767.62    .055       0  867.45     .02       0
  1074.3    .035       0 1179.78    .055       0    1460    .035       0
 1812.66    .055       0 2023.62     .06       0 2234.58      .1       0
Bank Sta=672.4,753.31
XS Rating Curve= 0 ,0
Exp/Cntr(USF)=0,0
Exp/Cntr=0.3,0.1

Type RM Length L Ch R = 1 ,130983  ,378.6,375.2,372
XS GIS Cut Line= 4
2460522.61944611576920.2024501912460991.53300828576746.731537018
2461465.86753648576605.7864200652462975.60657769575971.533393777
#Sta/Elev= 30
       0 1759.04   50.711744.455     111 1715.55  151.921702.783   230.4 1698.07
  556.151700.614  635.731695.581   677.1 1691.67   732.8 1691.95  744.49 1695.58
   956.71710.876  1058.11713.362 1262.44 1716.76 1466.791718.003  1773.31726.816
  1953.9 1736.22  2024.2 1735.07  2054.4 1740.58  2118.9 1743.36  2198.4 1742.03
  2220.9 1748.03 2284.171751.834 2386.341756.117  2424.4 1768.26  2449.2 1781.27
 2488.511784.536    2510 1785.23  2531.6  1808.9 2590.68 1834.46  2632.4 1847.89
#Mann= 15 ,-1 , 0
       0     .06       0   50.71      .1       0  151.92     .05       0
  556.15     .06       0  635.73    .045       0  744.49      .1       0
   956.7    .055       0  1058.1    .035       0 1262.44    .055       0
 1466.79     .05       0  1773.3    .055       0 2284.17     .06       0
 2386.34      .1       0 2488.51     .06       0 2590.68      .1       0
Bank Sta=635.73,744.49
XS Rating Curve= 0 ,0
Exp/Cntr(USF)=0,0
Exp/Cntr=0.3,0.1

Type RM Length L Ch R = 1 ,130608  ,464.9,457.3,445.8
XS GIS Cut Line= 4
2460636.45973288577283.4071746462461056.58460072 577131.62012562
2461579.70782325576941.886314337 2463065.0525173576242.581695609
#Sta/Elev= 30
       0 1761.14   142.8 1708.03  197.571696.958  399.691696.507   470.3 1696.07
  500.761702.021  601.84 1697.39  620.131694.094   674.5 1689.63   725.6 1693.58
   806.4 1698.42   891.5 1691.55   921.3 1694.86   946.8 1709.44 1103.431709.037
 1109.561708.993 1212.881709.085 1626.161715.086 1729.481719.641 1794.971722.191
  1832.81723.483 1936.121727.815 2142.761735.792 2246.081739.949  2349.41740.876
 2452.721761.449 2486.511766.385  2571.6 1779.52  2600.9 1792.75  2644.9 1795.49
#Mann= 20 ,-1 , 0
       0      .1       0  197.57     .05       0  399.69      .1       0
  500.76     .06       0  601.84      .1       0  620.13    .045       0
   725.6      .1       0 1103.43    .055       0 1109.56    .035       0
 1212.88    .055       0 1626.16    .035       0 1729.48    .055       0
 1794.97     .05       0  1832.8    .035       0 1936.12    .055       0
 2142.76     .06       0 2246.08    .055       0  2349.4    .035       0
 2452.72    .055       0 2486.51     .06       0
Bank Sta=620.13,725.6
XS Rating Curve= 0 ,0
Exp/Cntr(USF)=0,0
Exp/Cntr=0.3,0.1

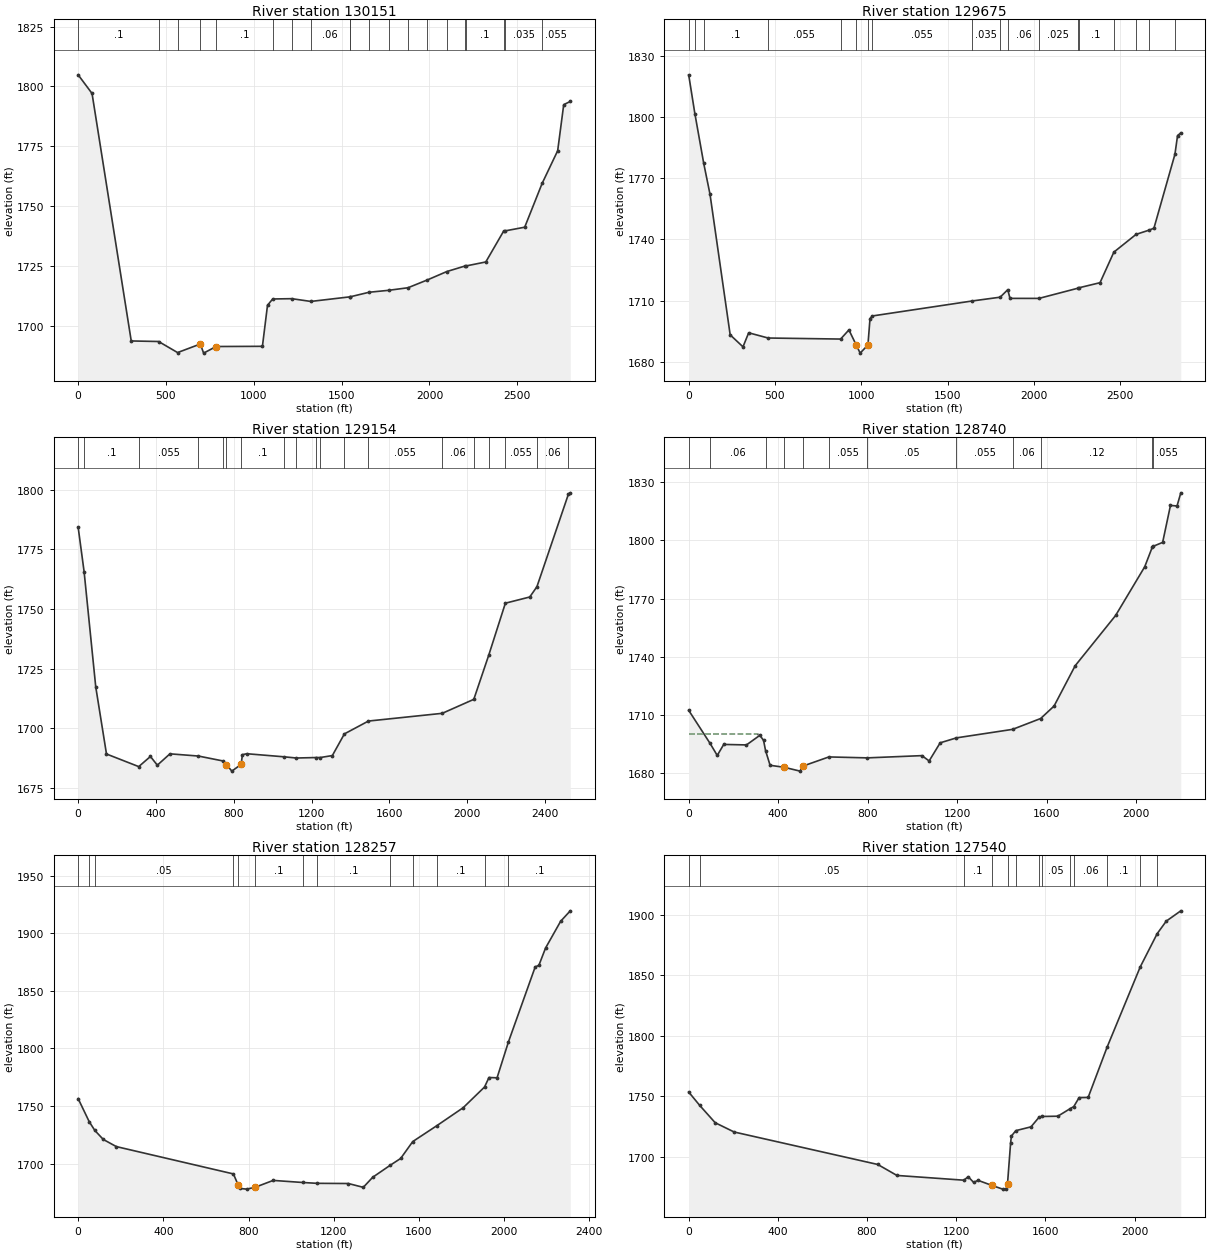
Type RM Length L Ch R = 1 ,130151  ,499.1,475.7,454.3
XS GIS Cut Line= 4
2460790.95726492577849.8981254772461080.97894788 577698.11107645
 2461896.8343364577174.987853913 2463124.6831437576304.922805031
#Sta/Elev= 30
       0 1804.84    79.1 1797.06   302.2 1693.78  457.821693.552  566.091688.932
   695.3  1692.5   714.3  1688.7   785.4 1691.46    1049 1691.54  1077.9 1708.67
 1107.411711.297 1215.671711.426 1324.531710.272 1545.741712.175 1548.081712.193
 1656.351714.105  1766.71714.906 1877.561715.984 1988.171719.252 2098.771722.749
 2203.951725.095 2209.381725.098  2320.6 1726.75 2422.571739.671 2430.591739.714
    2542 1741.25  2641.2 1759.53  2729.7 1773.16  2764.1 1792.39  2801.4 1793.73
#Mann= 20 ,-1 , 0
       0      .1       0  457.82     .06       0  566.09      .1       0
   695.3    .045       0   785.4      .1       0 1107.41     .06       0
 1215.67     .05       0 1324.53     .06       0 1545.74    .055       0
 1548.08    .035       0 1656.35    .055       0  1766.7    .035       0
 1877.56    .055       0 1988.17     .06       0 2098.77      .1       0
 2203.95    .035       0 2209.38      .1       0 2422.57    .055       0
 2430.59    .035       0  2641.2    .055       0
Bank Sta=695.3,785.4
XS Rating Curve= 0 ,0
Exp/Cntr(USF)=0,0
Exp/Cntr=0.3,0.1

Type RM Length L Ch R = 1 ,129675  ,515.2,521.4,530
XS GIS Cut Line= 4
2461262.58131011578467.8882536552461772.15211756577806.530397183
2462024.22703826577397.2474614162463246.65487953 576467.55178613
#Sta/Elev= 30
       0 1820.62    35.71801.666   87.271777.191   123.5 1762.13   240.4 1693.25
   314.6 1687.38   347.6 1694.26   460.31691.702  880.181691.191   928.4 1695.67
   970.7 1688.28   993.5  1684.3 1038.561688.304  1050.6 1701.24 1064.281702.505
 1644.011709.863 1804.561711.698 1848.891715.377  1861.5 1711.12 2029.621711.108
 2254.681716.089 2258.651716.253  2383.3  1718.8 2463.531733.776 2592.261742.471
 2668.411744.565  2695.7  1745.5 2817.321781.687  2832.6 1790.88  2851.4 1792.17
#Mann= 18 ,-1 , 0
       0     .05       0    35.7      .1       0   87.27      .1       0
   460.3    .055       0  880.18     .06       0   970.7    .045       0
 1038.56      .1       0 1064.28    .055       0 1644.01    .035       0
 1804.56    .055       0 1848.89     .06       0 2029.62    .025       0
 2254.68    .055       0 2258.65      .1       0 2463.53    .055       0
 2592.26    .035       0 2668.41    .055       0 2817.32     .06       0
Bank Sta=970.7,1038.56
XS Rating Curve= 0 ,0
Exp/Cntr(USF)=0,0
Exp/Cntr=0.3,0.1

Type RM Length L Ch R = 1 ,129154  ,408.8,413.5,416
XS GIS Cut Line= 4
2461796.54646472578579.0180574062462162.46167219578096.552080144
2462406.40514384 577828.214261332463496.01931721576708.784774761
#Sta/Elev= 30
       0 1784.34   30.671765.683    90.5 1717.39   145.7 1689.28  311.491683.995
   371.7 1688.24   407.1 1684.59   472.1 1689.35  618.031688.424  746.231686.336
   762.6 1684.84   790.3  1682.1   837.9 1684.92   844.8 1689.01   867.6 1689.39
 1060.821688.086 1121.691687.595 1223.081687.794 1245.341687.807    1307 1688.62
 1368.991697.704 1492.641703.088 1872.131706.324 2034.391712.186 2110.891730.622
 2196.661752.484  2322.1 1755.08 2358.921759.385 2521.18 1798.25  2530.4 1798.74
#Mann= 19 ,-1 , 0
       0      .1       0   30.67      .1       0  311.49    .055       0
  618.03     .06       0  746.23      .1       0   762.6    .045       0
   837.9      .1       0 1060.82     .06       0 1121.69    .055       0
 1223.08     .06       0 1245.34     .05       0 1368.99     .06       0
 1492.64    .055       0 1872.13     .06       0 2034.39      .1       0
 2110.89     .06       0 2196.66    .055       0 2358.92     .06       0
 2521.18    .055       0
Bank Sta=762.6,837.9
XS Rating Curve= 0 ,0
Exp/Cntr(USF)=0,0
Exp/Cntr=0.3,0.1

Type RM Length L Ch R = 1 ,128740  ,516.7,482.8,450.3
XS GIS Cut Line= 4
2462270.88099293578560.044676278 2462474.1672193 578345.91651783
2462899.71305318577944.7650311182463802.30389828576982.543559612
#Sta/Elev= 30
       0 1712.22   95.841695.081   127.6 1688.91   156.7  1694.6   258.2 1694.34
     318  1699.3   334.6  1696.7  343.511691.435   363.8 1683.82     428 1682.75
   497.9  1680.8   510.4  1683.4  626.511688.133  798.77 1687.65  1042.4 1688.81
  1074.6 1686.06    1124 1695.43 1196.851697.991 1447.631702.385 1573.021707.989
  1632.9 1714.42  1727.2 1735.25    1908 1761.23  2038.1 1786.39 2072.511796.715
 2074.581796.901  2118.2    1799  2153.2 1818.11  2182.5 1817.81  2199.4 1824.61
#Mann= 12 ,-1 , 0
       0      .1       0   95.84     .06       0  343.51      .1       0
     428    .045       0   510.4      .1       0  626.51    .055       0
  798.77     .05       0 1196.85    .055       0 1447.63     .06       0
 1573.02     .12       0 2072.51     .06       0 2074.58    .055       0
#XS Ineff= 2 , 0
          311.64 1699.78
Permanent Ineff=
       F       F
Bank Sta=428,510.4
XS Rating Curve= 0 ,0
Exp/Cntr(USF)=0,0
Exp/Cntr=0.3,0.1

Type RM Length L Ch R = 1 ,128257  ,683.4,717.4,739.6
XS GIS Cut Line= 4
2462558.19219287 578879.881672442463056.92106824 578394.70521216
2463070.47348333578088.4206310892464114.00944539577299.670072756
#Sta/Elev= 30
       0 1756.45   51.86 1736.49   78.351728.841     118 1721.04   179.3 1714.84
  729.031691.125   750.61681.777   759.7 1678.52   791.7 1677.94   831.7  1679.6
   915.7  1685.5 1054.34  1683.7 1121.541682.972  1268.5 1682.81  1338.7  1679.5
    1383 1688.24 1466.371698.796  1514.2 1704.56 1570.941719.202 1683.291732.892
  1807.6 1748.56    1908 1766.53  1928.9 1774.78  1966.8 1774.52 2020.351805.746
  2145.9 1870.75  2163.1 1872.06  2194.5 1887.11  2265.3 1910.31  2310.5 1919.38
#Mann= 13 ,-1 , 0
       0    .055       0   51.86      .1       0   78.35     .05       0
  729.03      .1       0   750.6    .045       0   831.7      .1       0
 1054.34     .05       0 1121.54      .1       0 1466.37      .1       0
 1570.94     .12       0 1683.29      .1       0    1908     .06       0
 2020.35      .1       0
Bank Sta=750.6,831.7
XS Rating Curve= 0 ,0
Exp/Cntr(USF)=0,0
Exp/Cntr=0.3,0.1

Type RM Length L Ch R = 1 ,127540  ,293.8,296.7,299.1
XS GIS Cut Line= 4
 2462709.9792419579186.1662535112463314.41695498578619.675302681
2463902.59176996578115.5254612722464227.84973216577605.954653827
#Sta/Elev= 30
       0  1753.7    49.41742.645   118.9 1728.33   203.9 1720.68   848.1 1693.87
   934.1 1684.81 1234.721680.891  1253.7 1683.79  1278.3 1679.05  1297.7 1680.79
  1360.9 1676.53  1408.4 1673.51  1424.2 1673.62 1430.191677.926  1444.2 1711.85
  1447.6  1717.3 1467.411721.796  1535.6 1724.94 1572.741733.098 1583.751733.483
    1656 1733.74 1711.771740.008 1727.431741.667  1751.4 1749.07  1791.9  1749.2
 1876.551790.545 2025.671857.024 2101.691884.467  2142.4  1894.8  2207.6  1903.3
#Mann= 13 ,-1 , 0
       0      .1       0    49.4     .05       0 1234.72      .1       0
  1360.9    .045       0 1430.19      .1       0 1467.41      .1       0
 1572.74      .1       0 1583.75     .05       0 1711.77     .12       0
 1727.43     .06       0 1876.55      .1       0 2025.67     .12       0
 2101.69      .1       0
Bank Sta=1360.9,1430.19
XS Rating Curve= 0 ,0
Exp/Cntr(USF)=0,0
Exp/Cntr=0.3,0.1