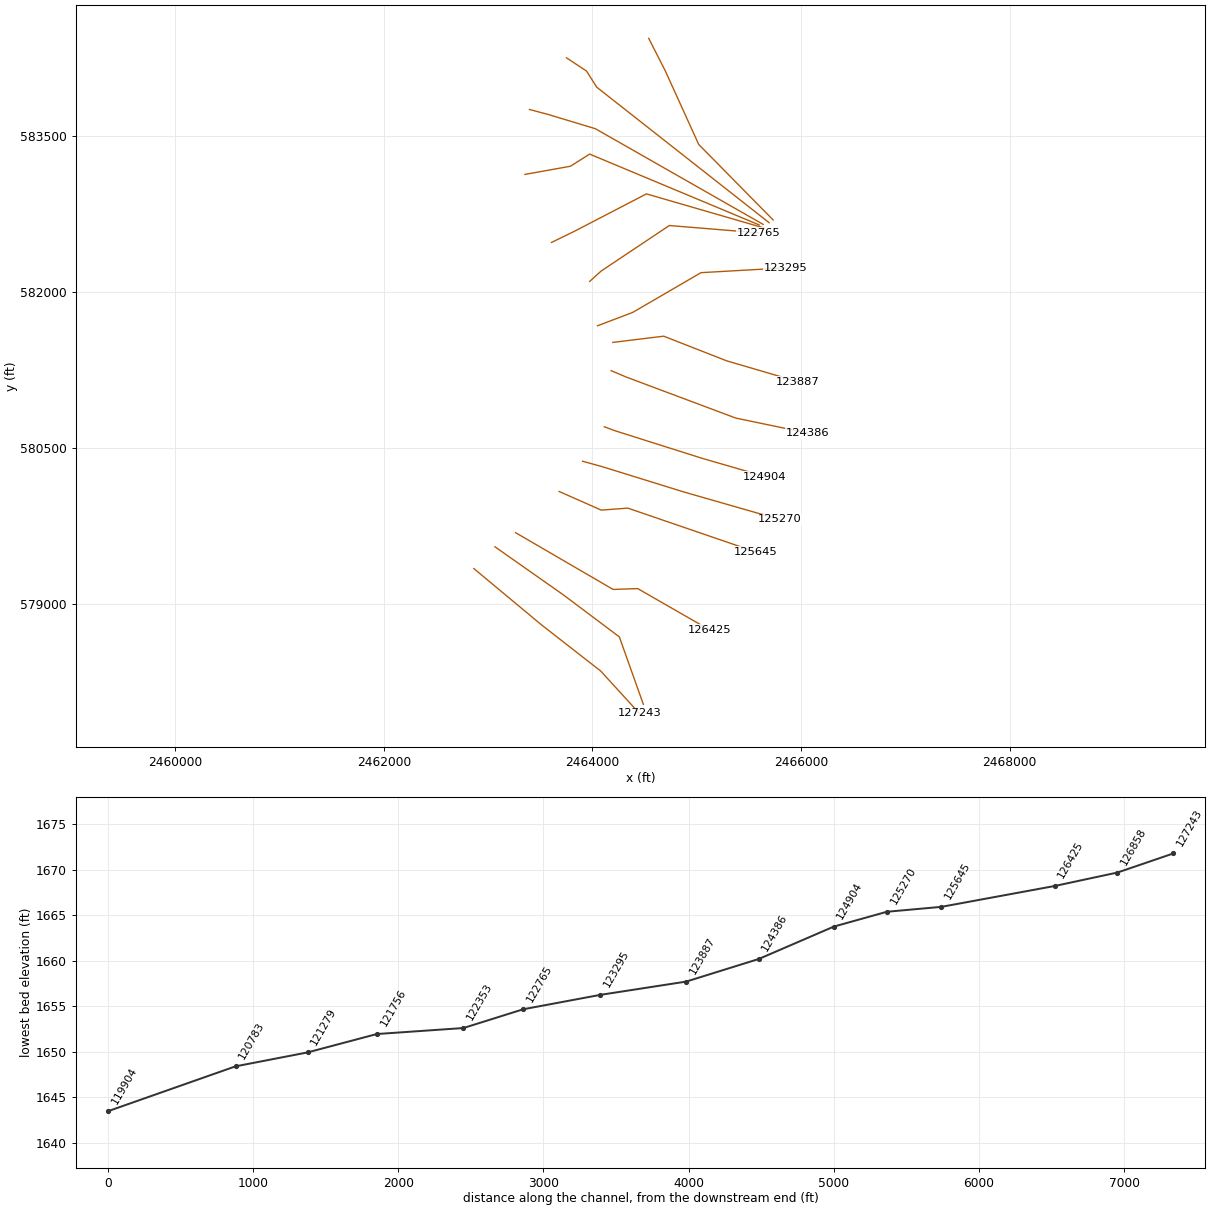
HEC-RAS study SFSBPOTOMC.prj: SFSBPOTOMC

--- SFSBPOTOMC.g01 (geometry) --- (continued)

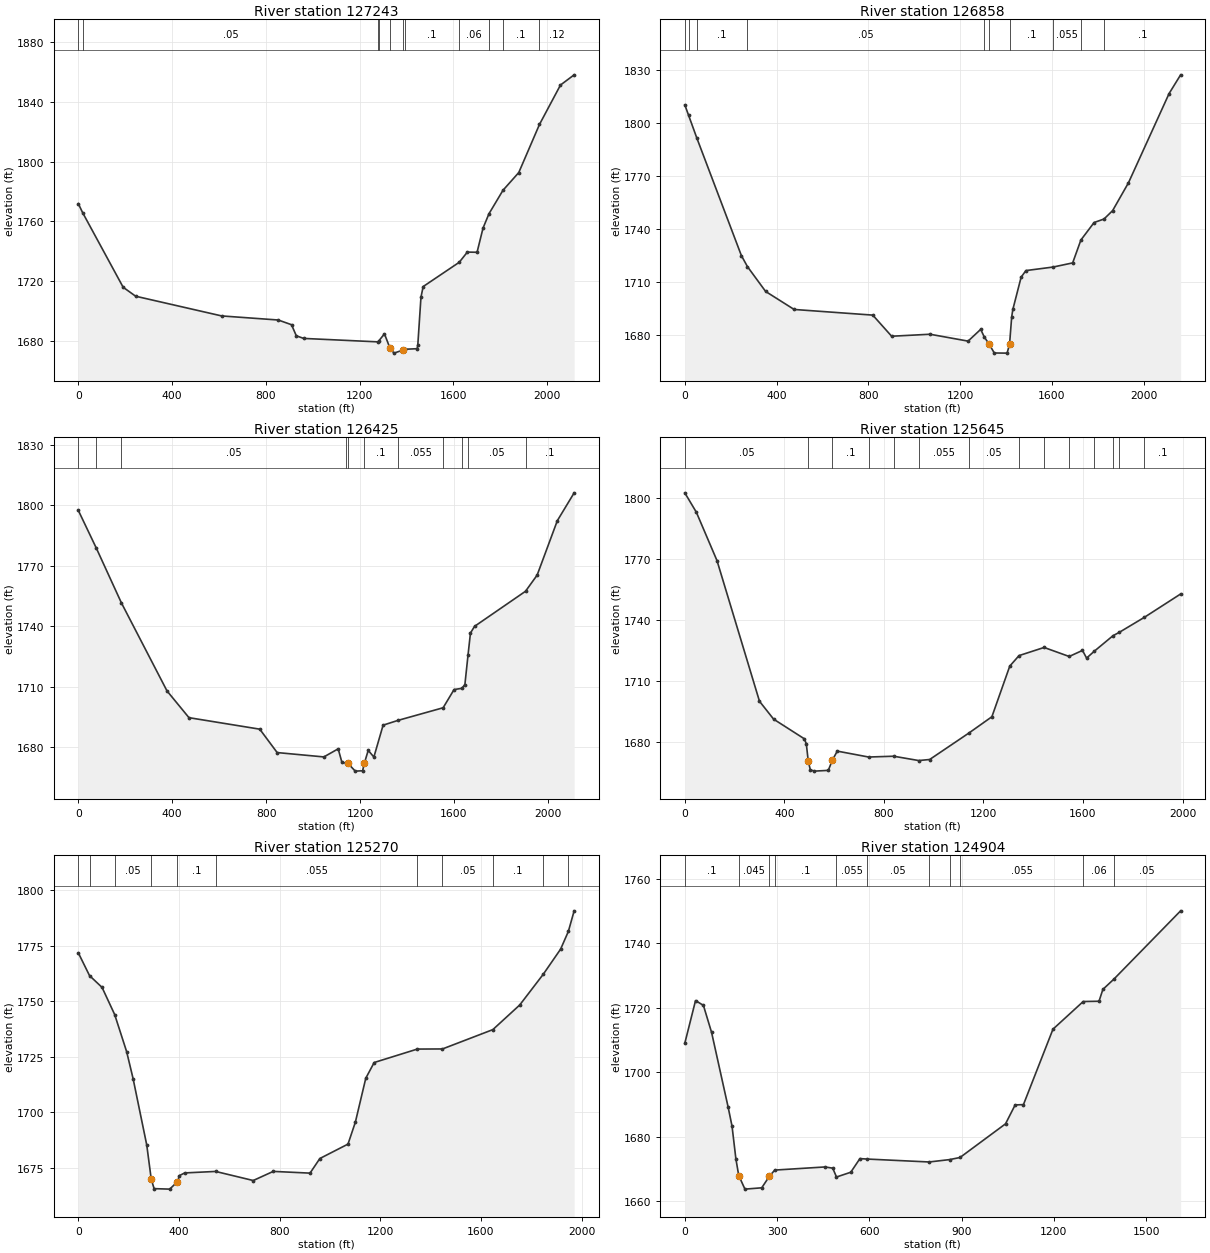
Type RM Length L Ch R = 1 ,127243  ,378.6,385.4,386.9
XS GIS Cut Line= 4
2462861.76629092579343.374268574 2463509.5717323578803.988147927
2464078.77316615578359.4689329222464450.10933966577952.896480173
#Sta/Elev= 30
       0 1771.87   18.161765.932   191.3 1715.91   244.6 1709.91   611.7 1696.71
   853.1 1693.98   909.7 1690.83   930.1 1683.43   961.4 1681.65 1279.171679.338
 1281.961679.957  1306.3 1684.71    1330 1675.09  1346.9  1671.8  1384.1 1673.77
 1392.481674.377  1445.9 1674.77  1448.7 1677.48  1462.1 1709.25  1471.5 1716.38
 1625.481732.647    1660 1739.46  1701.5 1739.35  1726.9 1755.51 1752.181765.116
 1812.061780.859  1879.5 1792.74 1967.831824.966  2057.4 1851.34  2115.8 1858.18
#Mann= 11 ,-1 , 0
       0      .1       0   18.16     .05       0 1279.17      .1       0
 1281.96      .1       0    1330    .045       0  1384.1      .1       0
 1392.48      .1       0 1625.48     .06       0 1752.18      .1       0
 1812.06      .1       0 1967.83     .12       0
Bank Sta=1330,1384.1
XS Rating Curve= 0 ,0
Exp/Cntr(USF)=0,0
Exp/Cntr=0.3,0.1

Type RM Length L Ch R = 1 ,126858  ,398.4,433.1,456.5
XS GIS Cut Line= 4
 2463065.0525173579552.0814609852463723.69989075579088.588864851
2464257.66504536578687.4373781392464488.05610192578039.631936759
#Sta/Elev= 30
       0 1810.37   16.15 1804.59   52.271791.623   246.6 1724.97  273.121718.691
   352.3 1704.64   476.5 1694.44   819.2 1691.24   901.4 1679.27  1068.7  1680.4
  1234.6  1676.5  1289.5 1683.17 1305.361678.781 1326.241674.829  1348.7 1669.78
  1404.6  1669.7 1415.381674.827  1424.6 1690.26  1429.6 1694.44  1465.8 1712.76
  1486.6 1716.47 1605.141718.475  1690.3 1720.82  1726.21733.792  1783.7  1743.7
  1826.91745.686  1864.4 1750.44  1933.6 1766.23  2110.6 1816.79  2160.8 1827.38
#Mann= 10 ,-1 , 0
       0      .1       0   16.15     .05       0   52.27      .1       0
  273.12     .05       0 1305.36      .1       0 1326.24    .045       0
 1415.38      .1       0 1605.14    .055       0  1726.2      .1       0
  1826.9      .1       0
Bank Sta=1326.24,1415.38
XS Rating Curve= 0 ,0
Exp/Cntr(USF)=0,0
Exp/Cntr=0.3,0.1

Type RM Length L Ch R = 1 ,126425  ,777.7,780.1,777.7
XS GIS Cut Line= 4
2463262.91777764579687.6056119012464198.03441896579142.798525218
2464433.84644155579150.9299742732465122.30912821578755.199453597
#Sta/Elev= 30
       0 1797.45   77.151778.633  183.541751.615   377.7 1707.99   471.3 1694.72
   772.9 1689.02     847 1677.42    1046 1675.26    1107 1679.27    1123 1672.53
 1138.241672.306  1148.8 1672.06  1179.7 1668.22    1211  1668.4  1218.4  1672.1
    1235 1678.51  1259.1  1675.2  1298.4 1691.01 1362.371693.391 1554.121699.634
  1600.7 1708.66 1633.74 1709.26  1646.8 1711.13 1660.281725.895  1670.5 1736.67
    1688 1739.99 1905.111757.379  1954.6 1765.39  2040.7 1792.39  2112.3 1806.18
#Mann= 11 ,-1 , 0
       0     .05       0   77.15      .1       0  183.54     .05       0
 1138.24      .1       0  1148.8    .045       0  1218.4      .1       0
 1362.37    .055       0 1554.12     .06       0 1633.74    .055       0
 1660.28     .05       0 1905.11      .1       0
Bank Sta=1148.8,1218.4
XS Rating Curve= 0 ,0
Exp/Cntr(USF)=0,0
Exp/Cntr=0.3,0.1

Type RM Length L Ch R = 1 ,125645  ,389.9,375.2,350.1
XS GIS Cut Line= 4
2463680.33216246580083.3361325772464084.19413219579904.444253367
2464338.97953591579923.4176344962465564.11786019579503.292766655
#Sta/Elev= 30
       0 1802.37    46.4 1792.86   129.5  1769.1   300.1 1700.18   356.9 1691.41
   480.4 1681.77   488.4 1679.25  495.991670.886   504.4 1666.57   520.5 1665.93
   576.6  1666.3   593.5 1671.44   612.7 1675.74  738.531672.844  839.291673.238
  940.061671.114     984 1671.63 1141.581684.604    1234 1692.59  1305.9 1717.43
 1343.111722.571 1443.871726.559 1544.631722.133    1598 1725.11  1614.6 1721.35
 1645.391724.709 1720.611732.319 1746.16 1733.99 1846.921741.346  1992.4 1752.78
#Mann= 14 ,-1 , 0
       0     .05       0  495.99    .045       0   593.5      .1       0
  738.53    .055       0  839.29      .1       0  940.06    .055       0
 1141.58     .05       0 1343.11      .1       0 1443.87     .05       0
 1544.63    .055       0 1645.39     .05       0 1720.61      .1       0
 1746.16     .05       0 1846.92      .1       0
Bank Sta=495.99,593.5
XS Rating Curve= 0 ,0
Exp/Cntr(USF)=0,0
Exp/Cntr=0.3,0.1

Type RM Length L Ch R = 1 ,125270  ,365.7,365.7,365.2
XS GIS Cut Line= 4
2463905.30225298580373.3578155382464092.32558124 580321.85863819
2464878.36565656 580077.915166542465794.50891675579814.998313763
#Sta/Elev= 30
       0 1771.84   44.511761.593    94.3 1756.28  144.411744.052   191.9 1727.35
   217.5 1715.22   271.9 1685.24   289.81669.755   301.2 1665.61   363.2 1665.39
   393.3  1668.7   401.7 1671.49   422.7 1672.69  545.41 1673.36   694.9 1669.27
   774.5 1673.38   920.6  1672.6   959.7 1679.19  1071.5 1685.68  1100.7 1695.54
  1142.2 1715.38  1175.5 1722.44  1346.91728.497 1446.921728.555 1646.96 1737.26
  1753.8 1748.36    18471762.155  1916.3 1773.53 1947.021781.493  1970.1 1790.79
#Mann= 11 ,-1 , 0
       0      .1       0   44.51      .1       0  144.41     .05       0
   289.8    .045       0   393.3      .1       0  545.41    .055       0
  1346.9     .06       0 1446.92     .05       0 1646.96      .1       0
    1847     .12       0 1947.02      .1       0
Bank Sta=289.8,393.3
XS Rating Curve= 0 ,0
Exp/Cntr(USF)=0,0
Exp/Cntr=0.3,0.1

Type RM Length L Ch R = 1 ,124904  ,518.6,517.4,512.6
XS GIS Cut Line= 4
2464114.00944539580704.0367437742464217.00780009580666.089981517
2465046.41560369580403.173128739 2465653.5637998580226.991732548
#Sta/Elev= 30
       0 1709.03    34.9 1722.27    60.5 1720.79    87.1 1712.39     141 1689.17
   153.6 1683.28   166.1 1673.15  175.361667.983   195.5 1663.76   250.1 1664.17
   275.2 1667.77   292.41669.671   455.7 1670.64   480.9 1670.27  493.181667.522
   539.6    1669   569.3 1673.23  593.571673.092  794.341672.187  860.881672.923
  894.731673.576  1042.7 1684.02    1074 1689.89    1101 1689.99    1197  1713.4
 1295.24 1721.98  1346.7 1722.07  1359.2 1725.74  1395.31728.958    1612 1750.13
#Mann= 11 ,-1 , 0
       0      .1       0  175.36    .045       0   275.2      .1       0
   292.4      .1       0  493.18    .055       0  593.57     .05       0
  794.34    .055       0  860.88     .05       0  894.73    .055       0
 1295.24     .06       0  1395.3     .05       0
Bank Sta=175.36,275.2
XS Rating Curve= 0 ,0
Exp/Cntr(USF)=0,0
Exp/Cntr=0.3,0.1

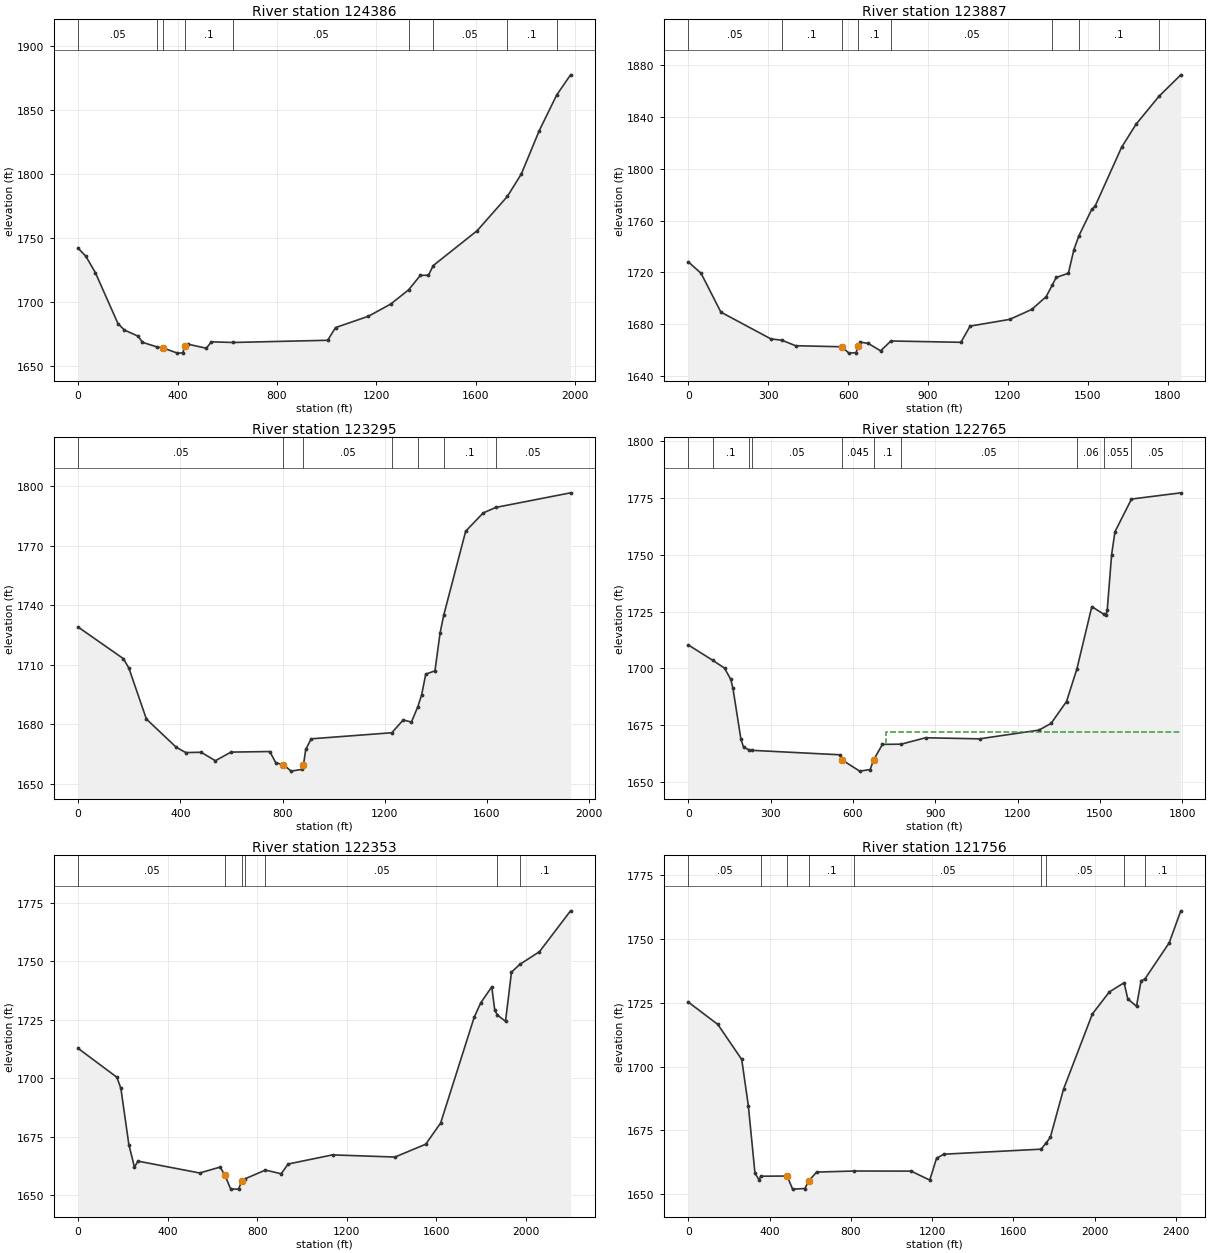
Type RM Length L Ch R = 1 ,124386  ,503,499.5,496.9
XS GIS Cut Line= 4
2464179.06103783581243.4228644212464325.42712082581181.081754999
2465374.38404891580788.0617173422466062.84673557 580644.40611737
#Sta/Elev= 30
       0 1741.94    30.7  1735.8    69.2 1722.97   160.5 1683.15   186.1 1678.23
   241.7 1673.37   258.7 1668.66  318.281664.978   339.9 1664.37   399.7  1660.2
   421.1 1660.43   429.6 1665.48   442.4 1667.18     516 1663.99   536.4 1669.03
  622.15  1668.5  1004.6 1670.22  1036.2 1680.12  1168.6 1688.94  1258.7 1698.49
 1330.221709.497  1377.7  1720.8  1410.4 1720.94 1429.641728.462  1606.5 1755.65
 1727.891782.308  1784.3 1799.84  1856.5 1833.65 1926.731861.422  1982.5 1877.15
#Mann= 9 ,-1 , 0
       0     .05       0  318.28      .1       0   339.9    .045       0
   429.6      .1       0  622.15     .05       0 1330.22     .06       0
 1429.64     .05       0 1727.89      .1       0 1926.73      .1       0
Bank Sta=339.9,429.6
XS Rating Curve= 0 ,0
Exp/Cntr(USF)=0,0
Exp/Cntr=0.3,0.1

Type RM Length L Ch R = 1 ,123887  ,549.1,592.2,620.6
XS GIS Cut Line= 4
2464195.32393594581514.4711662532464683.21087924581574.101792656
2465284.93810931581338.2897700622465967.97982992581137.714026706
#Sta/Elev= 30
       0 1728.07    47.8 1719.22   121.9 1689.36   309.7 1668.71  351.811667.644
   402.4 1663.44     577 1662.62   602.7 1657.72   629.4 1658.07   638.7 1662.95
   645.7  1666.2   675.8 1665.19     722 1659.48  760.681667.096  1023.7 1666.07
  1058.1 1678.56  1206.7 1683.73  1289.8 1691.41    1344 1701.32 1366.871710.225
  1381.5  1716.1  1427.3 1719.29  1448.1 1737.46 1466.961748.269  1514.9 1768.49
  1527.4 1770.89  1627.4 1816.51  1681.6 1834.25 1767.251855.661  1849.7 1872.34
#Mann= 8 ,-1 , 0
       0     .05       0  351.81      .1       0     577    .045       0
   638.7      .1       0  760.68     .05       0 1366.87     .06       0
 1466.96      .1       0 1767.25      .1       0
Bank Sta=577,638.7
XS Rating Curve= 0 ,0
Exp/Cntr(USF)=0,0
Exp/Cntr=0.3,0.1

Type RM Length L Ch R = 1 ,123295  ,529.1,530.1,531.7
XS GIS Cut Line= 4
2464048.95785295581674.3896643342464385.05774722581801.782366196
2465040.99463766 582183.960471782465848.71857712582230.038683091
#Sta/Elev= 30
       0 1728.94   177.3 1712.98   198.7 1708.16   267.1 1682.54   384.5 1668.24
   421.6 1665.61   481.4 1665.78     537 1661.51   598.4 1665.86   750.3 1666.15
   773.9 1660.41   803.2 1659.57   833.6 1656.26   878.1 1657.19   882.1 1659.51
   890.9 1667.18   912.3 1672.56 1228.011675.629  1272.6 1682.08  1304.6 1681.02
 1329.731688.751  1344.7 1694.76  1360.7 1705.19  1396.8 1706.86  1416.8 1725.96
 1431.451735.091    1517 1777.29  1585.1 1786.48 1634.891789.307  1927.6 1796.67
#Mann= 7 ,-1 , 0
       0     .05       0   803.2    .045       0   882.1     .05       0
 1228.01    .055       0 1329.73    .055       0 1431.45      .1       0
 1634.89     .05       0
Bank Sta=803.2,882.1
XS Rating Curve= 0 ,0
Exp/Cntr(USF)=0,0
Exp/Cntr=0.3,0.1

Type RM Length L Ch R = 1 ,122765  ,416.7,412,410.4
XS GIS Cut Line= 4
2463973.06432844582099.9354982122464084.19413219 582200.22336989
2464737.42053961 582636.61113584 2465593.9331734582566.138577364
#Sta/Elev= 30
       0 1710.27   88.041703.567   131.6 1700.09   154.5 1695.09   162.4 1691.12
   191.2 1668.89   200.9 1665.25  220.671664.083  232.691663.841   551.4 1661.89
  560.961659.559   624.2 1654.68   662.7 1655.38  674.651659.558   707.2 1666.47
  775.481666.566   864.7 1669.39    1061 1668.91  1277.8 1672.76  1321.9 1675.72
  1378.1 1685.36 1415.711699.592  1470.4 1727.18 1515.331723.724  1522.6 1723.36
  1526.6 1725.78  1542.6 1750.13  1554.7 1760.18 1614.961774.596  1794.7 1777.34
#Mann= 10 ,-1 , 0
       0     .05       0   88.04      .1       0  220.67      .1       0
  232.69     .05       0  560.96    .045       0  674.65      .1       0
  775.48     .05       0 1415.71     .06       0 1515.33    .055       0
 1614.96     .05       0
#XS Ineff= 2 , 0
                           721.6            1672
Permanent Ineff=
       F       F
Bank Sta=560.96,674.65
XS Rating Curve= 0 ,0
Exp/Cntr(USF)=0,0
Exp/Cntr=0.3,0.1

Type RM Length L Ch R = 1 ,122353  ,592.3,596.3,596.2
XS GIS Cut Line= 4
2463607.14912096582473.9821547412463818.56679639582576.980509437
2464517.87141512582940.1852338932465648.14283376582612.216788675
#Sta/Elev= 30
       0 1712.79   173.1 1700.45   190.9 1695.68   226.5 1671.69   251.6 1661.97
   266.9  1664.6   543.1 1659.52   634.2 1662.04  656.281658.493   681.6 1652.62
   716.6 1652.63   731.2 1656.02  745.04 1657.01   836.71660.769     907 1659.19
   938.5 1663.36  1136.5 1667.26  1415.6 1666.34    1553 1671.83  1619.7  1680.9
  1769.6 1726.12  1798.8 1732.27  1848.1 1739.12  1861.6 1729.07 1873.031727.089
  1909.5 1724.38  1936.2 1745.39 1973.081748.692  2061.2 1754.14  2200.1 1771.61
#Mann= 7 ,-1 , 0
       0     .05       0  656.28    .045       0   731.2     .05       0
  745.04      .1       0   836.7     .05       0 1873.03     .06       0
 1973.08      .1       0
Bank Sta=656.28,731.2
XS Rating Curve= 0 ,0
Exp/Cntr(USF)=0,0
Exp/Cntr=0.3,0.1

Type RM Length L Ch R = 1 ,121756  ,512.7,477.4,435.1
XS GIS Cut Line= 4
2463352.36371724583127.2085621572463788.75148319583205.812569689
2463973.06432844583322.3633394772465599.35413943582642.032101877
#Sta/Elev= 30
       0 1725.29   144.7 1716.58   262.5 1702.83   295.1 1684.64   327.6 1658.31
   347.9 1655.55  355.86 1657.03   486.2  1657.1   512.8 1651.96   573.2 1652.19
   593.5 1655.27   631.2 1658.65  817.191659.065  1096.5 1659.03  1188.2  1655.5
  1221.8 1664.06  1257.3 1665.66 1736.411667.634 1760.561670.004    1782 1672.29
    1847 1691.19  1989.1 1720.71  2072.5 1729.32 2144.951732.914  2163.5 1726.57
  2206.2 1723.69  2228.6 1733.67 2247.081734.337  2367.3  1748.6  2424.3 1761.13
#Mann= 9 ,-1 , 0
       0     .05       0  355.86      .1       0   486.2    .045       0
   593.5      .1       0  817.19     .05       0 1736.41    .055       0
 1760.56     .05       0 2144.95     .06       0 2247.08      .1       0
Bank Sta=486.2,593.5
XS Rating Curve= 0 ,0
Exp/Cntr(USF)=0,0
Exp/Cntr=0.3,0.1

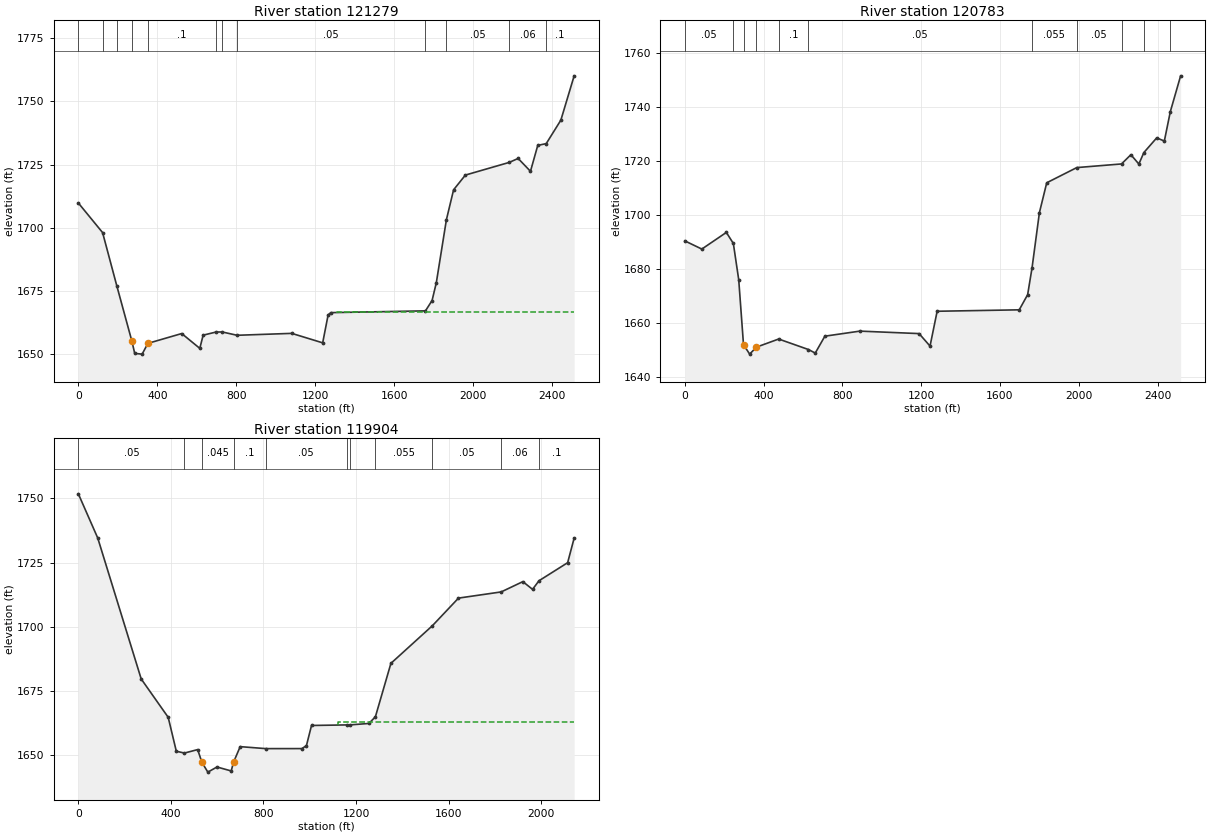
Type RM Length L Ch R = 1 ,121279  ,521.6,496,465.4
XS GIS Cut Line= 4
2463395.73144553583750.6196563722463569.20235871583704.541445061
 2464027.2739888583566.3068111262465637.30090169582647.453067914
#Sta/Elev= 30
       0  1709.8  122.881698.071  194.961676.957  271.621654.977   285.6 1650.23
   323.2 1649.94   352.4  1654.2   523.7 1658.09   615.3 1652.22   632.3 1657.45
  698.13  1658.7  728.831658.716  804.171657.403  1081.1 1658.16  1237.8 1654.41
  1265.3 1665.44  1278.8 1666.37 1758.471667.078  1791.9 1671.16  1813.4 1678.19
 1864.511703.154  1900.9 1715.01  1960.7 1720.85 2182.61 1725.86  2227.9 1727.43
  2290.4 1722.34  2327.3  1732.6 2370.211733.303  2444.3  1742.6  2511.7 1760.15
#Mann= 12 ,-1 , 0
       0      .1       0  122.88     .05       0  194.96      .1       0
  271.62    .045       0   352.4      .1       0  698.13     .05       0
  728.83      .1       0  804.17     .05       0 1758.47    .055       0
 1864.51     .05       0 2182.61     .06       0 2370.21      .1       0
#XS Ineff= 2 , 0
                         1310.96         1666.61
Permanent Ineff=
       F       F
Bank Sta=271.62,352.4
XS Rating Curve= 0 ,0
Exp/Cntr(USF)=0,0
Exp/Cntr=0.3,0.1

Type RM Length L Ch R = 1 ,120783  ,833.4,879.1,870.6
XS GIS Cut Line= 4
2463750.80472093584246.6380487262463943.24901523584119.245346865
2464040.82640389 583964.747814822465694.22104507582663.715966024
#Sta/Elev= 30
       0 1690.44    86.5  1687.4     211 1693.58  246.541689.467   273.8 1676.02
  298.05 1651.94   329.3 1648.41   363.7    1651  476.621654.013  627.69 1650.12
   662.3  1648.8   711.2 1655.07   889.1 1656.95  1189.6 1656.03  1245.1 1651.39
  1281.2 1664.32    1698 1664.85  1740.7 1670.48 1763.111680.458  1800.4 1700.91
  1837.6    1712  1990.21717.637 2217.281718.989  2264.9 1722.42  2305.3 1718.95
 2330.821723.217  2395.9 1728.66  2434.7 1727.49 2465.131738.404  2517.4 1751.69
#Mann= 11 ,-1 , 0
       0     .05       0  246.54    .025       0  298.05    .045       0
   363.7      .1       0  476.62      .1       0  627.69     .05       0
 1763.11    .055       0  1990.2     .05       0 2217.28     .06       0
 2330.82      .1       0 2465.13      .1       0
Bank Sta=298.05,363.7
XS Rating Curve= 0 ,0
Exp/Cntr(USF)=0,0
Exp/Cntr=0.3,0.1

Type RM Length L Ch R = 1 ,119904  ,449.9,426.9,424
XS GIS Cut Line= 4
2464539.55527927 584433.661376992464699.47377735584119.245346865
2465019.31077351  583414.51976212465732.16780733582690.820796207
#Sta/Elev= 30
       0 1751.81    83.9  1734.6   271.7 1679.74   388.3 1664.82   423.4 1651.61
  458.391650.903   515.7 1652.25   533.81647.318   559.6 1643.48   599.1 1645.48
   660.6 1643.94  670.561647.318   699.4  1653.4  809.731652.632   966.2 1652.64
   985.7 1653.81  1007.6 1661.64 1160.441661.859  1172.8 1661.86  1255.3 1662.42
 1283.551665.001  1350.7 1685.82 1529.771700.457  1642.7 1711.22 1827.041713.622
  1920.8 1717.63  1962.7 1714.63  1990.61717.979  2114.3    1725  2142.5 1734.59
#Mann= 11 ,-1 , 0
       0     .05       0  458.39      .1       0   533.8    .045       0
  670.56      .1       0  809.73     .05       0 1160.44    .055       0
  1172.8     .05       0 1283.55    .055       0 1529.77     .05       0
 1827.04     .06       0  1990.6      .1       0
#XS Ineff= 2 , 0
                         1123.29          1662.8
Permanent Ineff=
       F       F
Bank Sta=533.8,670.56
XS Rating Curve= 0 ,0
Exp/Cntr(USF)=0,0
Exp/Cntr=0.3,0.1