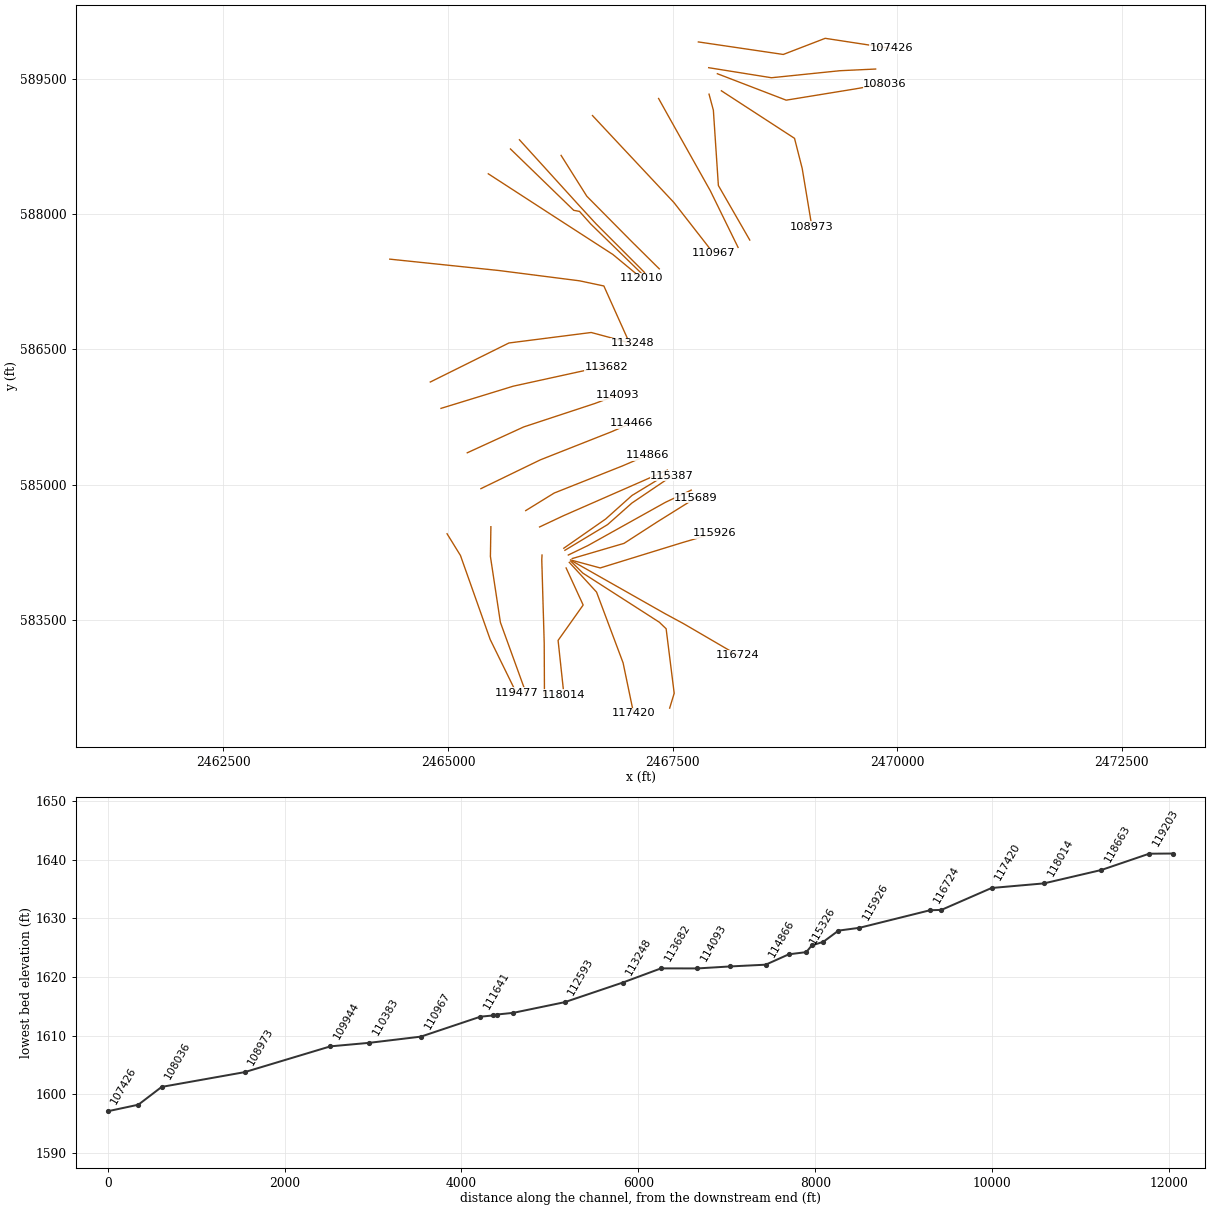
HEC-RAS study SFSBPOTOMC.prj: SFSBPOTOMC

--- SFSBPOTOMC.g01 (geometry) --- (continued)

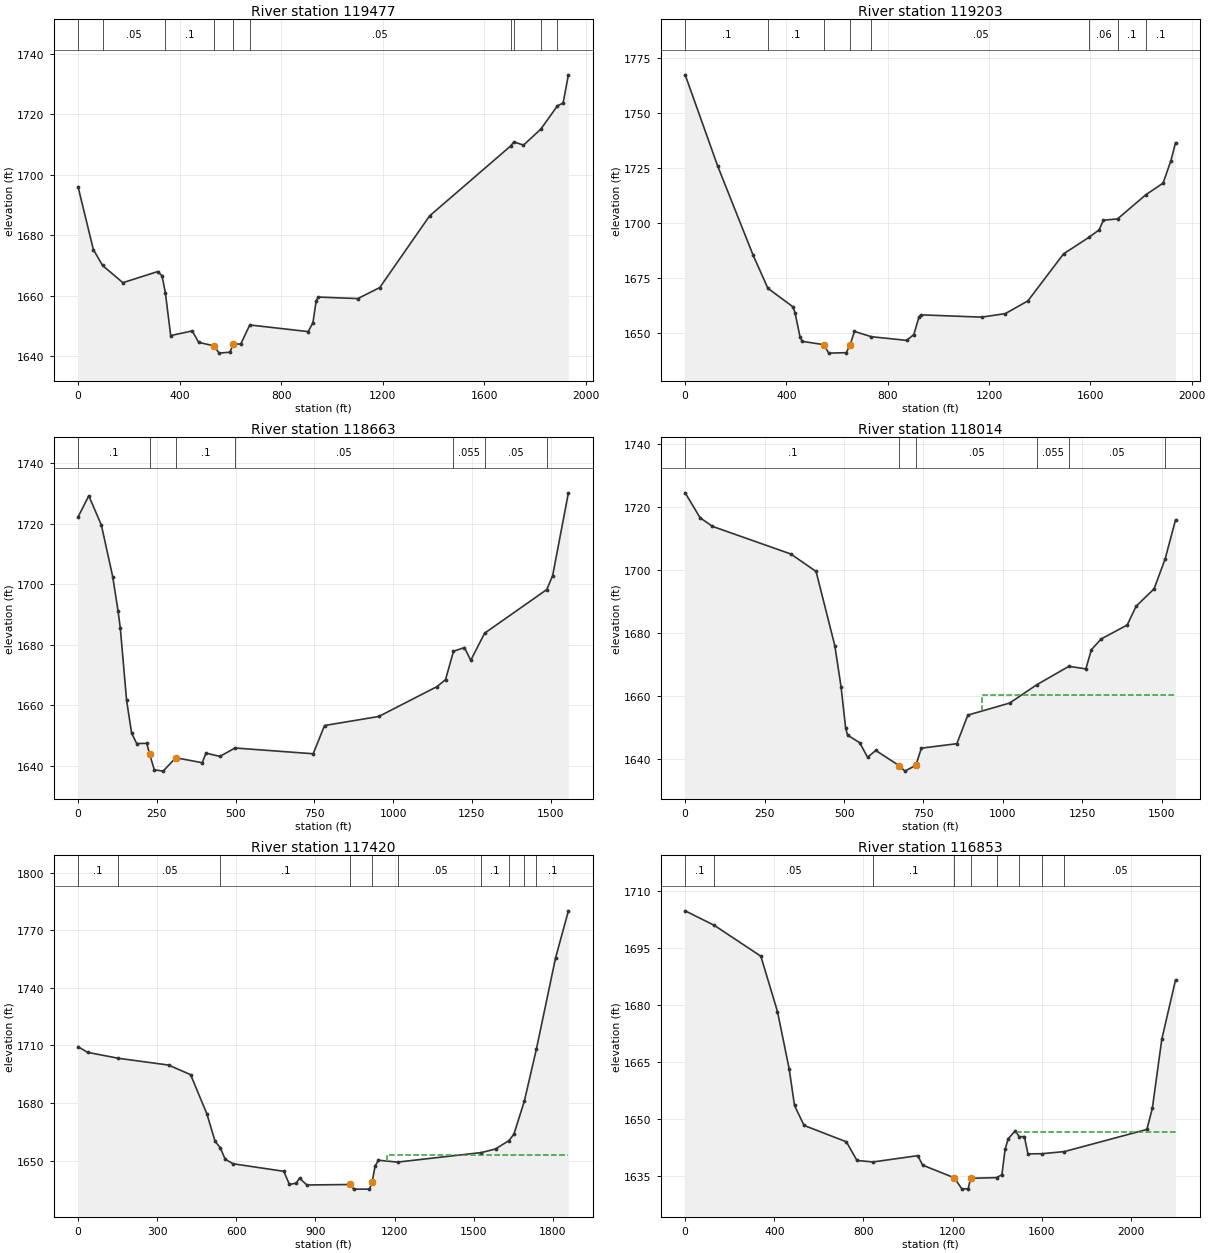
Type RM Length L Ch R = 1 ,119477  ,282.8,274.3,272.2
XS GIS Cut Line= 4
2464989.49546031584452.6347581192465138.57202632584211.401769488
2465469.25095455583278.9956111842465759.27263751582688.110313189
#Sta/Elev= 30
       0 1696.06    60.3  1675.3   96.671670.055   176.5 1664.37   313.8 1668.05
   330.8 1666.64  343.831661.083   364.8  1646.9   449.6 1648.44   475.1 1644.66
   534.5 1643.52   555.7  1641.1   598.2 1641.42   610.9 1644.11   640.6  1644.1
  676.311650.405   906.4 1648.21     925 1651.17   937.7 1658.37   946.2 1659.62
  1101.8 1659.12  1188.1 1662.76  1384.4 1686.43 1703.381709.516 1716.431710.882
  1754.2 1709.82  1822.41715.093 1888.081722.816  1910.2 1723.71  1931.1 1733.04
#Mann= 10 ,-1 , 0
       0      .1       0   96.67     .05       0  343.83      .1       0
   534.5    .045       0   610.9      .1       0  676.31     .05       0
 1703.38     .06       0 1716.43    .055       0  1822.4      .1       0
 1888.08      .1       0
Bank Sta=534.5,610.9
XS Rating Curve= 0 ,0
Exp/Cntr(USF)=0,0
Exp/Cntr=0.3,0.1

Type RM Length L Ch R = 1 ,119203  ,545.8,540,532.6
XS GIS Cut Line= 4
2465477.38240361 584531.238765652465471.96143757584200.559837414
2465583.09124132583468.7294224662465878.53389032582655.584516969
#Sta/Elev= 30
       0 1767.48   128.4 1726.04   268.4 1685.54  326.62 1670.51   425.5 1662.11
   433.6 1659.48   453.4  1648.5   461.9 1646.42   546.8 1644.94   567.1 1641.07
   635.9 1641.28   650.8 1644.66   668.3 1650.94  735.431648.516   874.6 1646.86
   902.9 1649.52   923.1 1657.53   931.8 1658.46  1170.8 1657.41  1264.4 1659.04
  1353.1  1664.8  1494.2 1686.18 1596.06  1693.8    1634 1697.03  1651.7 1701.43
 1707.351702.042 1818.641712.989  1886.9 1718.28  1918.1 1728.55  1936.1 1736.67
#Mann= 8 ,-1 , 0
       0      .1       0  326.62      .1       0   546.8    .045       0
   650.8      .1       0  735.43     .05       0 1596.06     .06       0
 1707.35      .1       0 1818.64      .1       0
Bank Sta=546.8,650.8
XS Rating Curve= 0 ,0
Exp/Cntr(USF)=0,0
Exp/Cntr=0.3,0.1

Type RM Length L Ch R = 1 ,118663  ,678.2,649,604.1
XS GIS Cut Line= 4
2466046.58383746584216.8227355242466043.87335444584162.613075158
2466070.97818462 583235.627882892466073.68866764582661.005483005
#Sta/Elev= 30
       0 1722.28      34 1729.33      74 1719.63     110 1702.57   126.8 1691.35
     134 1685.68     154 1661.74     170 1650.85   186.1 1647.41   218.1 1647.48
  227.361643.826   242.1 1638.72   270.1 1638.29   310.1 1642.72   394.1 1641.07
   406.1 1644.24   450.2 1643.16  498.041645.936   746.3 1644.03   782.3 1653.37
   954.4 1656.35  1139.4 1666.24  1166.4 1668.55 1191.481677.902  1226.4 1679.15
  1246.4 1674.92 1290.261683.883  1487.8 1698.32  1506.4 1702.96  1556.3 1730.29
#Mann= 7 ,-1 , 0
       0      .1       0  227.36    .045       0   310.1      .1       0
  498.04     .05       0 1191.48    .055       0 1290.26     .05       0
  1487.8      .1       0
Bank Sta=227.36,310.1
XS Rating Curve= 0 ,0
Exp/Cntr(USF)=0,0
Exp/Cntr=0.3,0.1

Type RM Length L Ch R = 1 ,118014  ,560.4,593.7,640.1
XS GIS Cut Line= 4
2466314.92165627584073.1671355532466504.65546755583661.173716767
2466225.47571667 583268.153679112466290.52730911582663.715966024
#Sta/Elev= 30
       0 1724.53    46.8 1716.62    85.6 1713.87   332.8 1705.06   412.1 1699.51
   471.1 1675.89   490.7 1662.82   505.2 1649.64   511.1 1647.47   549.6 1645.02
   574.1 1640.41     600 1642.57   674.6 1637.68   691.9    1636   726.2 1637.88
   726.2 1637.91   743.5 1643.31   855.3 1644.73   889.8 1653.82  1021.3 1657.65
 1106.991663.491 1207.951669.345  1261.2 1668.52  1278.9 1674.65  1309.8 1678.07
  1391.5 1682.48  1419.7 1688.48    1476 1693.97 1510.811703.466  1543.6 1715.91
#Mann= 6 ,-1 , 0
       0      .1       0   674.6    .045       0   726.2     .05       0
 1106.99    .055       0 1207.95     .05       0 1510.81      .1       0
#XS Ineff= 2 , 0
                          935.89         1660.07
Permanent Ineff=
       F       F
Bank Sta=674.6,726.2
XS Rating Curve= 0 ,0
Exp/Cntr(USF)=0,0
Exp/Cntr=0.3,0.1

Type RM Length L Ch R = 1 ,117420  ,549.6,566.9,585.1
XS GIS Cut Line= 4
2466350.15793551584135.5082449752466653.73203356583804.829316739
2466949.17468256583018.7892414242467065.72545235582460.429739649
#Sta/Elev= 30
       0 1709.34    36.4  1706.4  152.871703.319   343.4 1699.78   426.7 1694.79
   488.5 1674.33   519.3  1660.2  539.411656.649   557.8 1650.77   587.8 1648.41
     780 1644.49   801.4 1637.63     827 1638.34   839.8 1640.92   867.4 1637.37
  1032.1 1637.62  1044.9 1635.21  1104.8 1635.21 1114.78 1638.79  1126.1 1647.22
    1139 1650.25 1211.271649.276 1529.251654.251  1582.7 1656.11 1633.451660.484
  1652.2 1663.73 1692.051681.076 1737.661708.096  1810.5 1755.67    1859 1780.08
#Mann= 10 ,-1 , 0
       0      .1       0  152.87     .05       0  539.41      .1       0
  1032.1    .045       0 1114.78     .06       0 1211.27     .05       0
 1529.25      .1       0 1633.45     .05       0 1692.05      .1       0
 1737.66      .1       0
#XS Ineff= 2 , 0
                         1169.86         1653.21
Permanent Ineff=
       F       F
Bank Sta=1032.1,1114.78
XS Rating Curve= 0 ,0
Exp/Cntr(USF)=0,0
Exp/Cntr=0.3,0.1

Type RM Length L Ch R = 1 ,116853  ,116.7,128.7,149.9
XS GIS Cut Line= 6
2466366.42083362584149.0606600642466501.41112939584015.699401274
2467351.65452001583470.9646262082467428.39632162  583397.7092731
 2467518.2203217582680.8223821262467467.74292438582516.015650881
#Sta/Elev= 30
       01704.882  130.341701.068 339.5521692.914 414.2581678.302 466.872 1663.13
 490.6241653.535 533.3791648.277 723.4011643.954 770.9061639.026  843.05 1638.64
1043.9591640.2971065.4391637.803  1207.41634.4631242.5151631.4691270.1651631.596
  1280.71634.314 1397.17 1634.511421.3431635.2641435.6391641.9581449.5621644.756
1481.8121646.906 1498.611645.2961522.1251645.326 1538.251640.772 1600.061640.808
  1701.51641.3752071.9731647.2112096.4981652.7972138.9071671.0082200.4821686.654
#Mann= 9 ,-1 , 0
       0      .1       0  130.34     .05       0  843.05      .1       0
  1207.4    .045       0  1280.7      .1       0 1397.17     .06       0
 1498.61     .05       0 1600.06      .1       0  1701.5     .05       0
#XS Ineff= 2 , 0
                          1486.3         1646.53
Permanent Ineff=
       F       F
Bank Sta=1207.4,1280.7
XS Rating Curve= 0 ,0
Exp/Cntr(USF)=0,0
Exp/Cntr=0.3,0.1

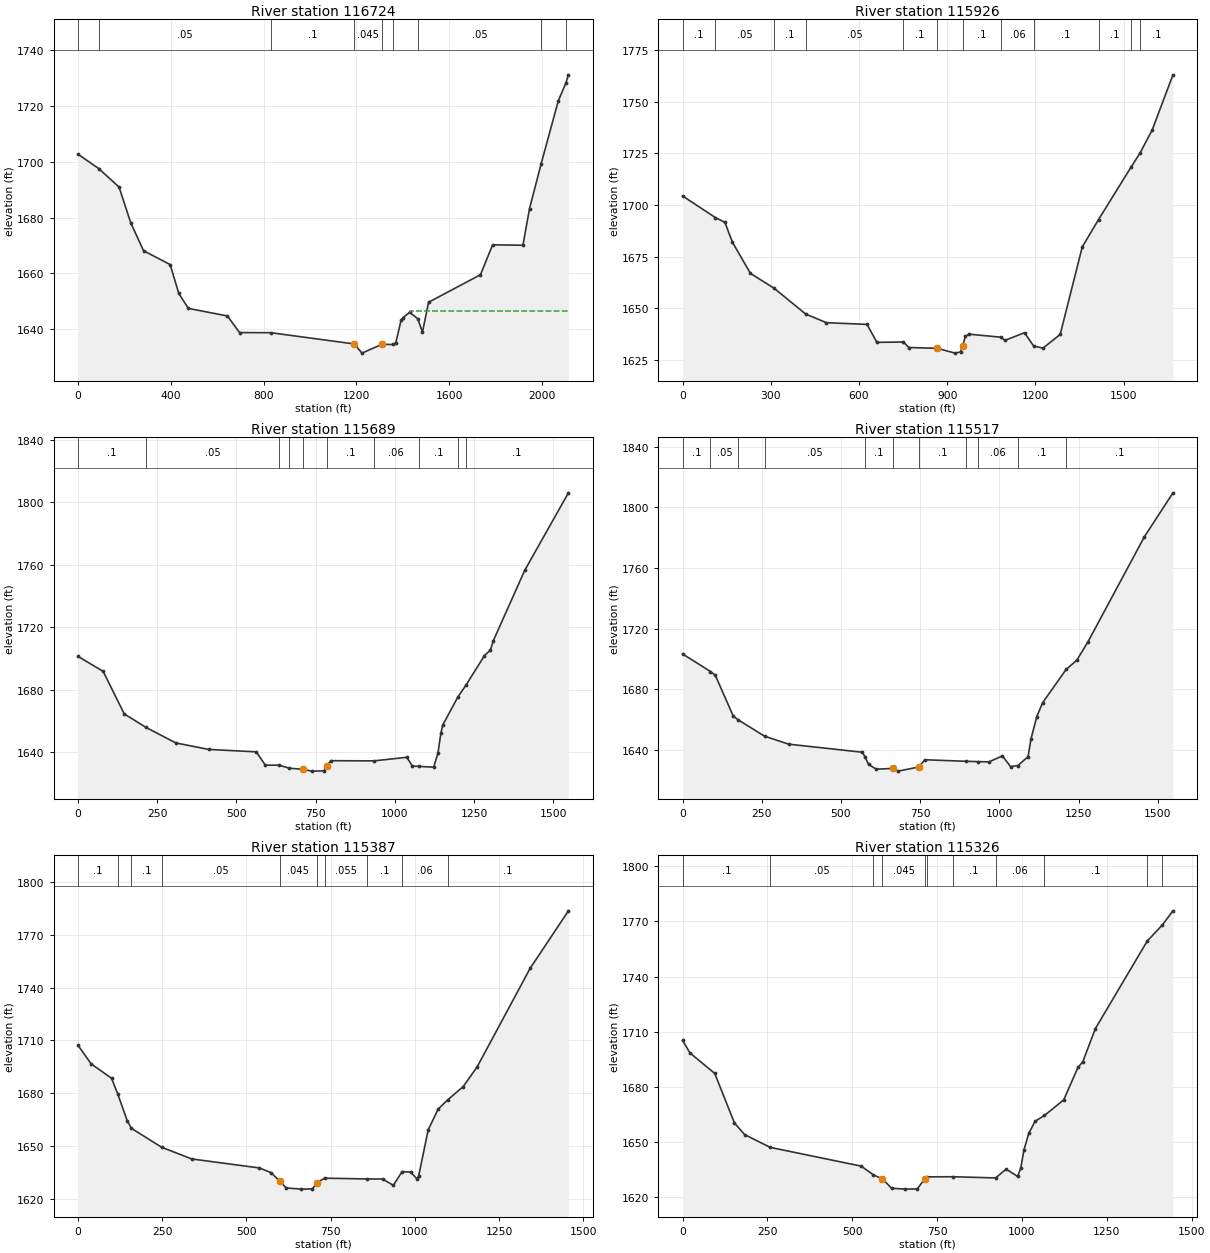
Type RM Length L Ch R = 1 ,116724  ,755.2,798.1,854.8
XS GIS Cut Line= 4
2466388.94618666584146.3118484172467414.98785332583566.103515103
2467623.32118669583453.6035150892468226.44618669583102.561848417
#Sta/Elev= 30
       0 1702.73   89.031697.598   176.7 1690.97   226.9 1678.18   282.4 1668.12
     397 1663.17     434 1652.82   475.4 1647.45   643.7 1644.74   695.9 1638.79
  830.181638.739  1189.8 1634.71  1223.9 1631.41  1308.5 1634.54 1358.311634.511
  1369.4 1635.09  1392.1  1643.2  1401.2 1644.14  1428.7 1646.06 1464.021643.745
  1484.3 1638.97  1510.7 1649.66  1734.2 1659.52  1786.7 1670.25  1917.3  1670.1
  1945.7 1683.23  1995.91699.334  2069.4 1721.79 2102.281728.2622113.344 1731.21
#Mann= 9 ,-1 , 0
       0      .1       0   89.03     .05       0  830.18      .1       0
  1189.8    .045       0  1308.5      .1       0 1358.31     .06       0
 1464.02     .05       0  1995.9     .06       0 2102.28      .1       0
#XS Ineff= 2 , 0
                         1431.51         1646.57
Permanent Ineff=
       F       F
Bank Sta=1189.8,1308.5
XS Rating Curve= 0 ,0
Exp/Cntr(USF)=0,0
Exp/Cntr=0.3,0.1

Type RM Length L Ch R = 1 ,115926  ,227.9,237.4,253.7
XS GIS Cut Line= 4
 2466363.7103506584162.6130751582466694.38927884584073.167135553
2467610.53253903584355.0573694592467962.89533141584458.055724155
#Sta/Elev= 30
       0 1704.36  111.631693.921     144  1691.6   169.4 1682.04     231 1666.93
  311.331659.761   418.71647.309   489.4 1643.12   627.5  1642.3     661 1633.62
  751.091633.774   770.1 1631.12   865.9 1630.75   926.9 1628.41   945.6    1629
   952.3  1631.8   962.3 1636.63   974.9 1637.57 1083.481636.101  1096.2 1634.57
  1163.2 1638.26 1194.281631.862    1226 1630.81  1284.6 1637.45  1359.7 1679.76
 1415.08 1692.96 1525.121718.183  1556.41725.164  1597.8 1736.31  1668.2 1762.91
#Mann= 12 ,-1 , 0
       0      .1       0  111.63     .05       0  311.33      .1       0
   418.7     .05       0  751.09      .1       0   865.9    .045       0
   952.3      .1       0 1083.48     .06       0 1194.28      .1       0
 1415.08      .1       0 1525.12      .1       0  1556.4      .1       0
Bank Sta=865.9,952.3
XS Rating Curve= 0 ,0
Exp/Cntr(USF)=0,0
Exp/Cntr=0.3,0.1

Type RM Length L Ch R = 1 ,115689  ,175.1,171.7,168.1
XS GIS Cut Line= 4
2466382.69618669584177.5618484322466959.77951998584346.311848432
2467334.77952001584587.9785151032467759.77951998584852.561848417
#Sta/Elev= 30
       0  1701.4    79.2 1691.83   145.9 1664.57  214.96 1655.88   308.4 1646.01
   412.6 1641.82   562.7 1640.28   591.2 1631.74  634.121631.765   666.71629.823
   709.5 1629.09     738 1627.93   776.1  1628.1   785.6 1631.32   797.7 1634.61
  934.031634.494  1037.9 1636.78  1055.3 1631.18 1075.071630.974  1122.7 1630.46
  1136.1 1639.48  1145.3 1652.12    1151 1657.35 1199.241675.493 1224.541682.988
  1282.9 1701.88  1301.8 1705.52  1311.2 1711.57  1410.1 1756.521548.004 1806.16
#Mann= 10 ,-1 , 0
       0      .1       0  214.96     .05       0  634.12      .1       0
   666.7     .05       0   709.5    .045       0   785.6      .1       0
  934.03     .06       0 1075.07      .1       0 1199.24      .1       0
 1224.54      .1       0
Bank Sta=709.5,785.6
XS Rating Curve= 0 ,0
Exp/Cntr(USF)=0,0
Exp/Cntr=0.3,0.1

Type RM Length L Ch R = 1 ,115517  ,129.2,130.3,139.6
XS GIS Cut Line= 4
2466339.31600344584216.8227355242466558.86512792584322.531573239
2467420.79872775584802.2870674832467708.10992769584937.811218399
#Sta/Elev= 30
       0 1703.28   88.091691.684     103 1689.31   159.9 1662.34  175.361659.836
  258.841649.046   335.1 1643.78   567.4 1638.46  576.191635.305   586.9 1630.41
   611.5 1627.31   664.7 1627.78   680.3 1626.01   746.1 1628.76   764.4  1633.5
  893.531632.515  931.72 1632.26   967.3 1632.11  1009.3 1636.05  1035.5 1628.97
  1058.31629.678  1090.4 1635.53  1099.6 1647.12  1117.9 1661.91  1136.2 1671.03
 1210.871693.129  1244.1 1699.08  1280.1 1711.47  1457.4 1780.46  1547.8 1809.52
#Mann= 11 ,-1 , 0
       0      .1       0   88.09     .05       0  175.36      .1       0
  258.84     .05       0  576.19      .1       0   664.7    .045       0
   746.1      .1       0  893.53    .055       0  931.72     .06       0
  1058.3      .1       0 1210.87      .1       0
Bank Sta=664.7,746.1
XS Rating Curve= 0 ,0
Exp/Cntr(USF)=0,0
Exp/Cntr=0.5,0.3

Type RM Length L Ch R = 1 ,115387  ,60.7,61.2,63.4
XS GIS Cut Line= 4
2466301.44618666584269.2285151032466776.44618666 584554.64518176
2467047.27952001584794.2285151032467495.19618669585096.311848432
#Sta/Elev= 30
       0 1707.14    38.8 1696.61    99.5 1688.41  118.171679.308   146.2 1664.14
  158.471659.956  248.221649.193   337.4 1642.56   538.5 1637.44     573 1634.78
  598.77  1629.9   618.3 1626.07   663.2  1625.4   696.1 1625.54     709 1628.98
  731.751631.624  858.471631.186   904.4 1631.16     936 1627.54  962.331635.389
   987.5 1635.04  1006.8 1631.18  1011.6 1633.13  1039.7 1659.16  1069.5 1670.96
 1098.581676.346  1143.5 1683.65  1185.3 1694.98  1342.3 1750.911456.012  1783.6
#Mann= 10 ,-1 , 0
       0      .1       0  118.17     .05       0  158.47      .1       0
  248.22     .05       0  598.77    .045       0     709     .05       0
  731.75    .055       0  858.47      .1       0  962.33     .06       0
 1098.58      .1       0
#XS Ineff= 2 , 0
             578 1630.06     729         1630.06
Permanent Ineff=
       F       F
Bank Sta=598.77,709
XS Rating Curve= 0 ,0
Exp/Cntr(USF)=0,0
Exp/Cntr=0.5,0.3

Type RM Length L Ch R = 1 ,115326  ,218.7,198.5,180.9
XS GIS Cut Line= 4
2466288.94618669584292.1451817752466755.61285332 584617.14518176
2467047.27952001584877.5618484322467461.86285332585129.645181775
#Sta/Elev= 30
       0 1705.24    21.7  1698.4    94.8 1687.24   152.7 1660.32   182.5 1653.98
  258.17 1646.99   526.1 1636.79  562.511631.985  588.791629.812   615.8 1624.77
   655.4 1624.26   691.4 1624.38   713.8 1629.86  719.361630.922  796.051631.013
  922.281630.355   953.6 1635.15   987.2 1631.17   996.5 1635.79  1005.9 1645.58
  1019.9 1654.55  1038.7 1661.21 1066.171664.346  1122.9 1672.82    1165 1690.49
  1179.1 1693.56  1216.3 1711.63 1368.821759.214 1413.791768.1131444.898 1775.76
#Mann= 11 ,-1 , 0
       0      .1       0  258.17     .05       0  562.51    .055       0
  588.79    .045       0   713.8      .1       0  719.36    .055       0
  796.05      .1       0  922.28     .06       0 1066.17      .1       0
 1368.82     .12       0 1413.79      .1       0
Bank Sta=588.79,713.8
XS Rating Curve= 0 ,0
Exp/Cntr(USF)=0,0
Exp/Cntr=0.5,0.3

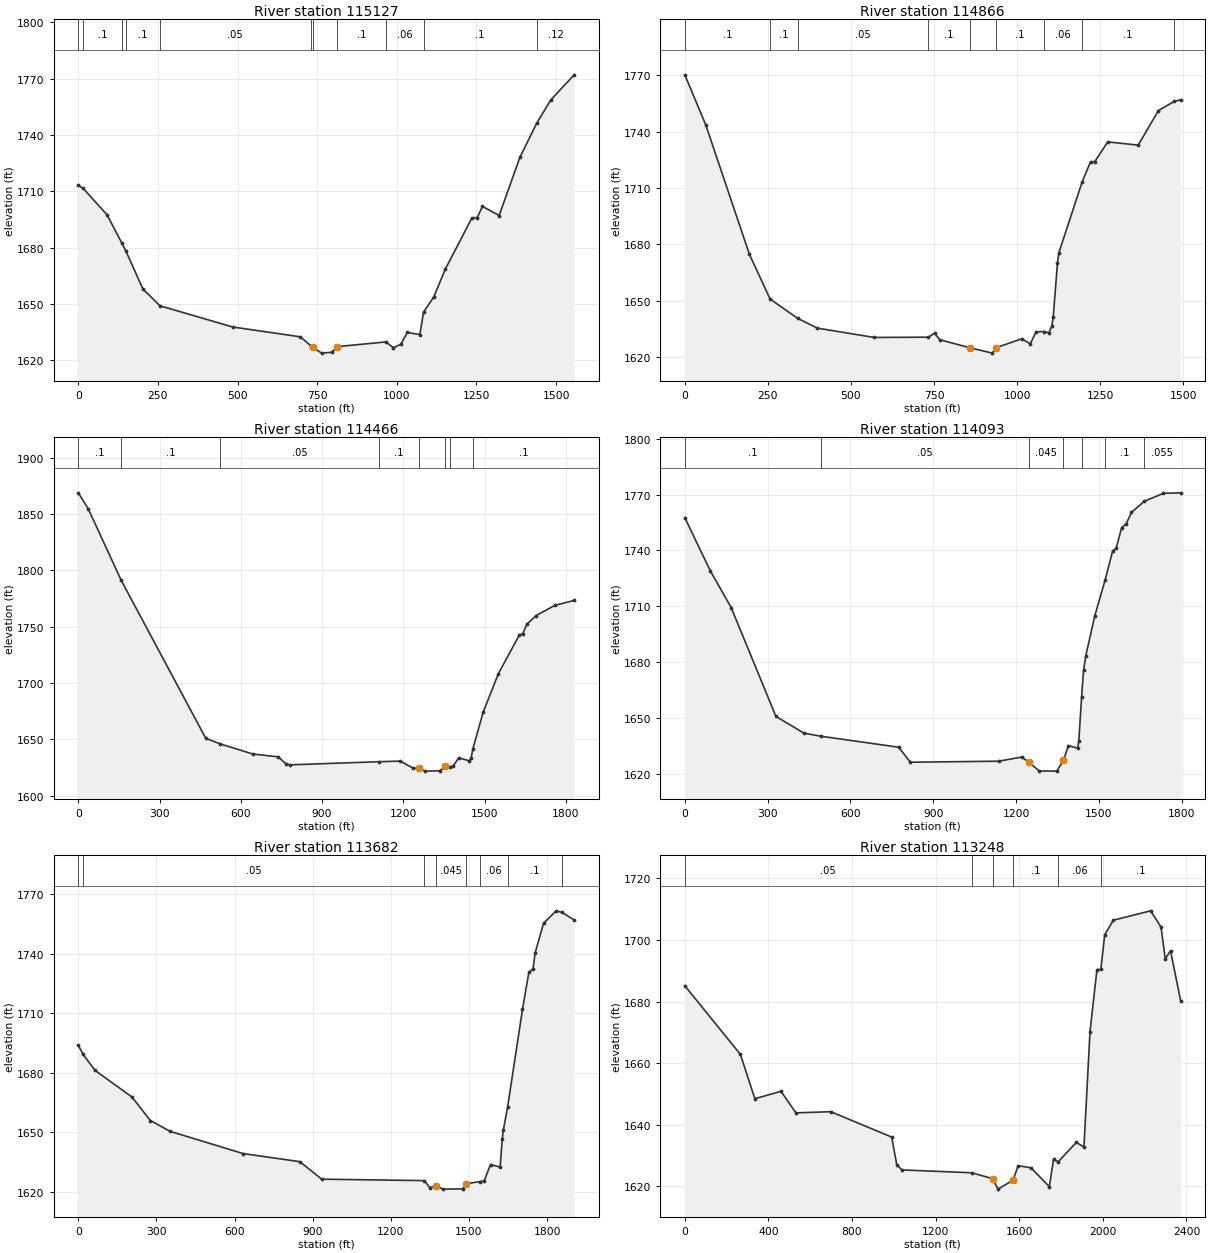
Type RM Length L Ch R = 1 ,115127  ,261.4,261,259
XS GIS Cut Line= 4
2466019.47900727584528.5282826322466285.10634307584653.210501475
2467128.06656177585021.8361919672467442.48259189585160.070825902
#Sta/Elev= 30
       0 1713.21   15.52 1711.49    90.3 1697.47  135.821682.677  149.611678.094
   202.7 1658.01  256.121649.079   484.3  1637.8   696.9 1632.56  729.551627.873
   736.2 1626.98   763.7 1623.88   796.8 1624.35   812.3 1627.34  965.94 1629.83
   989.4 1626.75  1012.8 1628.61    1033 1634.87  1072.3 1633.75 1084.131645.766
  1116.1 1653.78  1152.5 1668.63    1236 1695.87  1252.7 1695.99  1268.8 1701.94
  1321.3 1697.11  1386.8 1728.19    14391746.131  1483.4 1758.58  1556.9 1771.97
#Mann= 11 ,-1 , 0
       0      .1       0   15.52      .1       0  135.82     .05       0
  149.61      .1       0  256.12     .05       0  729.55      .1       0
   736.2    .045       0   812.3      .1       0  965.94     .06       0
 1084.13      .1       0    1439     .12       0
Bank Sta=736.2,812.3
XS Rating Curve= 0 ,0
Exp/Cntr(USF)=0,0
Exp/Cntr=0.3,0.1

Type RM Length L Ch R = 1 ,114866  ,400.2,400.6,401.3
XS GIS Cut Line= 4
2465864.98147523 584710.130644862466182.10798837584905.285422179
 2466941.0432335585206.1490372132467220.22298439 585325.41029002
#Sta/Elev= 30
       0 1770.27    63.1 1743.61   194.6 1674.65  256.851650.887  339.891640.615
   398.9 1635.43   570.2 1630.45  733.211630.605   751.7 1632.72   767.5 1629.26
   857.9 1624.96   925.6 1622.11     938 1625.06  1014.2 1629.73  1039.7 1627.03
  1057.2 1633.43 1080.211633.606  1095.9 1632.99  1104.4 1636.35  1108.8 1641.17
  1121.7 1670.18    1126 1675.64 1195.991713.297  1221.1 1723.95  1234.1  1724.1
  1272.9 1734.57  1364.6 1732.85  1425.5 1751.24 1472.811756.095  1492.3 1756.97
#Mann= 9 ,-1 , 0
       0      .1       0  256.85      .1       0  339.89     .05       0
  733.21      .1       0   857.9    .045       0     938      .1       0
 1080.21     .06       0 1195.99      .1       0 1472.81     .12       0
Bank Sta=857.9,938
XS Rating Curve= 0 ,0
Exp/Cntr(USF)=0,0
Exp/Cntr=0.3,0.1

Type RM Length L Ch R = 1 ,114466  ,376.4,372.7,369.3
XS GIS Cut Line= 4
2465366.25259986584954.0741165092466027.61045633585273.911112671
2466819.07149768585585.616659779 2467044.0415882585683.194048439
#Sta/Elev= 30
       0 1868.69    36.9 1854.34  158.521790.954   470.4 1650.95  522.341646.095
   644.9 1636.93     738 1634.49   765.6 1628.43     781 1627.37 1109.981630.169
  1188.1 1630.69  1236.7 1624.41  1258.2 1624.24  1280.6 1621.81  1335.6 1622.16
  1354.7 1626.35 1370.621625.692  1382.9 1626.08  1404.4 1633.64  1444.1 1630.86
  1450.3 1633.69 1456.521641.461  1494.6 1674.16  1550.5 1708.15  1628.5 1742.71
  1640.7 1743.63  1655.9 1752.14  1689.6 1759.73  1759.4 1768.88  1830.5 1773.25
#Mann= 8 ,-1 , 0
       0      .1       0  158.52      .1       0  522.34     .05       0
 1109.98      .1       0  1258.2    .045       0  1354.7     .06       0
 1370.62    .055       0 1456.52      .1       0
Bank Sta=1258.2,1354.7
XS Rating Curve= 0 ,0
Exp/Cntr(USF)=0,0
Exp/Cntr=0.3,0.1

Type RM Length L Ch R = 1 ,114093  ,413.1,410.6,400.7
XS GIS Cut Line= 4
2465214.46555083585352.5151202032465843.29761108585639.826320146
2466634.75865243585900.0326899052466889.54405616585994.899595546
#Sta/Elev= 30
       0 1757.66    92.3 1729.11     168 1709.34   330.1 1650.88   431.3  1641.9
  491.941640.237     775 1634.31   817.1 1626.25  1137.1 1626.81  1221.3 1629.03
  1246.6 1626.17  1284.5 1621.57  1347.6 1621.47 1371.861627.213  1389.7 1635.18
  1423.4 1633.78  1427.6 1637.84 1437.681661.476  1444.7 1675.59  1452.9 1683.52
  1485.6 1705.02 1523.05 1724.26  1550.1 1739.72  1562.9 1741.16  1582.7 1752.29
  1598.2 1754.11  1618.4 1760.46 1664.351766.404  1733.6 1770.71  1796.4 1770.98
#Mann= 7 ,-1 , 0
       0      .1       0  491.94     .05       0  1246.6    .045       0
 1371.86     .06       0 1437.68    .055       0 1523.05      .1       0
 1664.35    .055       0
Bank Sta=1246.6,1371.86
XS Rating Curve= 0 ,0
Exp/Cntr(USF)=0,0
Exp/Cntr=0.3,0.1

Type RM Length L Ch R = 1 ,113682  ,437.2,433.9,427.7
XS GIS Cut Line= 4
2464921.73338485585845.8230295382465726.74684129586092.476984206
2466583.25947508 586279.500312472466767.57232033586301.184176617
#Sta/Elev= 30
       0  1693.8   17.981689.329    63.8 1681.27   206.1  1667.8   276.7 1655.99
   352.5 1650.55   632.5 1639.38   850.7 1635.29   934.7 1626.49 1328.671625.763
  1349.6 1622.21  1374.9 1623.26  1398.8 1621.48  1476.6 1621.59  1488.8 1624.18
  1542.21625.258  1558.4 1625.54    1583 1633.84  1619.9 1632.55    1628 1646.69
  1632.1 1651.05 1648.961663.014  1705.8 1711.93  1730.2 1730.55  1746.3 1732.28
  1754.4 1740.34  1786.6 1755.23  1834.9  1761.5  1857.81760.693  1904.2 1756.89
#Mann= 8 ,-1 , 0
       0      .1       0   17.98     .05       0 1328.67      .1       0
  1374.9    .045       0  1488.8      .1       0  1542.2     .06       0
 1648.96      .1       0  1857.8      .1       0
Bank Sta=1374.9,1488.8
XS Rating Curve= 0 ,0
Exp/Cntr(USF)=0,0
Exp/Cntr=0.3,0.1

Type RM Length L Ch R = 1 ,113248  ,666.2,655.5,644.9
XS GIS Cut Line= 4
2464802.47213204586138.5551955172465677.95814696 586572.23247845
2466594.10140716586688.7832482382467049.46255424586566.811512413
#Sta/Elev= 30
       0 1685.14   266.1 1662.83   335.1 1648.43   460.1 1650.84   531.5 1643.83
   698.7 1644.21   989.9 1635.95  1014.1 1626.97  1038.3 1625.29 1372.281624.369
  1473.7 1622.44    1498 1619.05  1570.3 1621.96  1594.7 1626.67  1656.2 1625.97
  1743.9 1619.86  1764.1 1628.69 1786.521627.936    1873 1634.24  1909.5 1632.74
  1938.5 1670.23  1971.6 1690.36 1990.281690.458  2008.9 1701.72  2050.3 1706.45
  2228.3 1709.49    2278 1704.28  2298.7 1693.86  2323.6 1696.56    2372  1680.3
#Mann= 6 ,-1 , 0
       0     .05       0 1372.28      .1       0  1473.7    .045       0
  1570.3      .1       0 1786.52     .06       0 1990.28      .1       0
Bank Sta=1473.7,1570.3
XS Rating Curve= 0 ,0
Exp/Cntr(USF)=0,0
Exp/Cntr=0.3,0.1

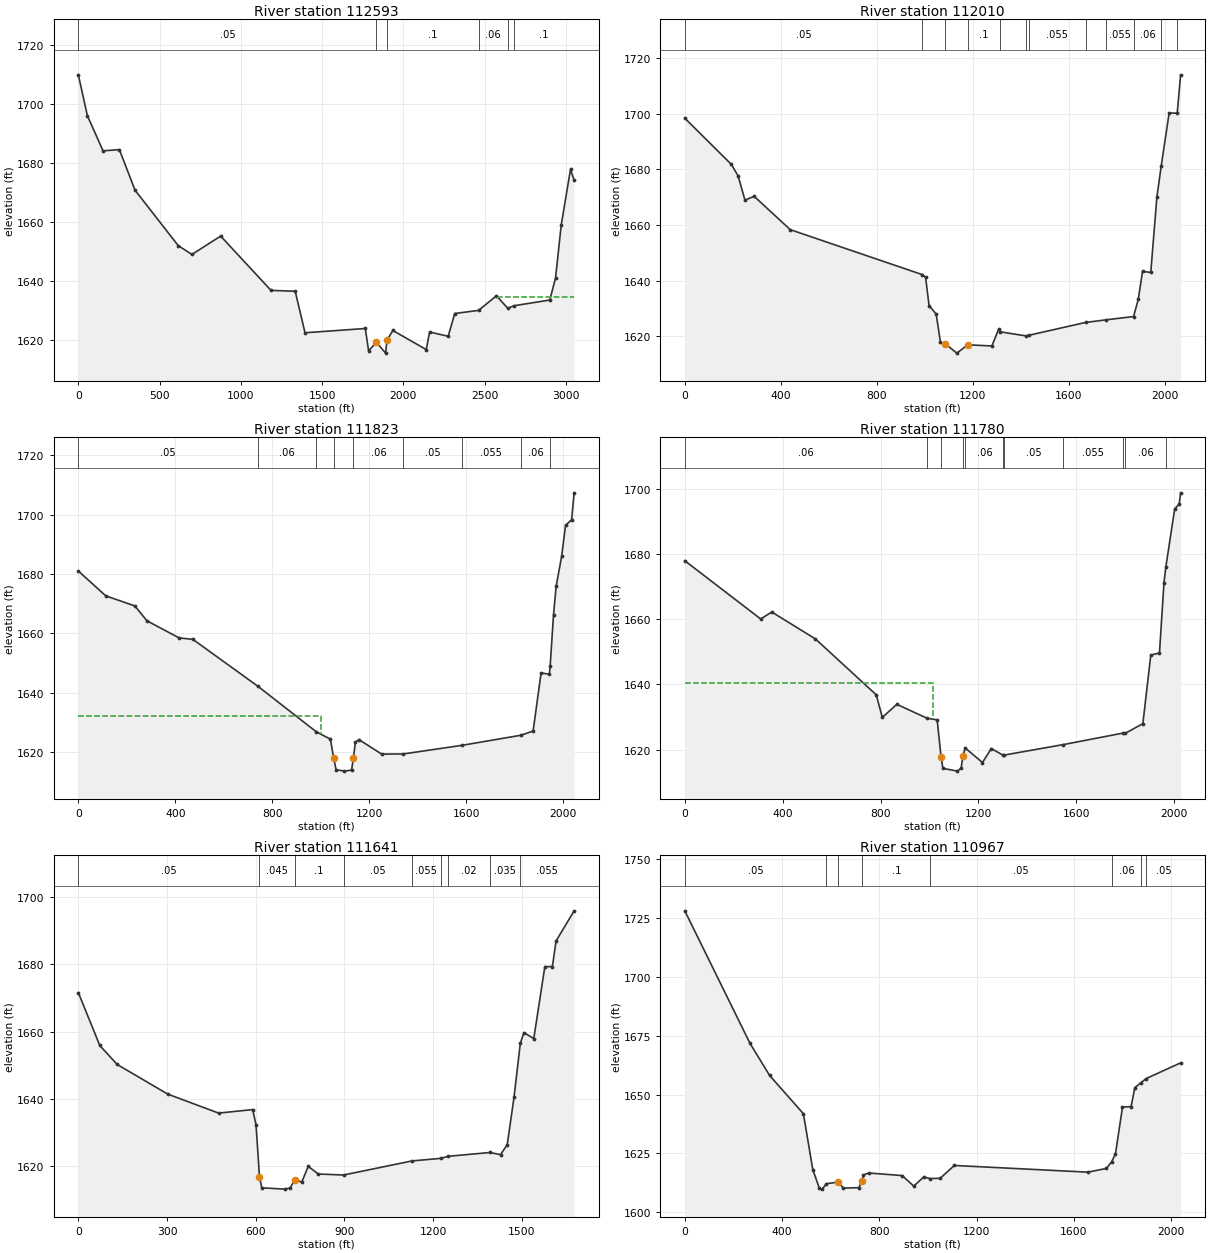
Type RM Length L Ch R = 1 ,112593  ,602.5,582.6,565
XS GIS Cut Line= 5
2464351.46486098587503.6496264892465567.27823134587377.234780641
2466464.01918276 587262.946084572466734.99085234 587205.56384866
2467001.16606683586614.477836224
#Sta/Elev= 30
       01709.757  55.5781695.977 152.0961684.063 252.6351684.479 349.1521670.755
 614.5761652.053 699.0281649.053 875.9771655.2621185.6381636.9171334.7361636.612
1395.2221622.5821766.1981624.031 1786.361616.524  1834.81619.3211891.2011615.705
  1899.31619.9741935.5571623.3582141.4151616.9062161.8581622.8382276.3421621.398
2316.5631629.095 2463.091630.1482572.9751635.076 2643.261630.865 2681.731631.722
 2901.991633.6582937.0851641.171 2972.18 1659.043029.2091677.8283051.5961674.067
#Mann= 6 ,-1 , 0
       0     .05       0  1834.8    .045       0  1899.3      .1       0
 2463.09     .06       0 2643.26    .055       0 2681.73      .1       0
#XS Ineff= 2 , 0
                         2584.25         1634.76
Permanent Ineff=
       F       F
Bank Sta=1834.8,1899.3
XS Rating Curve= 0 ,0
Exp/Cntr(USF)=0,0
Exp/Cntr=0.3,0.1

Type RM Length L Ch R = 1 ,112010  ,200.1,187.8,177.2
XS GIS Cut Line= 4
 2465448.2995529588451.7609703482466206.78862798587960.973921762
2466835.14477352587555.7027983092467154.89997184587291.718855509
#Sta/Elev= 30
       0 1698.45   193.5 1681.86   222.1 1677.68   250.7 1668.95   288.8 1670.34
   439.2 1658.33  990.011642.122  1003.3 1641.13  1017.7 1631.02  1047.5 1627.91
  1065.2 1617.75  1084.3 1617.28  1133.5 1613.88  1179.4 1616.88  1279.4 1616.45
    1308 1622.57 1315.181621.533 1423.571620.051 1434.561620.326 1669.66 1624.92
 1754.751625.859 1869.82 1627.05  1889.2 1633.19  1907.1  1643.3  1941.4 1642.92
    1967  1670.1 1984.891681.214    2018 1700.33 2051.561700.229  2065.8 1714.06
#Mann= 12 ,-1 , 0
       0     .05       0  990.01     .06       0  1084.3    .045       0
  1179.4      .1       0 1315.18     .06       0 1423.57     .05       0
 1434.56    .055       0 1669.66     .05       0 1754.75    .055       0
 1869.82     .06       0 1984.89    .055       0 2051.56     .06       0
Bank Sta=1084.3,1179.4
XS Rating Curve= 0 ,0
Exp/Cntr(USF)=0,0
Exp/Cntr=0.5,0.3

Type RM Length L Ch R = 1 ,111823  ,41.6,42.6,43.7
XS GIS Cut Line= 5
2465695.19618669588727.5618484322466399.36285332588046.311848432
2466463.94618666588033.8118484322466591.02951998 587892.14518176
2467172.27951998587327.561848417
#Sta/Elev= 30
       0 1680.98   113.3 1672.61   233.1 1669.23   283.2 1664.21     416 1658.45
   472.6 1657.97  740.451642.205  981.991626.837  1040.3 1624.36 1053.561618.005
  1063.8 1614.07  1097.7 1613.59  1127.6 1613.95 1135.321618.004  1143.1 1623.25
  1157.6 1624.22  1252.2 1619.31 1341.161619.376 1583.521622.281 1825.881625.666
  1876.8 1627.09  1909.8 1646.69  1943.8  1646.2 1947.061648.845    1961 1666.24
    1972 1675.87  1994.7 1685.98  2010.6 1696.37  2035.7 1698.23 2046.18 1707.31
#Mann= 9 ,-1 , 0
       0     .05       0  740.45     .06       0  981.99    .055       0
 1053.56    .045       0 1135.32     .06       0 1341.16     .05       0
 1583.52    .055       0 1825.88     .06       0 1947.06    .055       0
#XS Ineff= 2 , 0
         1000.89 1632.25
Permanent Ineff=
       F       F
Bank Sta=1053.56,1135.32
XS Rating Curve= 0 ,0
Exp/Cntr(USF)=0,0
Exp/Cntr=0.5,0.3

Type RM Length L Ch R = 1 ,111780  ,135.4,139.2,142.8
XS GIS Cut Line= 4
2465795.19618669588829.6451817752466472.27951998 588085.89518176
2466649.36285335587894.2285150892467186.86285335587356.728515089
#Sta/Elev= 30
       0 1677.94   310.3 1660.08   355.6 1662.22     534 1653.96   782.7 1636.82
   807.4  1629.9   866.8 1633.92  989.911629.653  1031.7 1629.15 1047.451617.839
  1054.9 1614.29  1114.4 1613.43  1129.7 1614.35    1137 1618.19 1146.651620.501
  1216.8 1616.07  1253.1 1620.35 1302.551618.251  1305.51618.352 1547.421621.567
 1792.291625.107 1801.231625.048  1872.5 1627.99    1905 1649.04  1940.4 1649.63
  1958.8 1671.16 1966.471676.043  2002.6 1693.82  2021.1 1695.342026.875 1698.76
#Mann= 11 ,-1 , 0
       0     .06       0  989.91    .055       0 1047.45    .045       0
    1137    .055       0 1146.65     .06       0 1302.55      .1       0
  1305.5     .05       0 1547.42    .055       0 1792.29    .035       0
 1801.23     .06       0 1966.47    .055       0
#XS Ineff= 2 , 0
         1015.88 1640.55
Permanent Ineff=
       F       F
Bank Sta=1047.45,1137
XS Rating Curve= 0 ,0
Exp/Cntr(USF)=0,0
Exp/Cntr=0.5,0.3

Type RM Length L Ch R = 1 ,111641  ,672.2,673.6,671.1
XS GIS Cut Line= 4
 2466258.8417998588656.2555739262466545.13424481588202.649362354
 2467043.3574608587700.7080626642467351.95840802587395.825199149
#Sta/Elev= 30
       0 1671.56    72.6 1655.87   131.4 1650.24   302.5 1641.44   474.6  1635.8
   589.8 1636.84   601.1 1632.38  612.891616.855   620.6 1613.62   698.6 1613.23
   716.4  1613.6   732.5 1615.99   755.9 1615.34   777.8 1619.99   811.7 1617.72
  897.351617.421  1128.8  1621.6 1226.171622.364 1251.511622.979 1392.561624.106
  1428.3 1623.47    1451 1626.43  1473.9 1640.44 1495.331656.544  1507.5 1659.69
  1540.8 1657.92  1578.2 1679.27  1603.7 1679.29  1616.2 1686.91  1677.4 1695.85
#Mann= 9 ,-1 , 0
       0     .05       0  612.89    .045       0   732.5      .1       0
  897.35     .05       0  1128.8    .055       0 1226.17    .035       0
 1251.51     .02       0 1392.56    .035       0 1495.33    .055       0
Bank Sta=612.89,732.5
XS Rating Curve= 0 ,0
Exp/Cntr(USF)=0,0
Exp/Cntr=0.3,0.1

Type RM Length L Ch R = 1 ,110967  ,597.8,584.1,571.6
XS GIS Cut Line= 4
2466608.34166773589098.7075343932466883.47986164588804.978921982
2467515.55409088588132.0057720272467954.28796764587570.575133115
#Sta/Elev= 30
       0 1728.09   268.3 1671.72   348.7 1658.13   487.6 1641.86   526.1 1618.14
   553.3 1610.15     565 1609.82  582.091612.133   629.3 1612.77   652.3 1610.28
   714.7 1610.42   729.1 1613.11   734.5 1615.85   756.5 1616.67   893.7 1615.58
   941.1  1611.1   981.5 1614.92 1009.71 1614.31  1049.9 1614.43    1108 1619.88
  1657.1 1617.03  1733.3 1618.63 1754.351621.377  1770.5 1624.82  1799.3 1644.66
  1834.8 1644.91    1850 1652.93 1876.021655.129 1896.911656.817  2038.3 1663.48
#Mann= 8 ,-1 , 0
       0     .05       0  582.09      .1       0   629.3    .045       0
   729.1      .1       0 1009.71     .05       0 1754.35     .06       0
 1876.02    .055       0 1896.91     .05       0
Bank Sta=629.3,729.1
XS Rating Curve= 0 ,0
Exp/Cntr(USF)=0,0
Exp/Cntr=0.3,0.1

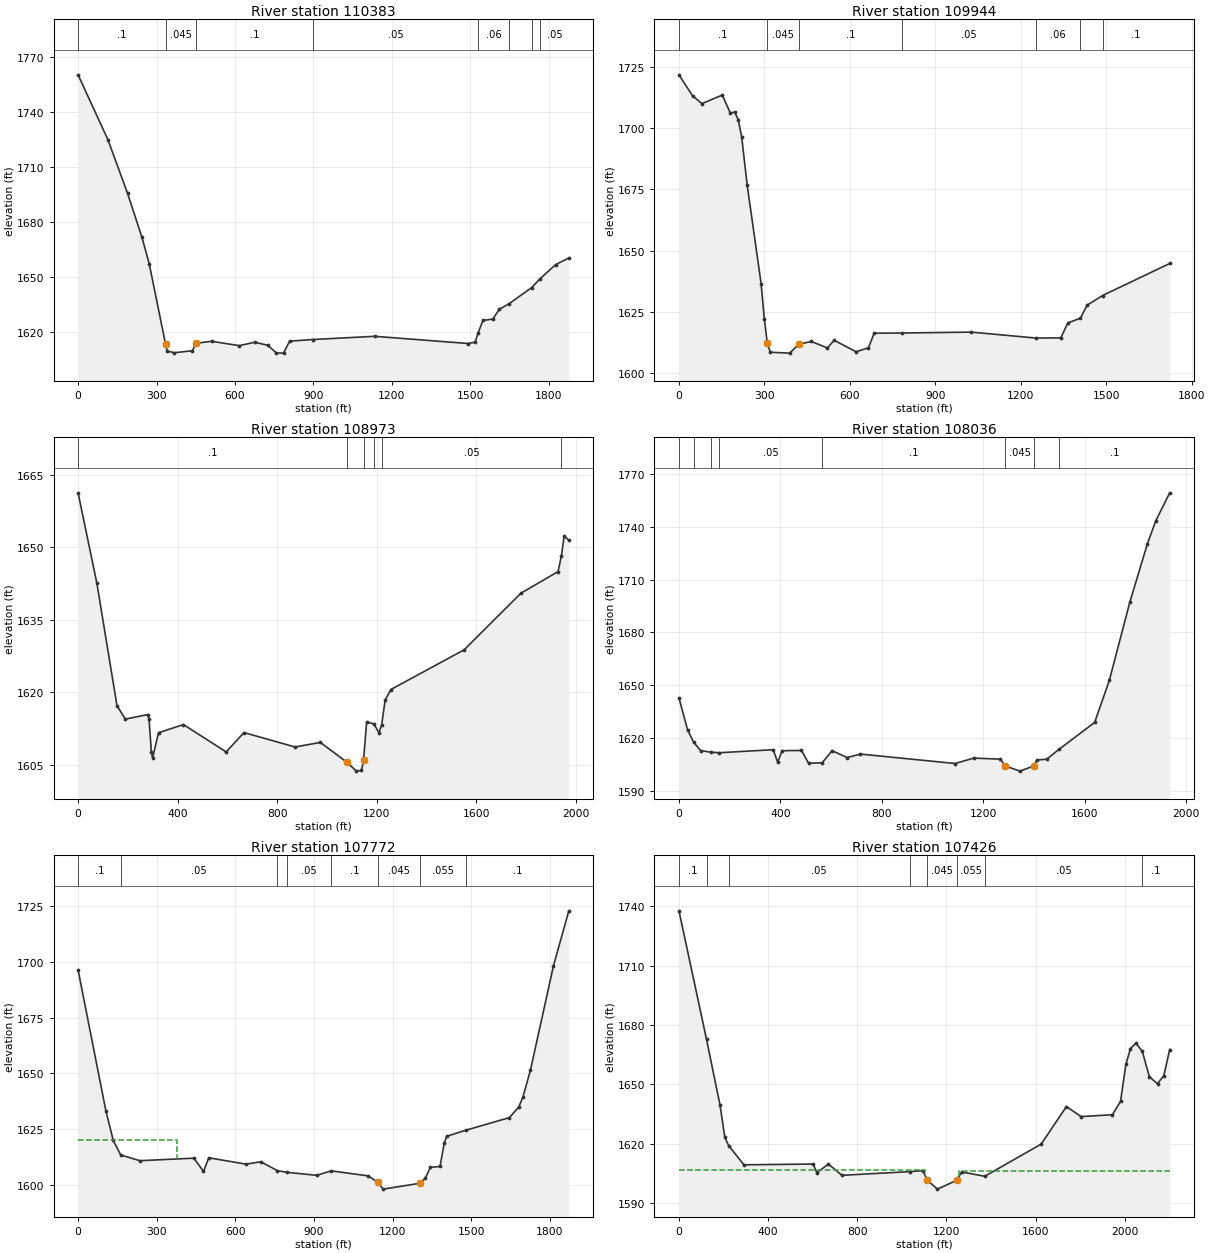
Type RM Length L Ch R = 1 ,110383  ,469.5,438.8,415.5
XS GIS Cut Line= 4
2467344.52224061589288.3298031652467452.34666795589094.989450692
2467920.82521433588262.1387015762468229.42616155587633.782556039
#Sta/Elev= 30
       0 1760.29   114.4 1724.87   189.4  1695.7   244.4 1671.78     272 1657.47
   334.8 1613.52   340.8  1609.9   368.3 1608.99   437.2 1610.06     451 1614.11
   510.6 1615.21   616.2 1612.84   675.5 1614.68   725.5 1613.04   758.4 1608.84
     786 1608.76   808.9 1615.29  897.88 1616.17  1134.8 1617.92  1491.6    1614
  1518.5 1614.73 1529.621619.575  1548.4 1626.58  1586.1 1627.29  1611.2  1632.6
 1648.661635.695 1734.311644.374  1767.71649.355  1826.7 1656.98    1877 1660.57
#Mann= 8 ,-1 , 0
       0      .1       0   334.8    .045       0     451      .1       0
  897.88     .05       0 1529.62     .06       0 1648.66     .05       0
 1734.31      .1       0  1767.7     .05       0
Bank Sta=334.8,451
XS Rating Curve= 0 ,0
Exp/Cntr(USF)=0,0
Exp/Cntr=0.3,0.1

Type RM Length L Ch R = 1 ,109944  ,976.6,970.9,972.7
XS GIS Cut Line= 4
2467905.95287953589336.6648912832467954.28796764589158.196873616
2468010.05922317588321.628040799 2468359.5590911587715.580397469
#Sta/Elev= 30
       0  1721.8    47.7 1713.26    80.6 1710.04   152.1 1713.54     180 1706.28
   196.2 1706.57   208.3  1703.4   220.3 1696.34   239.5 1676.79   288.4 1636.59
   299.6 1622.25     3101612.328   320.5 1608.52   388.7 1608.16   420.7 1611.79
   464.8 1612.92   520.9 1610.28     545  1613.4   621.8 1608.72   665.3 1610.33
   685.3 1616.29  784.131616.381  1026.5 1616.74 1252.411614.328  1340.5 1614.39
  1365.5  1620.5 1409.611622.433  1432.8 1627.72 1487.091631.678  1722.9 1644.77
#Mann= 7 ,-1 , 0
       0      .1       0     310    .045       0   420.7      .1       0
  784.13     .05       0 1252.41     .06       0 1409.61     .05       0
 1487.09      .1       0
Bank Sta=310,420.7
XS Rating Curve= 0 ,0
Exp/Cntr(USF)=0,0
Exp/Cntr=0.3,0.1

Type RM Length L Ch R = 1 ,108973  ,872.3,937.7,1006.2
XS GIS Cut Line= 4
2468043.52197648589373.8457282972468857.78230709588845.877842697
2468943.29823222588511.2503095712469051.12265956587864.303745526
#Sta/Elev= 30
       0 1661.26    75.4 1642.61   156.4 1617.26   189.8  1614.5   280.3 1615.44
     285 1614.56   294.6 1607.61   299.4  1606.5   323.2 1611.68   423.4 1613.37
     595 1607.72   666.5 1611.72   871.5 1608.74   973.7 1609.68  1080.9 1605.55
  1118.4 1603.75  1138.7 1603.91  1146.9 1605.96  1159.3 1613.89 1188.371613.523
  1208.9 1611.64 1219.881613.357  1233.6 1618.38  1256.5 1620.61  1551.4 1628.83
  1779.2 1640.52  1928.5 1644.98 1941.951648.284  1952.9 1652.26  1971.7  1651.5
#Mann= 6 ,-1 , 0
       0      .1       0  1080.9    .045       0  1146.9     .06       0
 1188.37    .055       0 1219.88     .05       0 1941.95      .1       0
Bank Sta=1080.9,1146.9
XS Rating Curve= 0 ,0
Exp/Cntr(USF)=0,0
Exp/Cntr=0.3,0.1

Type RM Length L Ch R = 1 ,108036  ,290.5,263.8,259.2
XS GIS Cut Line= 4
2467998.90497206589563.4679970692468764.83021455589269.739384658
2469519.60120594589392.4361468042469865.38299017589451.925486027
#Sta/Elev= 30
       0 1642.83    34.1  1624.6   57.761617.663    85.5 1612.91  125.261611.998
  159.211611.678   371.9  1613.4   389.7 1606.21   406.8 1612.82   483.4 1612.98
   511.3 1605.73  565.011605.965   603.9 1612.82   663.9 1608.95   715.6 1610.92
  1089.7 1605.55  1162.7 1608.62    1268 1608.04 1287.561604.172    1345 1601.23
 1399.541604.171  1412.1  1607.6  1450.7 1607.97 1499.091613.597  1639.8 1628.88
  1697.8 1652.79  1778.9 1697.34  1847.9 1730.32  1880.7 1743.33  1935.9  1759.3
#Mann= 8 ,-1 , 0
       0      .1       0   57.76     .05       0  125.26      .1       0
  159.21     .05       0  565.01      .1       0 1287.56    .045       0
 1399.54    .055       0 1499.09      .1       0
Bank Sta=1287.56,1399.54
XS Rating Curve= 0 ,0
Exp/Cntr(USF)=0,0
Exp/Cntr=0.3,0.1

Type RM Length L Ch R = 1 ,107772  ,312,345.9,358.8
XS GIS Cut Line= 4
2467902.23479582589630.3935036942468601.23453169589518.850992652
2469363.44169048589596.9307503822469761.27664653589615.521168889
#Sta/Elev= 30
       0 1696.34   105.8 1633.39   134.2 1619.99  162.681613.481   235.5 1610.92
     442 1612.05   478.5 1606.09   498.7 1612.22   640.5 1609.38   697.2 1610.44
  760.391606.459  797.891605.709   910.4 1604.36  966.081606.374  1107.4 1604.11
    1144 1601.18  1163.7 1598.19  1303.8  1600.8  1324.6 1603.03  1343.9 1607.93
  1380.9 1608.34  1396.9 1618.72  1405.9 1621.82 1480.241624.599  1645.5  1630.2
  1681.6 1634.99  1697.6  1639.6  1725.6 1651.31  1813.7 1698.17  1872.3 1722.79
#Mann= 8 ,-1 , 0
       0      .1       0  162.68     .05       0  760.39      .1       0
  797.89     .05       0  966.08      .1       0    1144    .045       0
  1303.8    .055       0 1480.24      .1       0
#XS Ineff= 2 , 0
           377.3    1620
Permanent Ineff=
       F       F
Bank Sta=1144,1303.8
XS Rating Curve= 0 ,0
Exp/Cntr(USF)=0,0
Exp/Cntr=0.5,0.3

Type RM Length L Ch R = 1 ,107426  ,71.4,70.4,69.9
XS GIS Cut Line= 4
2467786.97420108589916.6859487152468732.69618669589777.561848417
2469199.36285335589956.7285150892469936.86285332589844.228515103
#Sta/Elev= 30
       0 1737.81  123.661672.789   184.7 1639.38   205.8 1623.25  222.991619.055
   291.5 1609.37   602.2 1609.75   618.4 1605.39   670.7 1609.72   731.6 1604.05
 1035.481605.918  1094.7 1606.44 1113.861601.578  1159.8 1597.07 1247.04 1601.58
  1268.1 1605.75 1372.081603.578  1625.1 1619.84  1738.4 1638.82  1804.4 1633.75
  1944.8  1634.7  1981.2 1641.46  2005.4 1660.23  2025.7 1668.14    2050 1670.86
 2078.691666.813  2110.6 1653.89  2147.1 1650.35  2175.4  1654.5  2201.8 1667.68
#Mann= 8 ,-1 , 0
       0      .1       0  123.66      .1       0  222.99     .05       0
 1035.48     .06       0 1113.86    .045       0 1247.04    .055       0
 1372.08     .05       0 2078.69      .1       0
#XS Ineff= 2 , 0
         1105.01 1606.85    1257         1606.13
Permanent Ineff=
       F       F
Bank Sta=1113.86,1247.04
XS Rating Curve= 0 ,0
Exp/Cntr(USF)=0,0
Exp/Cntr=0.5,0.3