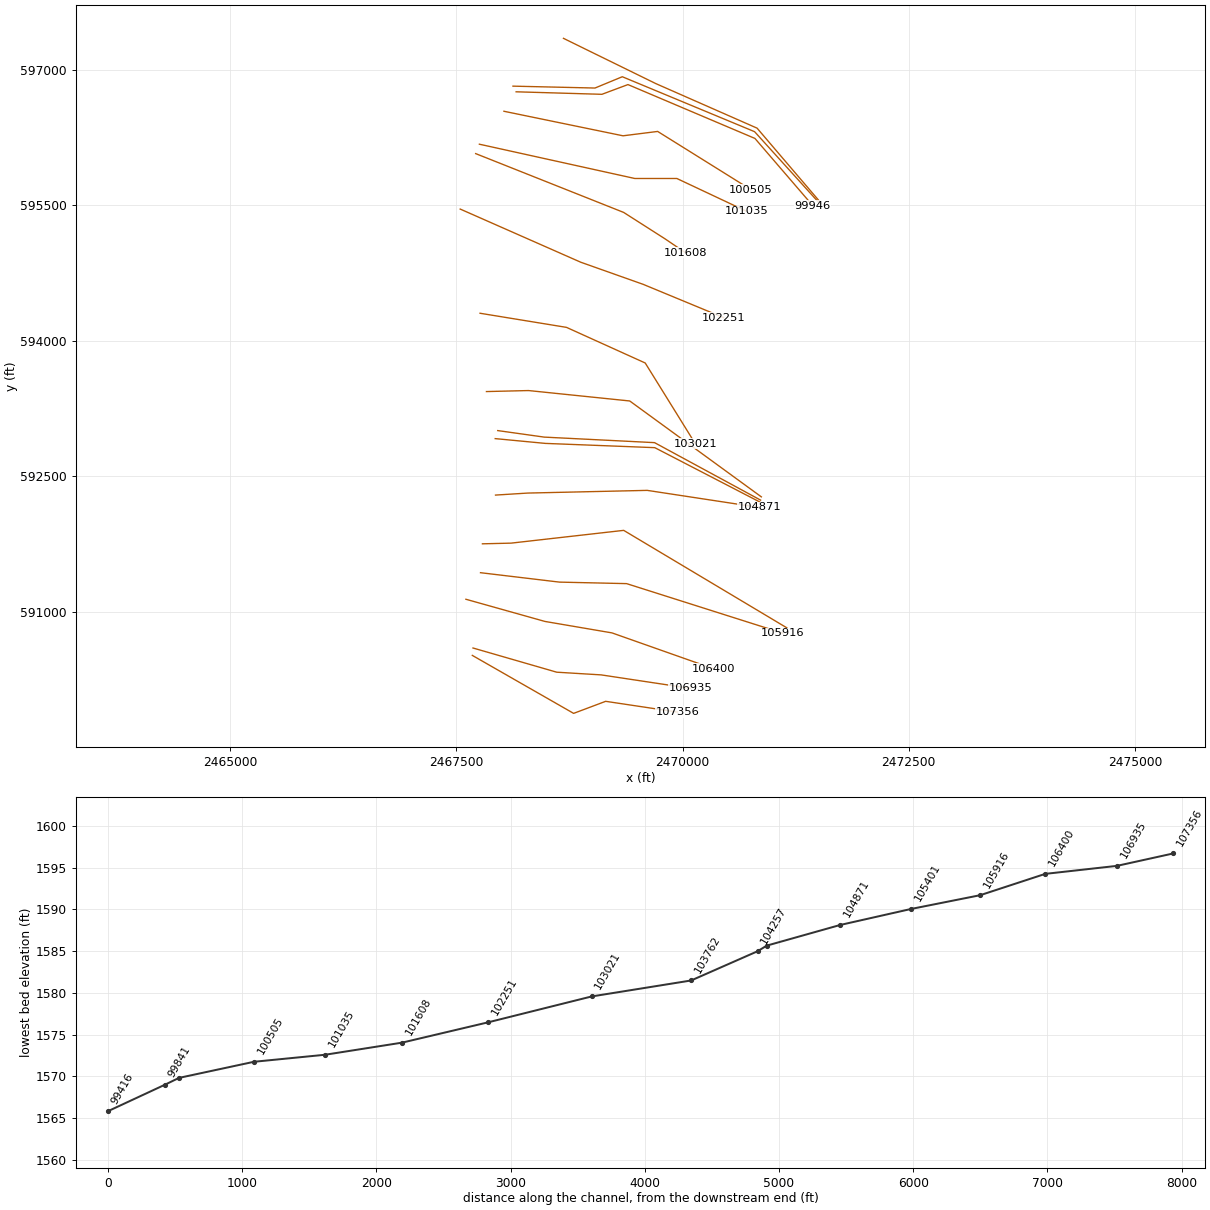
HEC-RAS study SFSBPOTOMC.prj: SFSBPOTOMC

--- SFSBPOTOMC.g01 (geometry) --- (continued)

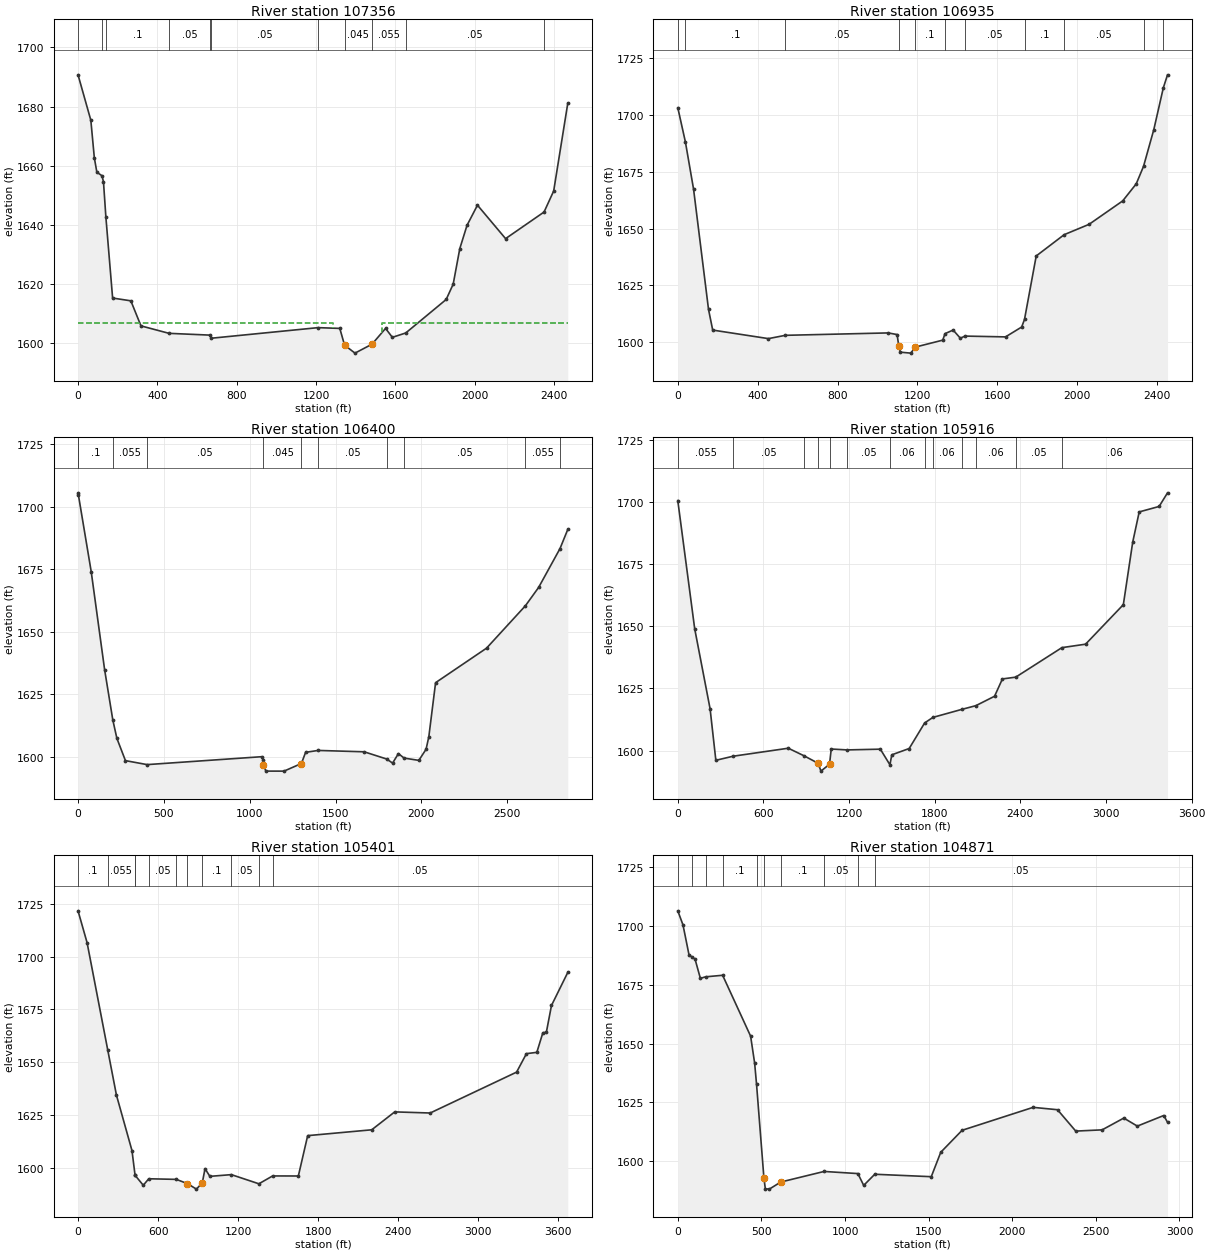
Type RM Length L Ch R = 1 ,107356  ,441.6,420.5,399.8
XS GIS Cut Line= 4
2467675.43169004590519.0155083392468795.19618666589877.561848432
2469149.36285335590010.8951817752469941.02952003 589892.14518179
#Sta/Elev= 30
       0 1690.76    64.6  1675.4    82.2 1662.72    94.9 1657.85  120.641656.656
   128.3 1654.62   140.5 1642.62   174.4 1615.31   266.3 1614.37   317.3  1605.9
  458.791603.379  665.471602.777  670.991601.718 1210.291605.304  1319.9 1605.05
  1343.9  1599.4  1396.4 1596.69  1482.3 1599.71  1550.7 1605.04  1584.9 1602.03
 1652.421603.501  1856.4 1614.83  1891.7 1620.01  1925.1 1632.05  1961.5  1639.9
  2014.1  1646.7  2155.9 1635.39 2349.871644.387  2398.4 1651.49  2469.4 1681.11
#Mann= 11 ,-1 , 0
       0      .1       0  120.64     .06       0   140.5      .1       0
  458.79     .05       0  665.47     .06       0  670.99     .05       0
 1210.29     .06       0  1343.9    .045       0  1482.3    .055       0
 1652.42     .05       0 2349.87      .1       0
#XS Ineff= 2 , 0
         1283.73 1606.91  1530.5         1606.81
Permanent Ineff=
       F       F
Bank Sta=1343.9,1482.3
XS Rating Curve= 0 ,0
Exp/Cntr(USF)=0,0
Exp/Cntr=0.5,0.3

Type RM Length L Ch R = 1 ,106935  ,552.5,534.7,510.8
XS GIS Cut Line= 4
2467682.86785744590600.8133497622468608.67069909 590333.11132326
2469099.45774768590303.3666536492470084.74992855590154.643305593
#Sta/Elev= 30
       0 1703.27   38.23 1688.14      79 1667.39   153.9 1614.42   174.8 1605.35
   453.7 1601.59  538.451603.041  1053.2  1604.1  1098.1 1603.38  1106.1 1598.45
  1114.1 1595.62  1166.2  1595.2  1189.7 1597.87  1326.5 1600.92 1337.961603.781
  1378.6 1605.36  1414.6 1601.77 1437.771602.705  1640.8 1602.35  1721.7  1606.7
 1735.821610.036  1794.5 1637.99 1934.471647.366  2059.1 1651.92  2227.4 1662.23
  2295.2 1669.74 2331.761677.452  2383.1  1693.6 2431.08 1712.11  2451.9 1717.76
#Mann= 11 ,-1 , 0
       0      .1       0   38.23      .1       0  538.45     .05       0
  1106.1    .045       0  1189.7      .1       0 1337.96     .06       0
 1437.77     .05       0 1735.82      .1       0 1934.47     .05       0
 2331.76      .1       0 2431.08      .1       0
Bank Sta=1106.1,1189.7
XS Rating Curve= 0 ,0
Exp/Cntr(USF)=0,0
Exp/Cntr=0.3,0.1

Type RM Length L Ch R = 1 ,106400  ,476.5,484.4,506.3
XS GIS Cut Line= 4
2467604.78809971591139.9354864662468478.53776954590894.541962173
2469218.43642612590768.1271163252470345.01578765590370.292160274
#Sta/Elev= 30
       0 1705.56     2.71704.506    76.8 1674.04   154.9  1634.8  202.611614.717
   226.3 1607.36   276.2 1598.44  402.521596.846  1070.1 1600.01  1078.2 1598.68
 1080.27 1596.71  1094.4 1594.25  1199.9 1594.24  1301.4 1597.29  1325.7 1601.76
 1398.921602.516    1667 1601.97 1798.431599.072  1832.4 1597.45  1866.4 1601.25
 1899.361599.458  1985.4 1598.54  2027.6    1603  2043.6 1608.03  2082.9 1629.62
  2379.7 1643.42 2605.831660.354    2683  1667.7 2807.681683.256  2852.9  1690.9
#Mann= 11 ,-1 , 0
       0      .1       0     2.7      .1       0  202.61    .055       0
  402.52     .05       0 1080.27    .045       0  1301.4      .1       0
 1398.92     .05       0 1798.43     .06       0 1899.36     .05       0
 2605.83    .055       0 2807.68     .05       0
Bank Sta=1080.27,1301.4
XS Rating Curve= 0 ,0
Exp/Cntr(USF)=0,0
Exp/Cntr=0.3,0.1

Type RM Length L Ch R = 1 ,105916  ,511.1,515.5,518
XS GIS Cut Line= 4
2467766.02951998591433.8118484322468638.94618669591329.645181775
2469380.61285332591312.9785150892471105.61285332590765.061848432
#Sta/Elev= 30
       0 1700.67   118.4 1649.05   226.3  1616.8   266.6 1596.05  387.481597.697
   774.2 1600.92  884.541597.863   983.3 1594.85  1002.9 1591.69    1063 1594.47
    1075  1600.6 1185.361600.236    1419 1600.54 1486.191594.237  1499.1 1598.26
    1621  1600.8 1729.461611.102 1787.211613.337    1988 1616.54  2088.41618.069
  2219.2 1621.86  2274.1 1628.83 2367.371629.547 2690.781641.438  2856.7 1642.83
  3121.4 1658.76    3187 1683.94  3232.5 1696.12    3372 1698.323430.891 1703.81
#Mann= 13 ,-1 , 0
       0    .055       0  387.48     .05       0  884.54      .1       0
   983.3    .045       0    1063      .1       0 1185.36     .05       0
 1486.19     .06       0 1729.46     .05       0 1787.21     .06       0
    1988    .055       0  2088.4     .06       0 2367.37     .05       0
 2690.78     .06       0
Bank Sta=983.3,1063
XS Rating Curve= 0 ,0
Exp/Cntr(USF)=0,0
Exp/Cntr=0.3,0.1

Type RM Length L Ch R = 1 ,105401  ,531.8,529.1,524.7
XS GIS Cut Line= 4
2467786.97420108591753.419297198 2468103.0113157591760.855464601
2469348.56935567591902.1426452542471151.83995085590823.898371846
#Sta/Elev= 30
       0 1721.62    67.9 1706.56  222.751655.816   287.9 1634.49   404.4 1608.26
  427.091596.813  427.871596.559     489 1591.86  530.251594.937  736.56 1594.65
   820.3 1592.64   887.5 1590.04   931.6 1593.07   951.9 1599.73   988.1 1596.08
 1149.181596.893 1355.491592.568 1458.651596.276  1651.4 1596.25  1721.3 1615.33
  2201.4 1618.09  2373.8 1626.56  2639.5 1626.03  3287.3 1645.36  3360.9 1654.09
  3438.9 1654.71    3484 1663.98  3510.2 1664.19  3548.7 1676.87  3670.7 1692.48
#Mann= 11 ,-1 , 0
       0      .1       0  222.75    .055       0  427.09     .05       0
  427.87    .055       0  530.25     .05       0  736.56      .1       0
   820.3    .045       0   931.6      .1       0 1149.18     .05       0
 1355.49     .06       0 1458.65     .05       0
Bank Sta=820.3,931.6
XS Rating Curve= 0 ,0
Exp/Cntr(USF)=0,0
Exp/Cntr=0.3,0.1

Type RM Length L Ch R = 1 ,104871  ,549.6,546.4,543.4
XS GIS Cut Line= 4
2467931.97946545592292.5414339012468288.91550079592314.849936128
2469608.83521476592344.5946057292470845.19618669592156.034070641
#Sta/Elev= 30
       0 1706.52    31.2 1700.49    66.9 1687.86   83.781686.916     103 1686.01
     135 1677.79  166.251678.443   268.11679.102   435.5 1653.19   459.5 1641.76
  470.851632.802  515.231592.671   523.5 1588.28   547.3 1588.12   615.5 1591.13
  874.88 1595.64 1076.891594.734  1111.7 1589.71  1177.91594.446  1515.8 1593.41
  1572.4 1603.79  1700.1 1613.15  2124.9 1622.91  2270.6  1621.9  2379.7 1612.81
  2537.7 1613.34  2667.1 1618.35    2748 1614.93  2905.8 1619.442928.545 1616.57
#Mann= 10 ,-1 , 0
       0      .1       0   83.78     .12       0  166.25     .05       0
   268.1      .1       0  470.85      .1       0  515.23    .045       0
   615.5      .1       0  874.88     .05       0 1076.89     .06       0
  1177.9     .05       0
Bank Sta=515.23,615.5
XS Rating Curve= 0 ,0
Exp/Cntr(USF)=0,0
Exp/Cntr=0.5,0.3

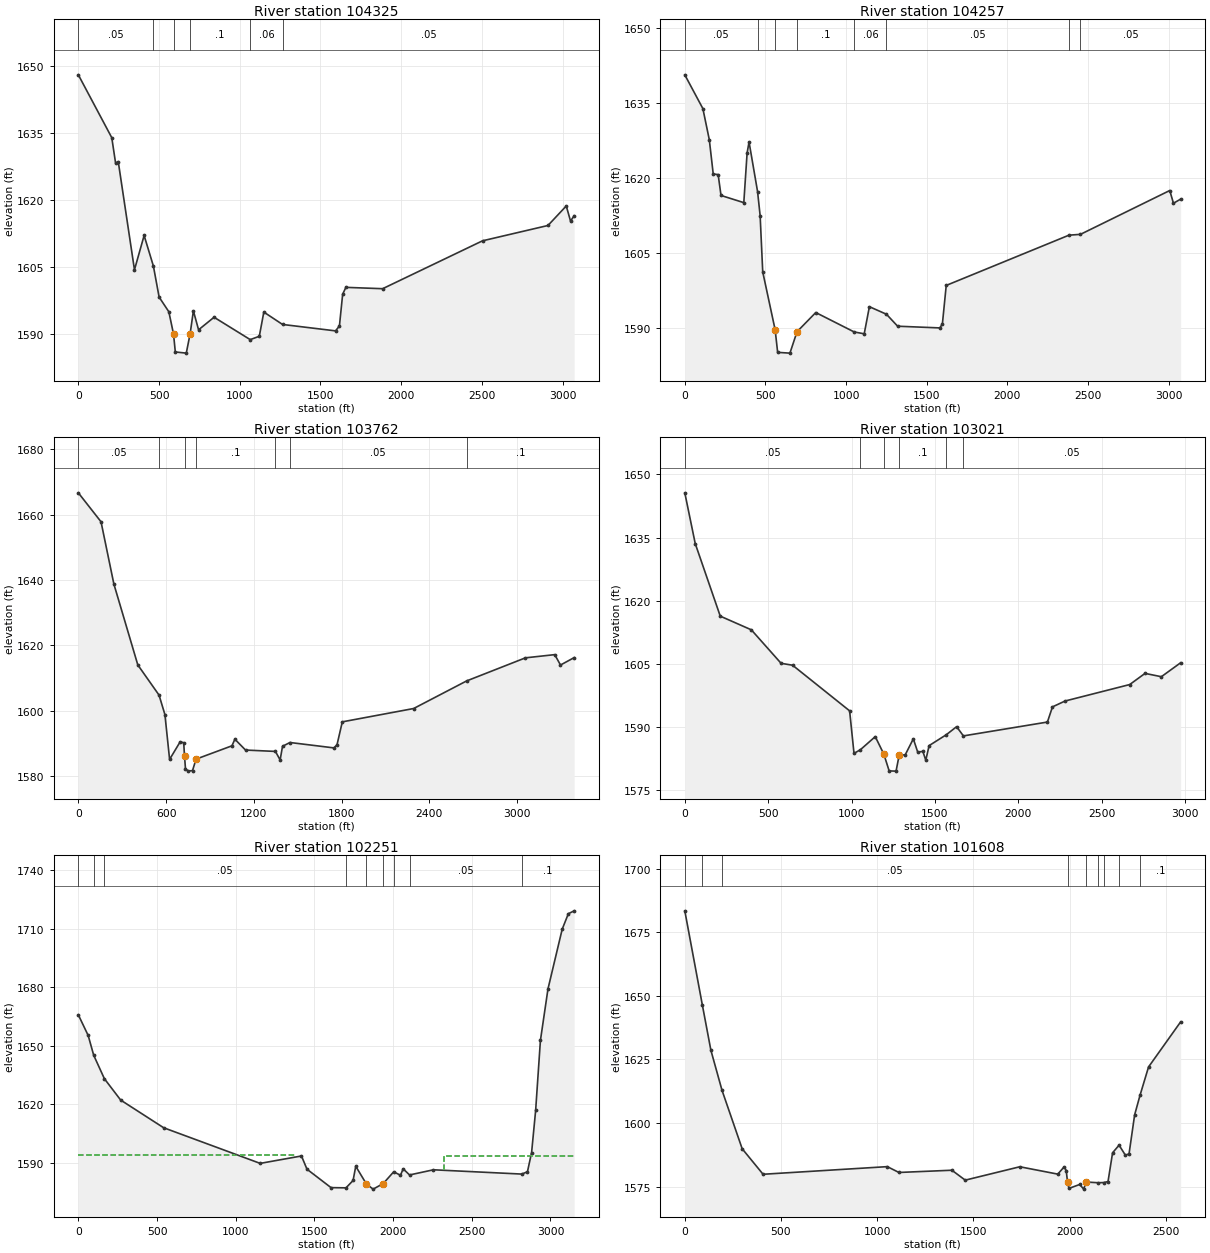
Type RM Length L Ch R = 1 ,104325  ,68.9,67.9,71.6
XS GIS Cut Line= 4
2467928.52951998 592917.145181762468481.30729777592864.367403984
 2469692.4184089 592817.145181762470850.75174224592217.145181775
#Sta/Elev= 30
       0 1647.94   207.2 1633.87     231 1628.13   247.3 1628.52   347.8  1604.3
   407.6 1611.98  465.131605.123   500.5 1598.19   560.7 1594.91  589.761589.922
   600.8 1585.91   668.8 1585.65   692.8 1590.02   712.8 1595.11   744.9 1590.87
   840.9 1593.68    10651588.671  1121.2 1589.42  1149.2 1594.84 1265.111592.068
  1593.5 1590.63  1617.6 1591.73  1637.6 1598.83  1657.6 1600.37  1885.3 1600.07
  2504.2 1610.79  2909.6 1614.22    3023 1618.59  3049.3 1615.213071.829  1616.4
#Mann= 6 ,-1 , 0
       0     .05       0  465.13      .1       0  589.76    .045       0
   692.8      .1       0    1065     .06       0 1265.11     .05       0
#XS Ineff= 2 , 0
             569 1590.15     712         1590.15
Permanent Ineff=
       F       F
Bank Sta=589.76,692.8
XS Rating Curve= 0 ,0
Exp/Cntr(USF)=0,0
Exp/Cntr=0.5,0.3

Type RM Length L Ch R = 1 ,104257  ,495.2,495.2,492.7
XS GIS Cut Line= 4
 2467956.3072978593006.0340706412468470.19618669592933.811848417
2469689.64063111592872.7007373272470861.86285332592236.589626208
#Sta/Elev= 30
       0 1640.72     112 1633.96   151.9 1627.73   176.2 1620.87   206.8 1620.73
   224.5 1616.56   365.8 1615.12   386.2 1625.05   398.3 1627.27  451.041617.347
     467 1612.52   483.1 1601.25  559.891589.678   575.6 1585.13   651.7 1584.98
   695.7 1589.27   811.9 1593.11  1050.21589.217  1112.2 1588.85  1144.3 1594.28
 1250.061592.768  1319.4 1590.37  1580.8 1590.03  1596.8 1590.82  1620.6 1598.54
  2381.51608.604 2452.77 1608.77  3006.3 1617.55  3029.1    16153073.609 1615.82
#Mann= 8 ,-1 , 0
       0     .05       0  451.04      .1       0  559.89    .045       0
   695.7      .1       0  1050.2     .06       0 1250.06     .05       0
  2381.5      .1       0 2452.77     .05       0
Bank Sta=559.89,695.7
XS Rating Curve= 0 ,0
Exp/Cntr(USF)=0,0
Exp/Cntr=0.5,0.3

Type RM Length L Ch R = 1 ,103762  ,743.1,740.7,717.6
XS GIS Cut Line= 4
2467831.59120551593437.7112139462468296.35166818593448.865465045
2469415.49486229593333.6048703042470870.19618669592272.700737312
#Sta/Elev= 30
       0 1666.65   155.2 1657.79   243.2 1638.71   406.7 1613.98  551.891604.745
     592  1598.8   624.1 1585.07   696.5 1590.47   720.6 1590.16  726.12 1586.03
   732.7  1582.2   752.3 1581.48     781 1581.67   805.1 1585.15  1050.4 1589.23
  1070.4 1591.25  1143.3 1587.93 1347.771587.511  1379.9  1584.9  1396.2 1589.08
 1447.261590.241  1747.5 1588.59  1768.9 1589.55    1805 1596.56  2292.8 1600.64
 2655.191609.085  3057.2 1616.15  3257.6 1617.13    3297 1613.953390.422 1616.22
#Mann= 7 ,-1 , 0
       0     .05       0  551.89      .1       0  726.12    .045       0
   805.1      .1       0 1347.77     .06       0 1447.26     .05       0
 2655.19      .1       0
Bank Sta=726.12,805.1
XS Rating Curve= 0 ,0
Exp/Cntr(USF)=0,0
Exp/Cntr=0.3,0.1

Type RM Length L Ch R = 1 ,103021  ,762.5,769.9,772.4
XS GIS Cut Line= 4
2467760.94761521594304.0247163772468716.49512643594147.865200922
 2469586.5267126593753.7483285522470139.64063114592861.589626193
#Sta/Elev= 30
       0 1645.63    62.6 1633.58   212.6 1616.36     399 1613.11   577.4 1605.16
   646.3 1604.71   988.3 1593.88  1014.6 1583.78 1053.111584.658    1142 1587.76
  1193.5  1583.6  1225.4 1579.62  1266.8 1579.57    1285 1583.28    1322 1583.46
  1370.3 1587.24  1396.6 1584.09  1427.4 1584.25    1445 1582.17    1465 1585.63
  1567.61588.197  1629.8 1590.12  1670.51587.931  2174.3 1591.22  2204.6 1594.82
    2280 1596.21  2667.7 1600.12  2759.7 1602.77  2857.5 1601.982973.064 1605.29
#Mann= 6 ,-1 , 0
       0     .05       0 1053.11      .1       0  1193.5    .045       0
    1285      .1       0  1567.6     .06       0  1670.5     .05       0
Bank Sta=1193.5,1285
XS Rating Curve= 0 ,0
Exp/Cntr(USF)=0,0
Exp/Cntr=0.3,0.1

Type RM Length L Ch R = 1 ,102251  ,653.7,643.1,630.9
XS GIS Cut Line= 4
2467541.58067679  595456.63066382468872.65464189594869.173438978
2469564.21821035594623.7799146852470452.84021499594255.689628245
#Sta/Elev= 30
       0  1665.9    62.5 1655.33   97.681645.169  165.411633.157   269.1 1622.17
   542.2 1607.97  1155.5 1589.69  1417.9 1593.49  1452.9  1586.7  1605.7 1577.25
  1700.81577.138  1745.8 1580.91  1762.8 1588.21  1830.7 1579.08  1873.1 1576.48
 1936.97  1579.3 2003.661585.341  2047.1 1583.62  2064.1  1586.9 2104.611583.754
  2256.4  1586.4 2818.041584.204  2853.9 1585.41  2880.2 1595.26  2905.9 1616.88
  2936.2 1652.76  2984.3 1679.22  3074.7 1709.87  3113.7 1717.78  3150.6 1719.27
#Mann= 9 ,-1 , 0
       0     .05       0   97.68     .12       0  165.41     .05       0
  1700.8      .1       0  1830.7    .045       0 1936.97      .1       0
 2003.66     .06       0 2104.61     .05       0 2818.04      .1       0
#XS Ineff= 2 , 0
         1376.03 1593.95  2323.2         1593.67
Permanent Ineff=
       F       F
Bank Sta=1830.7,1936.97
XS Rating Curve= 0 ,0
Exp/Cntr(USF)=0,0
Exp/Cntr=0.3,0.1

Type RM Length L Ch R = 1 ,101608  ,546.8,573.8,600.2
XS GIS Cut Line= 4
2467712.61252705596070.1144745322469348.56935567595419.449826786
2469802.17556724595129.4392980762470032.69675673594973.279782617
#Sta/Elev= 30
       0 1683.44   91.59 1646.28   135.7  1628.6   193.31612.925   298.2 1589.92
   406.9 1579.88  1052.7 1582.88  1113.1 1580.59  1388.4 1581.47  1457.8 1577.57
  1741.4 1582.83  1938.8 1579.94  1972.1 1582.81  1982.7 1581.35  1989.7 1576.72
  1997.2 1574.33  2052.8 1575.87  2073.5 1574.04    2086 1576.83 2149.271576.552
 2178.19 1576.63    2200 1577.01  2223.7 1588.32 2257.471591.323  2290.2 1587.39
  2309.3 1587.91  2338.3 1603.22 2366.471610.957  2410.7 1622.07  2577.4 1639.78
#Mann= 9 ,-1 , 0
       0     .12       0   91.59      .1       0   193.3     .05       0
  1989.7    .045       0    2086      .1       0 2149.27    .055       0
 2178.19     .06       0 2257.47      .1       0 2366.47      .1       0
Bank Sta=1989.7,2086
XS Rating Curve= 0 ,0
Exp/Cntr(USF)=0,0
Exp/Cntr=0.3,0.1

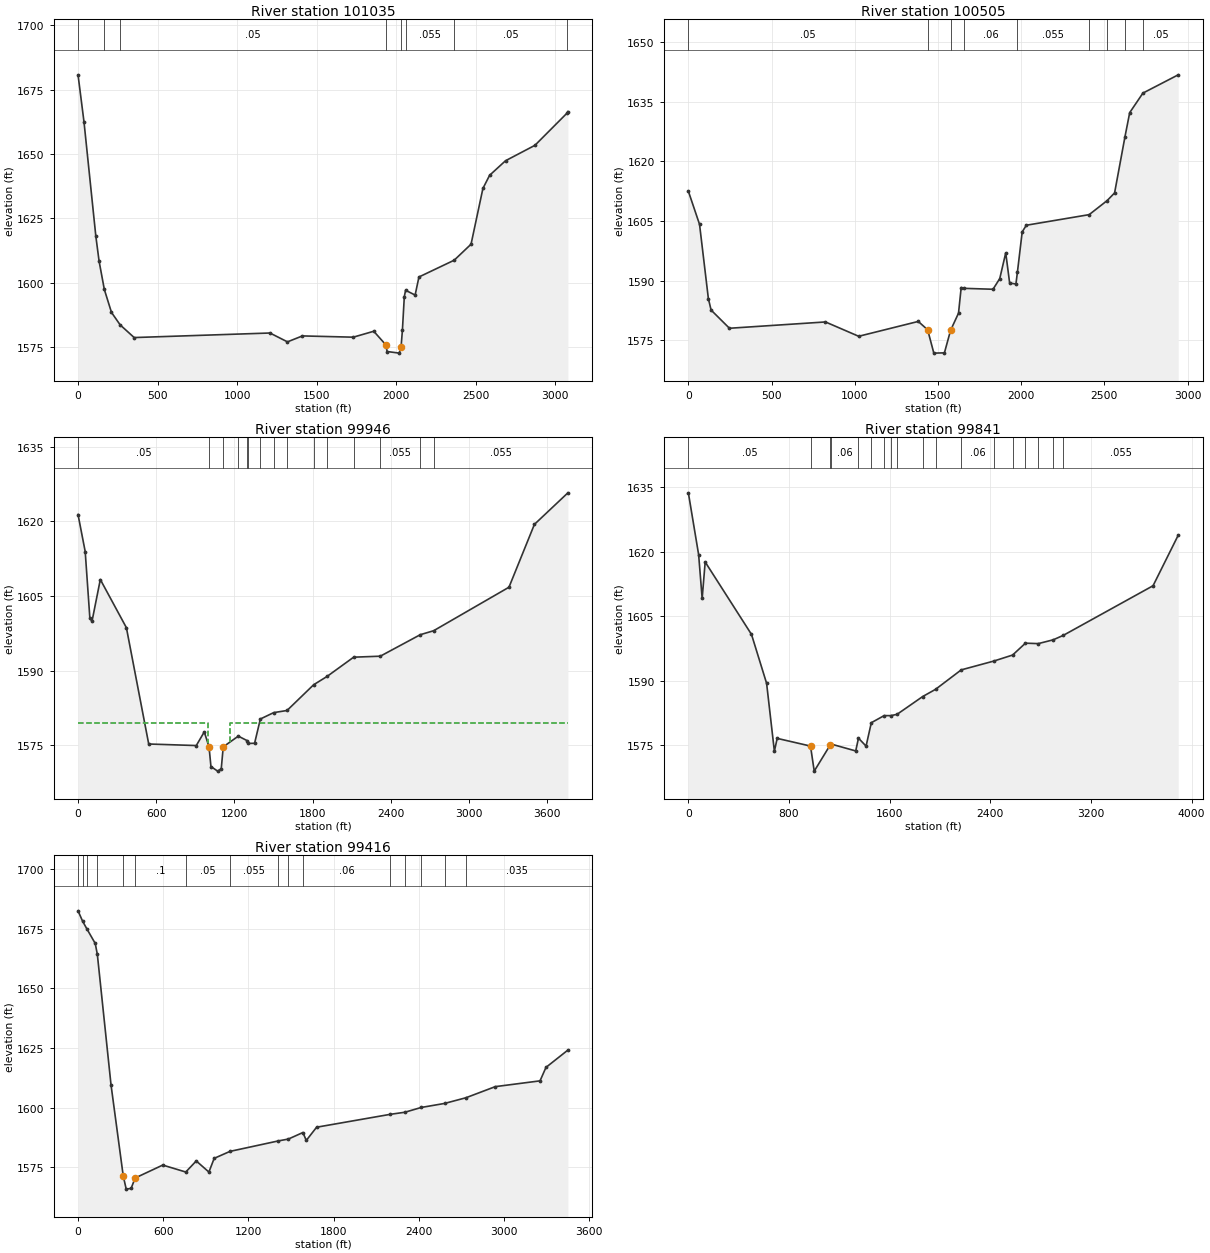
Type RM Length L Ch R = 1 ,101035  ,530.7,529.4,532.4
XS GIS Cut Line= 4
2467753.51144777596174.2208181722469471.26611782595794.976280628
2469936.02658049595794.9762806282470709.38799039 595430.60407789
#Sta/Elev= 30
       0 1680.77    37.4 1662.51   111.9 1618.02   132.3 1608.35  165.291597.339
   210.2 1588.42  264.771583.569   352.8 1578.64  1206.3 1580.41  1316.2 1576.97
  1410.4 1579.28  1729.9 1578.79  1858.6 1581.09  1934.5 1575.81  1942.6 1573.22
  2018.6 1572.59  2030.5 1575.16  2038.7  1581.5  2050.6 1594.54 2058.711597.028
  2118.6 1595.16  2142.6 1602.19 2364.241608.713  2470.1 1614.93  2544.6 1636.59
  2586.7 1641.71  2686.7 1647.37  2871.6 1653.37 3071.721665.786  3078.8 1666.48
#Mann= 8 ,-1 , 0
       0      .1       0  165.29      .1       0  264.77     .05       0
  1934.5    .045       0  2030.5      .1       0 2058.71    .055       0
 2364.24     .05       0 3071.72     .06       0
Bank Sta=1934.5,2030.5
XS Rating Curve= 0 ,0
Exp/Cntr(USF)=0,0
Exp/Cntr=0.3,0.1

Type RM Length L Ch R = 1 ,100505  ,544.1,559.1,580.5
XS GIS Cut Line= 4
2468024.93155797 596538.593020912469341.13318827596267.172910707
2469724.09580951596315.507998825 2470754.0049948595672.279518482
#Sta/Elev= 30
       0 1612.52    67.2 1604.17   120.3 1585.47   136.7 1582.59   246.9 1578.01
   824.1  1579.6  1023.8 1575.99  1381.8 1579.73  1438.3 1577.62  1475.3 1571.75
    1539 1571.82 1575.961577.481  1623.7 1581.81  1639.8 1588.27 1657.791588.062
    1831 1587.83  1871.6 1590.52  1907.5    1597  1931.1 1589.38  1968.8 1589.17
 1978.021592.231  2006.5 1602.28  2031.3 1603.95 2408.891606.617  2516.61610.139
  2561.7 1612.08 2624.321626.268  2652.6  1632.3 2732.03 1637.22  2944.2 1641.82
#Mann= 9 ,-1 , 0
       0     .05       0  1438.3    .045       0 1575.96      .1       0
 1657.79     .06       0 1978.02    .055       0 2408.89     .06       0
  2516.6    .055       0 2624.32     .06       0 2732.03     .05       0
Bank Sta=1438.3,1575.96
XS Rating Curve= 0 ,0
Exp/Cntr(USF)=0,0
Exp/Cntr=0.5,0.3

Type RM Length L Ch R = 1 ,99946   ,102,105.2,100.2
XS GIS Cut Line= 5
2468159.77952001596753.9507373122469107.69618666596726.172959536
2469395.89063111596833.811848432 2470799.5842219 596237.81795603
2471437.23901072595496.022496581
#Sta/Elev= 30
       0 1621.38      55 1613.95    90.6 1600.64     107 1599.91     171 1608.33
   371.1 1598.65   542.4 1575.27   907.4 1574.96   968.7  1577.7 1005.231574.707
  1019.9 1570.75  1071.1 1569.82    1099 1570.29 1114.371574.706 1230.091576.853
 1296.951575.955 1307.651575.382  1354.9 1575.42 1399.221580.299 1501.491581.578
 1603.751582.006 1808.281587.184 1910.551588.841 2115.081592.719 2319.611592.919
 2626.411597.238 2728.681598.034    3307 1606.78  3502.2 1619.413759.138 1625.75
#Mann= 15 ,-1 , 0
       0     .05       0 1005.23    .045       0 1114.37    .055       0
 1230.09     .06       0 1296.95      .1       0 1307.65     .06       0
 1399.22     .05       0 1501.49     .06       0 1603.75     .05       0
 1808.28     .06       0 1910.55    .055       0 2115.08     .06       0
 2319.61    .055       0 2626.41    .035       0 2728.68    .055       0
#XS Ineff= 2 , 0
             995 1579.44    1164         1579.44
Permanent Ineff=
       F       F
Bank Sta=1005.23,1114.37
XS Rating Curve= 0 ,0
Exp/Cntr(USF)=0,0
Exp/Cntr=0.5,0.3

Type RM Length L Ch R = 1 ,99841   ,454,424.4,382.1
XS GIS Cut Line= 5
 2468125.0572978596816.450737327 2469031.3072978596795.617403984
2469333.39063111596920.6174039842470795.57234406596312.689163238
2471517.91030702595514.613353059
#Sta/Elev= 30
       0 1633.67    81.7  1619.3   109.7 1609.12   133.7  1617.6   501.8 1600.77
   621.9  1589.4   683.7 1573.62   705.9 1576.61   970.8 1574.82  1000.4    1569
    1126 1575.01  1135.61575.282  1330.2 1573.69 1352.031576.658  1412.5 1574.81
 1454.111580.249 1556.191581.902 1607.251581.892 1658.271582.188 1862.431586.333
 1964.511588.004 2168.681592.526 2427.991594.579    25771595.974 2679.081598.733
 2781.161598.631 2899.531599.512 2979.911600.547  3693.4 1612.08  3893.4 1623.82
#Mann= 18 ,-1 , 0
       0     .05       0   970.8    .045       0    1126      .1       0
  1135.6     .06       0 1352.03      .1       0 1454.11     .05       0
 1556.19    .055       0 1607.25     .06       0 1658.27     .05       0
 1862.43     .06       0 1964.51    .055       0 2168.68     .06       0
 2427.99    .055       0    2577     .06       0 2679.08    .035       0
 2781.16    .055       0 2899.53     .06       0 2979.91    .055       0
Bank Sta=970.8,1126
XS Rating Curve= 0 ,0
Exp/Cntr(USF)=0,0
Exp/Cntr=0.53,0.3

Type RM Length L Ch R = 1 ,99416   ,411.6,410.9,410
XS GIS Cut Line= 5
2468683.03237316597345.4171841292468909.83547893597233.874673083
2469702.74827001596845.0965706562470823.07419831596351.703345045
2471530.93114036595521.557797506
#Sta/Elev= 30
       0 1682.57   32.241678.209   62.651674.956   121.2 1668.88  136.081664.257
   232.3 1609.61   318.4 1571.37   339.4 1565.83     374 1566.14   402.1 1570.49
   596.8 1575.92  758.951573.006   832.9 1577.65     922 1572.99   959.1 1578.74
 1070.37 1581.66 1410.841586.051 1481.56 1586.83 1584.181589.573  1607.9 1586.25
  1680.7  1591.8 2199.841597.207 2302.451598.079 2417.221600.079 2582.881601.784
 2732.391604.154  2939.3 1608.82  3254.7 1611.25  3296.6  1616.9    3451 1624.16
#Mann= 16 ,-1 , 0
       0      .1       0   32.24      .1       0   62.65      .1       0
  136.08      .1       0   318.4    .045       0   402.1      .1       0
  758.95     .05       0 1070.37    .055       0 1410.84     .06       0
 1481.56    .055       0 1584.18     .06       0 2199.84    .035       0
 2302.45    .055       0 2417.22     .06       0 2582.88    .055       0
 2732.39    .035       0
Bank Sta=318.4,402.1
XS Rating Curve= 0 ,0
Exp/Cntr(USF)=0,0
Exp/Cntr=0.3,0.1