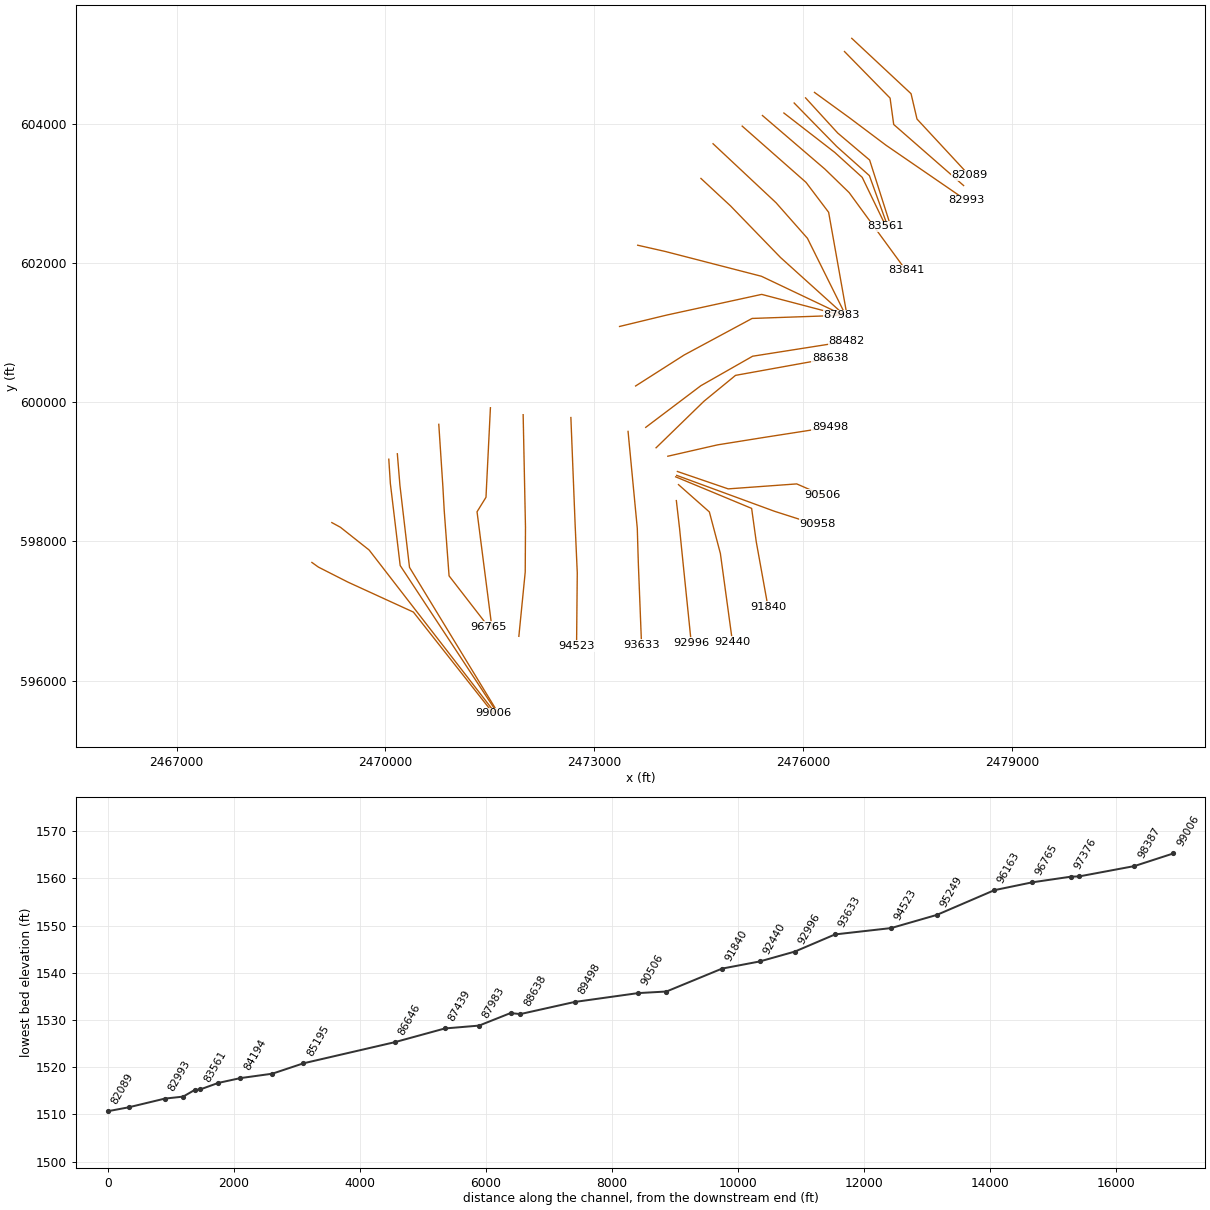
HEC-RAS study SFSBPOTOMC.prj: SFSBPOTOMC

--- SFSBPOTOMC.g01 (geometry) --- (continued)

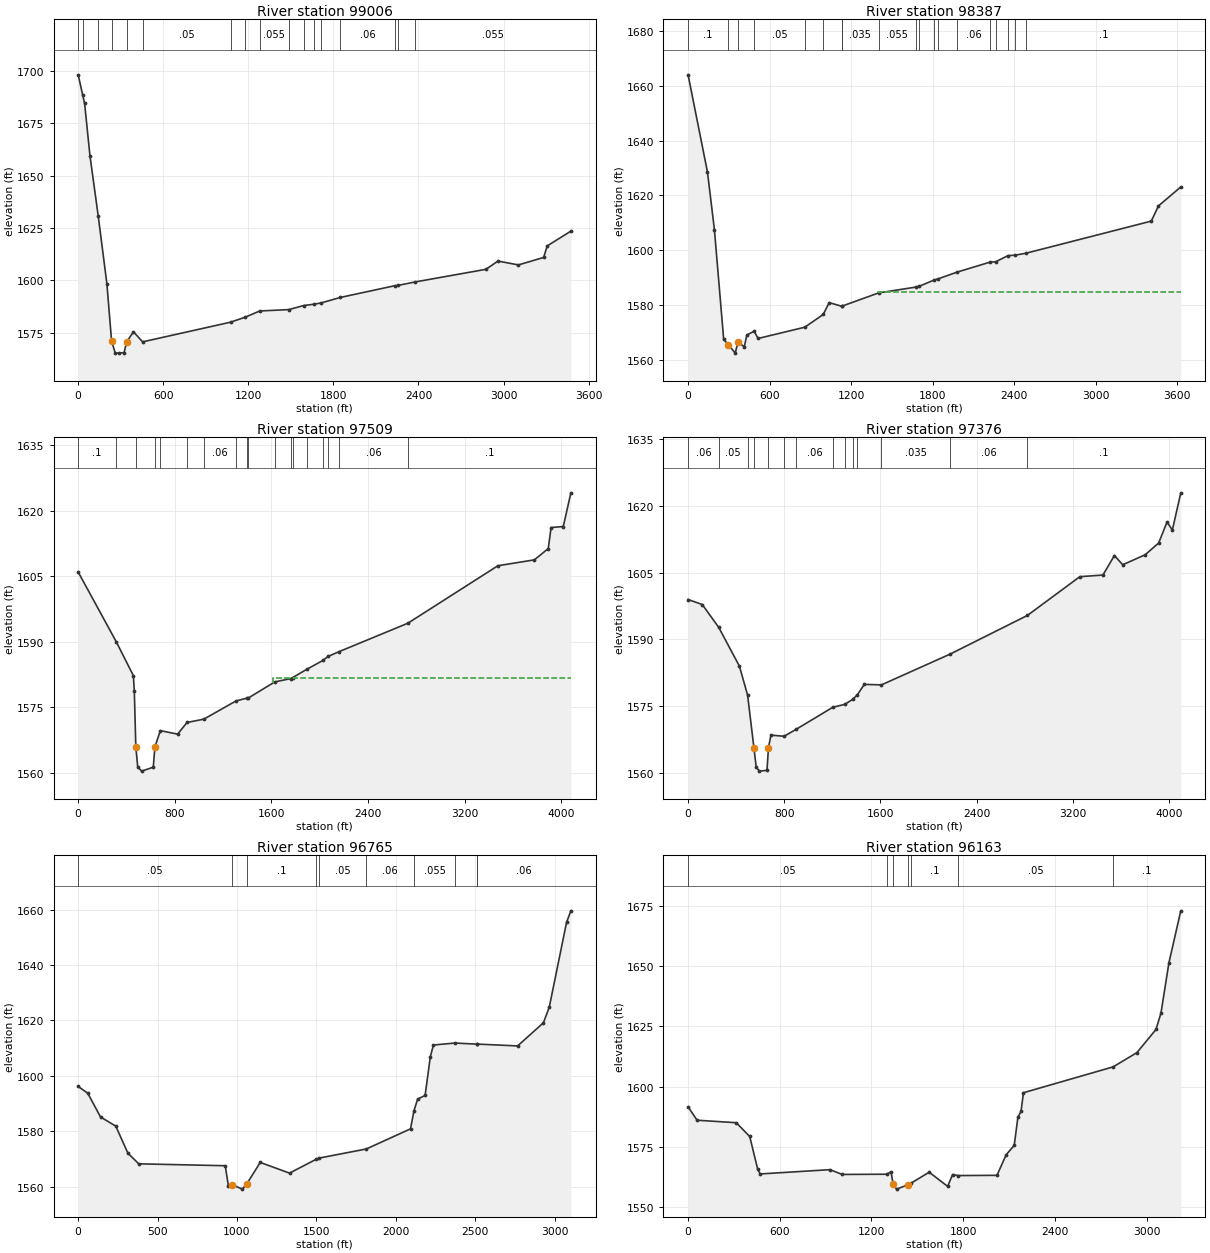
Type RM Length L Ch R = 1 ,99006   ,625.9,618.6,608.6
XS GIS Cut Line= 5
2468943.29823223 597698.635135772469036.25032479597631.709629133
2469460.11186674 597416.060774462470401.12789965596984.911385477
2471545.68808484595531.974464178
#Sta/Elev= 30
       0 1698.12   32.52 1688.31    45.3 1684.48    83.1 1659.53  141.781630.534
   202.6 1598.34  235.611571.044     261 1565.39   287.9 1565.28   323.8 1565.54
   341.7 1570.56   389.8 1575.46  454.631570.661 1074.381580.045  1177.41582.414
 1280.421585.397 1486.45 1586.06 1589.471587.981 1659.881588.603 1713.281589.231
 1848.111591.845 2232.521597.455 2252.631597.562 2375.681599.246  2875.4 1605.28
  2960.8 1609.22  3104.5 1607.39  3282.7 1610.94  3308.1 1616.46  3474.8 1623.51
#Mann= 17 ,-1 , 0
       0      .1       0   32.52      .1       0  141.78      .1       0
  235.61    .045       0   341.7      .1       0  454.63     .05       0
 1074.38    .055       0  1177.4     .06       0 1280.42    .055       0
 1486.45    .035       0 1589.47    .055       0 1659.88    .035       0
 1713.28    .055       0 1848.11     .06       0 2232.52    .055       0
 2252.63     .06       0 2375.68    .055       0
Bank Sta=235.61,341.7
XS Rating Curve= 0 ,0
Exp/Cntr(USF)=0,0
Exp/Cntr=0.3,0.1

Type RM Length L Ch R = 1 ,98387   ,906.2,877.8,783.6
XS GIS Cut Line= 4
2469229.59067726598271.2200257782469352.28743941598204.294519156
2469764.99473023597877.1031534372471575.20197374595535.446686402
#Sta/Elev= 30
       0 1663.91   142.9 1628.44   193.8 1607.55   262.1 1567.58   296.6 1565.68
   347.1  1562.6   367.4 1566.69   413.4 1564.89   432.9 1569.21  485.941570.581
   515.5 1567.94  858.661572.031  994.641576.669  1038.3 1580.99 1130.621579.665
 1131.571579.681 1402.591584.522 1674.561586.628 1698.651586.891 1810.541589.193
 1840.421589.642 1982.191592.125  2218.51595.666 2265.741595.896 2354.481598.104
 2407.511598.254 2490.461599.013  3409.1 1610.66  3461.9 1616.19  3626.2 1623.09
#Mann= 19 ,-1 , 0
       0      .1       0   296.6    .045       0   367.4      .1       0
  485.94     .05       0  858.66     .06       0  994.64    .055       0
 1130.62     .02       0 1131.57    .035       0 1402.59    .055       0
 1674.56     .06       0 1698.65    .055       0 1810.54     .06       0
 1840.42    .055       0 1982.19     .06       0  2218.5      .1       0
 2265.74     .06       0 2354.48      .1       0 2407.51     .06       0
 2490.46      .1       0
#XS Ineff= 2 , 0
                         1397.26          1584.8
Permanent Ineff=
       F       F
Bank Sta=296.6,367.4
XS Rating Curve= 0 ,0
Exp/Cntr(USF)=0,0
Exp/Cntr=0.5,0.3

Type RM Length L Ch R = 1 ,97509   ,133.1,132.8,135.8
XS GIS Cut Line= 4
2470047.56909156599182.1505326032470069.87759379598836.368748397
2470211.16477439597654.0181313312471609.05614039595530.238353044
#Sta/Elev= 30
       0 1605.97  315.021590.031   456.8 1582.27   464.8  1578.8  477.351565.947
     493 1561.39   525.2 1560.41   621.9 1561.31  635.131565.946  680.821569.678
   823.3 1568.87  901.481571.542 1040.611572.302 1306.611576.465 1400.391577.137
 1407.891577.126 1628.231580.826 1763.981581.604 1775.061581.799  1895.6 1583.75
 2027.211585.746 2068.721586.648 2158.821587.734  2729.7 1594.25  3475.6 1607.41
  3777.4 1608.75  3892.3 1611.33  3916.2 1616.15  4016.8 1616.38  4079.8 1624.09
#Mann= 18 ,-1 , 0
       0      .1       0  315.02    .055       0  477.35    .045       0
  635.13      .1       0  680.82     .06       0  901.48     .05       0
 1040.61     .06       0 1306.61     .05       0 1400.39    .055       0
 1407.89     .06       0 1628.23    .035       0 1763.98    .055       0
 1775.06    .035       0  1895.6    .055       0 2027.21     .06       0
 2068.72    .055       0 2158.82     .06       0  2729.7      .1       0
#XS Ineff= 2 , 0
             437  1581.2 1609.59          1581.7
Permanent Ineff=
       F       F
Bank Sta=477.35,635.13
XS Rating Curve= 0 ,0
Exp/Cntr(USF)=0,0
Exp/Cntr=0.5,0.3

Type RM Length L Ch R = 1 ,97376   ,613.3,611.8,603.8
XS GIS Cut Line= 4
2470170.26585367599260.2302903382470207.44669071598806.624078766
2470345.01578766597627.9915454392471621.67188114595529.471570641
#Sta/Elev= 30
       0 1598.95   117.7 1597.83  254.131592.723   426.8 1583.97  495.081577.436
  547.861565.554     566 1561.38   591.8 1560.35   656.2 1560.53  668.581565.553
   688.7 1568.45  798.691568.188  899.891569.769 1203.51 1574.71 1304.711575.379
 1368.351576.493 1405.921577.444  1465.7 1579.86 1608.331579.751  2181.5  1586.7
  2822.8 1595.38  3258.4 1604.09  3450.3 1604.45    3546 1608.84  3615.3 1606.77
  3801.5 1609.01  3913.8 1611.65  3984.1 1616.38    4028 1614.57  4098.1 1622.95
#Mann= 14 ,-1 , 0
       0     .06       0  254.13     .05       0  495.08    .055       0
  547.86    .045       0  668.58      .1       0  798.69    .055       0
  899.89     .06       0 1203.51      .1       0 1304.71    .055       0
 1368.35     .06       0 1405.92    .055       0 1608.33    .035       0
  2181.5     .06       0  2822.8      .1       0
Bank Sta=547.86,668.58
XS Rating Curve= 0 ,0
Exp/Cntr(USF)=0,0
Exp/Cntr=0.5,0.3

Type RM Length L Ch R = 1 ,96765   ,623.7,602,560.2
XS GIS Cut Line= 5
2470765.57321422599683.2588167962470824.44965887598786.083260477
2470843.89410332598438.8610382532470913.33854777597505.527704909
2471476.52812862596777.601649423
#Sta/Elev= 30
       01596.205  60.4981593.747  140.671585.186 236.8761581.885  313.041572.146
 381.1861568.285  926.34  1567.6 946.3721560.164 970.4091560.708 1034.511559.156
1062.5531561.0931146.6851568.7881331.0741564.928 1500.921569.981 1514.211570.321
  1814.61573.6372093.1751580.901 2114.981587.4332138.0261591.6482185.0831592.957
2217.7671606.8592237.3771611.148 2373.261611.857  2509.21611.467 2512.251611.485
2767.7231610.8212930.2731619.1692966.939 1624.783076.2261655.4663103.1431659.559
#Mann= 10 ,-1 , 0
       0     .05       0 970.409    .045       01062.553      .1       0
 1500.92     .06       0 1514.21     .05       0  1814.6     .06       0
 2114.98    .055       0 2373.26     .06       0  2509.2     .05       0
 2512.25     .06       0
Bank Sta=970.409,1062.553
XS Rating Curve= 0 ,0
Exp/Cntr(USF)=0,0
Exp/Cntr=0.3,0.1

Type RM Length L Ch R = 1 ,96163   ,860.6,913.5,923
XS GIS Cut Line= 4
2471507.14971402599921.7937069422471443.37326998598634.833260477
2471314.90104777598426.4999271182471530.17882556596750.072129257
#Sta/Elev= 30
       01591.606  58.9751586.054 315.2891585.031 403.3971579.309 455.4611565.735
 471.4811563.783  928.041565.5631008.1381563.582 1300.71 1563.67 1327.84 1564.71
1341.2781559.6011363.6631557.4911438.8531559.286 1457.731559.9151577.2681564.514
1698.2531558.6381730.5161563.544  1765.4 1563.112020.8811563.2142081.3741571.771
2133.8011575.6152157.9981587.3672178.1621589.6842194.2931597.458 2780.751608.169
2936.3371614.0713061.3551623.6963093.6181630.3873146.0451651.3663223.4941672.866
#Mann= 7 ,-1 , 0
       0     .05       0 1300.71      .1       01341.278    .045       0
1438.853     .05       0 1457.73      .1       0  1765.4     .05       0
 2780.75      .1       0
Bank Sta=1341.278,1438.853
XS Rating Curve= 0 ,0
Exp/Cntr(USF)=0,0
Exp/Cntr=0.3,0.1

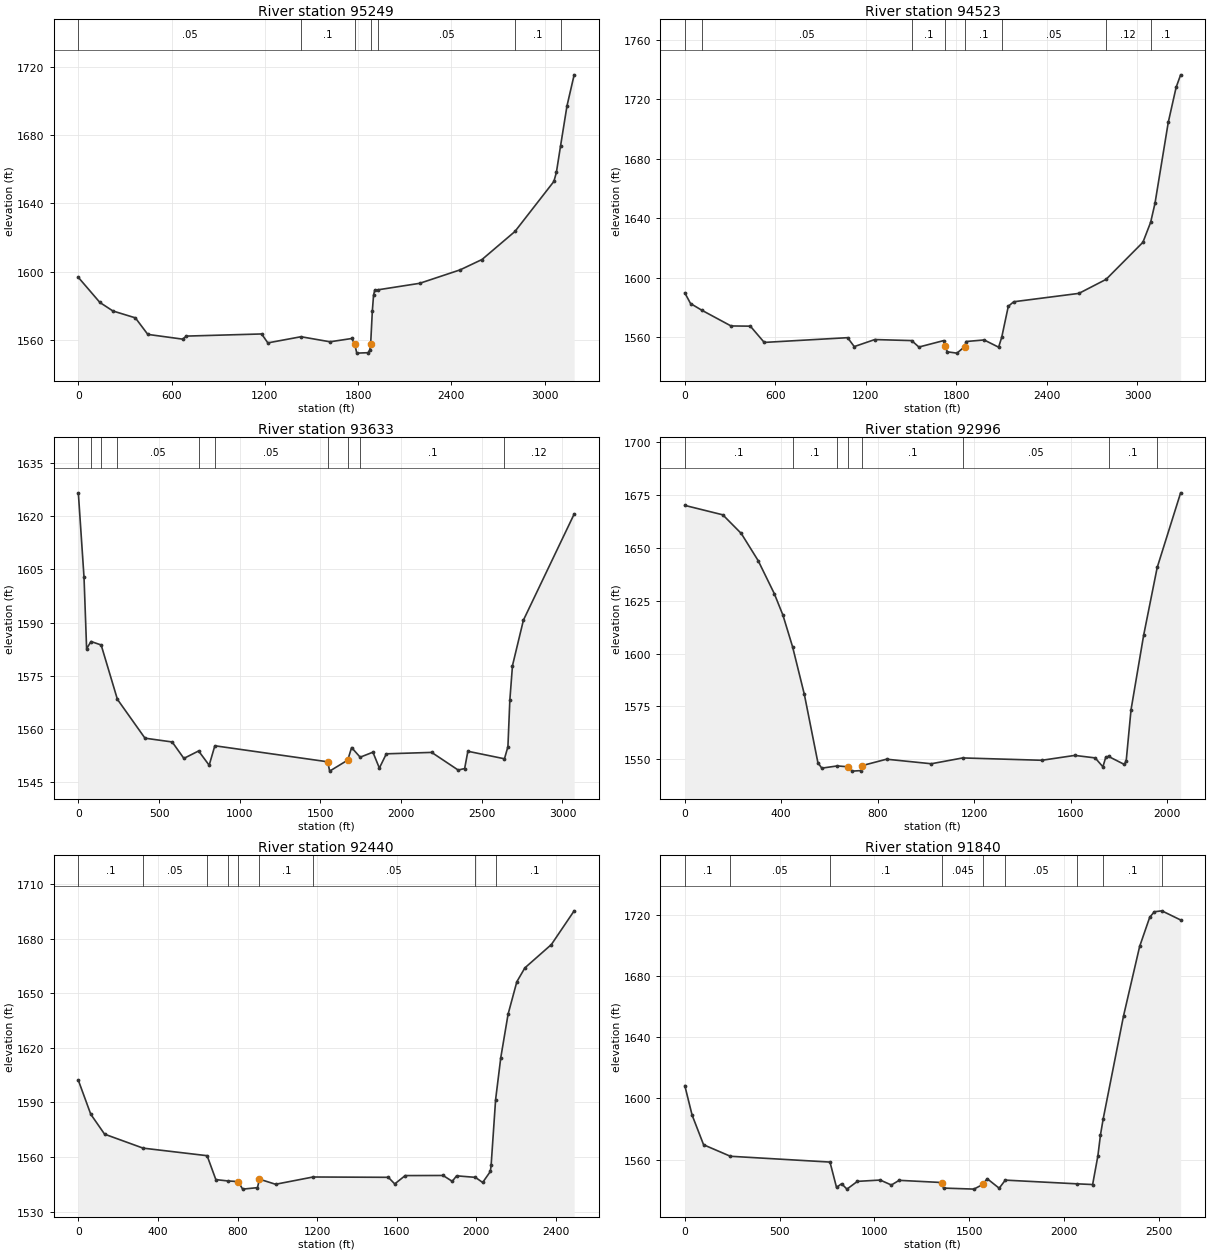
Type RM Length L Ch R = 1 ,95249   ,722.4,725.8,729.5
XS GIS Cut Line= 4
2471977.25453256599821.6609292532472010.71728588598200.576435439
2472006.99920218597561.0660387972471915.57106587596637.051346838
#Sta/Elev= 30
       01596.644   138.81581.928 222.8181576.938 366.848 1572.92 446.8651563.225
 670.9131560.449 694.918 1562.231179.0211563.483 1219.03 1558.25 1432.43 1561.86
1619.1151558.8871759.1181560.828 1778.151557.4351791.118 1552.25 1863.12  1552.5
 1875.121554.012 1880.341557.457 1891.12  1576.8 1899.121586.274 1907.121589.227
 1926.311589.3342195.7581593.1622456.0741601.0472596.7581607.112 2808.611623.539
3059.0041652.8543075.0831658.117 3101.651673.4873143.415 1697.153189.4781715.332
#Mann= 7 ,-1 , 0
       0     .05       0 1432.43      .1       0 1778.15    .045       0
 1880.34      .1       0 1926.31     .05       0 2808.61      .1       0
 3101.65      .1       0
Bank Sta=1778.15,1880.34
XS Rating Curve= 0 ,0
Exp/Cntr(USF)=0,0
Exp/Cntr=0.3,0.1

Type RM Length L Ch R = 1 ,94523   ,890.3,889.8,888.2
XS GIS Cut Line= 4
2472662.62639511599780.909915845  2472723.829419598240.633814576
2472754.43093095597546.9995438062472744.23042696596497.016788383
#Sta/Elev= 30
       01589.957  38.0491582.773  112.191578.308 306.2611567.718 434.3621567.576
 526.4341556.656 1078.871559.8441122.9041553.8511259.0121558.579 1503.671557.884
1551.2441553.5461715.4041557.883 1725.271554.4591739.4271550.3361803.4891549.464
  1855.51553.8741863.5471557.2531983.6641558.3172079.7581553.451  2100.51560.214
 2143.821580.9212179.8551583.9692611.9271589.593 2791.641598.9953035.9471623.914
 3087.31 1637.373115.951 1650.093203.9551704.4823255.9571727.9513285.833 1736.38
#Mann= 8 ,-1 , 0
       0     .06       0  112.19     .05       0 1503.67      .1       0
 1725.27    .045       0  1855.5      .1       0  2100.5     .05       0
 2791.64     .12       0 3087.31      .1       0
Bank Sta=1725.27,1855.5
XS Rating Curve= 0 ,0
Exp/Cntr(USF)=0,0
Exp/Cntr=0.3,0.1

Type RM Length L Ch R = 1 ,93633   ,645.7,637,637.1
XS GIS Cut Line= 4
2473483.76696565599582.0000881982473616.37351742598189.631294666
2473631.67427339597679.6060955712473677.57654131596516.748641632
#Sta/Elev= 30
       0 1626.58    35.3 1602.72    51.3 1582.62   78.521584.665  141.441583.686
  242.071568.368     413 1557.41   581.6 1556.34   654.1 1551.71  745.251553.803
   810.8 1549.78  845.891555.269  1545.5 1550.75  1557.5 1548.12  1669.5 1551.23
  1693.5 1554.76  1746.61552.047  1825.6 1553.46  1865.6 1548.98  1908.7    1553
  2189.8  1553.4    2354 1548.42    2394 1548.85    2414 1553.72 2640.78  1551.6
  2662.2    1555  2674.2 1568.19  2690.5 1577.87  2758.3 1590.69  3072.7 1620.59
#Mann= 10 ,-1 , 0
       0    .055       0   78.52    .035       0  141.44    .055       0
  242.07     .05       0  745.25      .1       0  845.89     .05       0
  1545.5    .045       0  1669.5    .025       0  1746.6      .1       0
 2640.78     .12       0
Bank Sta=1545.5,1669.5
XS Rating Curve= 0 ,0
Exp/Cntr(USF)=0,0
Exp/Cntr=0.3,0.1

Type RM Length L Ch R = 1 ,92996   ,566.4,556.7,558.1
XS GIS Cut Line= 4
2474177.40123642598587.4509499612474223.30350434598189.631294666
2474289.60678022597536.7990398242474391.61182004596542.249901587
#Sta/Elev= 30
       0  1669.9   157.6 1665.45   234.1 1656.66   304.1 1643.86     371 1628.31
   407.2 1618.04  447.021603.161   495.7 1580.76   552.1 1548.45   568.1  1545.9
  632.821546.948   676.2 1546.54     695 1544.49   728.9 1544.74   734.6 1547.07
   836.8 1550.12  1022.4 1547.97 1152.631550.716  1480.8 1549.61  1617.4 1551.91
  1701.9 1550.73  1734.1 1546.53  1746.2 1551.18 1757.57 1551.42  1822.6 1547.66
  1830.6 1549.26  1850.7 1573.44    1903 1608.59 1959.22 1640.59  2056.4 1675.83
#Mann= 8 ,-1 , 0
       0      .1       0  447.02      .1       0  632.82      .1       0
   676.2    .045       0   734.6      .1       0 1152.63     .05       0
 1757.57      .1       0 1959.22      .1       0
Bank Sta=676.2,734.6
XS Rating Curve= 0 ,0
Exp/Cntr(USF)=0,0
Exp/Cntr=0.3,0.1

Type RM Length L Ch R = 1 ,92440   ,600,599.8,606.5
XS GIS Cut Line= 4
2474208.00274837598816.9622895542474651.72467158 598424.24288625
 2474809.8324833597827.513403308  2474983.241051 596557.55065756
#Sta/Elev= 30
       0 1602.22    62.4 1583.56   131.9  1572.6  325.341564.923  647.18 1560.77
     691 1547.63  753.661546.865  803.221546.563   825.7  1542.4   900.2 1543.21
   910.2 1547.87   991.2 1545.07 1179.611549.066  1557.7 1548.89    1590 1545.26
  1642.5 1549.84  1832.9  1549.9    1879 1546.68  1900.8 1549.71 1995.14 1548.87
  2031.8 1546.05  2070.4 1552.09  2074.4 1555.56 2096.911591.623  2122.9 1614.67
  2159.6 1638.53  2203.6 1656.35    2244 1663.96  2377.2 1676.79  2491.6  1695.3
#Mann= 9 ,-1 , 0
       0      .1       0  325.34     .05       0  647.18      .1       0
  753.66      .1       0  803.22    .045       0   910.2      .1       0
 1179.61     .05       0 1995.14      .1       0 2096.91      .1       0
Bank Sta=803.22,910.2
XS Rating Curve= 0 ,0
Exp/Cntr(USF)=0,0
Exp/Cntr=0.3,0.1

Type RM Length L Ch R = 1 ,91840   ,834.8,882.3,915.1
XS GIS Cut Line= 4
2474167.20073244598929.1678333552475258.65465851 598475.24540616
2475324.95793439 597995.821719012475493.26625009597062.475604665
#Sta/Elev= 30
       0 1608.39    38.5 1589.18    99.1 1569.81  240.431562.314  765.581558.524
     800 1542.02   826.9  1544.4     855 1540.88   910.1 1545.94  1030.6  1546.8
  1089.3 1543.56  1130.2 1546.62  1356.1 1545.18  1364.2 1541.56  1524.5  1540.9
  1572.7    1544  1594.3 1547.71  1657.8 1541.47 1689.961546.756 2067.341544.342
  2150.5 1543.87  2178.1 1562.48  2191.8  1576.2 2205.87 1586.51  2313.3 1653.78
  2398.4 1699.17  2451.5  1718.2  2475.9  1721.8 2515.411722.405  2614.5 1716.44
#Mann= 9 ,-1 , 0
       0      .1       0  240.43     .05       0  765.58      .1       0
  1356.1    .045       0  1572.7    .025       0 1689.96     .05       0
 2067.34      .1       0 2205.87      .1       0 2515.41      .1       0
Bank Sta=1356.1,1572.7
XS Rating Curve= 0 ,0
Exp/Cntr(USF)=0,0
Exp/Cntr=0.3,0.1

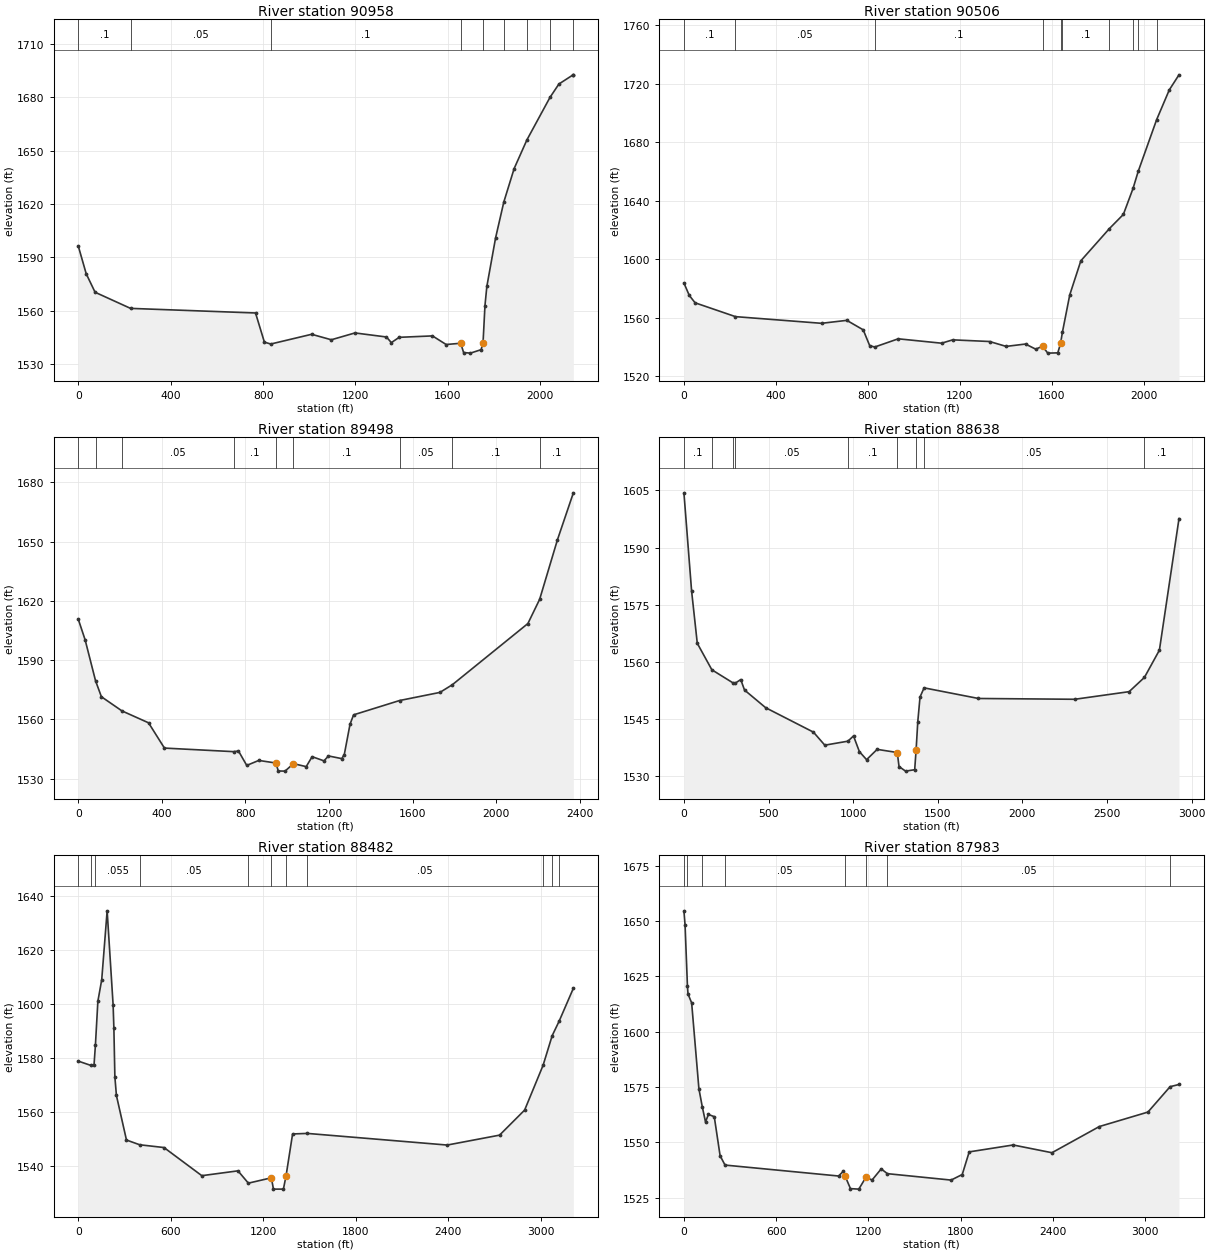
Type RM Length L Ch R = 1 ,90958   ,439.4,451.5,478.6
XS GIS Cut Line= 4
2474182.50148841598949.5688413192475585.07078593598434.443390232
2475982.89044122598306.9370904582476207.30152882598250.834318558
#Sta/Elev= 30
       0 1596.31    34.3  1580.7    72.7 1570.31   226.2 1561.23   767.3 1558.64
   805.6 1542.23  833.161541.156  1010.2 1546.64  1095.4 1543.55  1197.7  1547.4
    1334 1545.12  1355.3 1541.95  1389.2 1544.93  1533.3 1545.73  1592.5 1540.88
  1655.5 1541.59  1668.1 1536.36  1697.6 1536.03  1743.8 1537.97  1752.2 1541.78
  1760.6 1562.85  1768.7 1573.58  1806.5 1600.91 1842.25 1621.17  1886.9 1639.97
 1942.451656.182 2042.121680.059  2080.8 1687.59 2141.791692.7082143.245 1692.75
#Mann= 9 ,-1 , 0
       0      .1       0   226.2     .05       0  833.16      .1       0
  1655.5    .045       0  1752.2      .1       0 1842.25      .1       0
 1942.45     .12       0 2042.12      .1       0 2141.79      .1       0
Bank Sta=1655.5,1752.2
XS Rating Curve= 0 ,0
Exp/Cntr(USF)=0,0
Exp/Cntr=0.3,0.1

Type RM Length L Ch R = 1 ,90506   ,982.9,1007.9,987.8
XS GIS Cut Line= 4
 2474192.7019924599005.671613219 2474922.0380271598755.759265663
2475906.38666136598827.1627935362476268.50455272598669.054981816
#Sta/Elev= 30
       0 1583.66    23.3 1575.14    48.7 1570.09  224.191560.641   598.4 1556.08
   708.3  1558.1   779.7 1551.62   807.8 1540.83   829.51539.859   932.1 1545.48
  1120.6 1542.48  1168.7 1544.77  1329.1 1543.64  1401.3 1540.29  1485.5 1541.91
  1529.9  1538.4  1559.7 1540.44  1582.2 1535.69  1625.9 1535.87 1637.92 1542.32
 1646.121550.086    1678 1575.57  1726.2 1598.84 1850.691620.903  1911.1 1630.54
 1953.211648.321  1975.81660.045 2055.741695.313  2110.8 1715.69    2153 1725.99
#Mann= 10 ,-1 , 0
       0      .1       0  224.19     .05       0   829.5      .1       0
  1559.7    .045       0 1637.92      .1       0 1646.12      .1       0
 1850.69     .12       0 1953.21      .1       0  1975.8     .12       0
 2055.74      .1       0
Bank Sta=1559.7,1637.92
XS Rating Curve= 0 ,0
Exp/Cntr(USF)=0,0
Exp/Cntr=0.3,0.1

Type RM Length L Ch R = 1 ,89498   ,816.2,860.3,880.9
XS GIS Cut Line= 4
2474054.99518864599224.9824488312474769.03046737599388.190512541
2475437.16347819599495.2958043512476385.81034851599643.203112089
#Sta/Elev= 30
       0 1610.68    32.6 1600.31   82.571579.556   110.5 1571.48   208.71564.312
   336.2 1558.27   412.2 1545.48   744.31543.665   766.6 1544.01   806.1  1536.7
   863.8 1539.23   945.8 1537.91     957 1533.89   989.4 1533.81  1029.6 1537.59
  1090.7 1536.09    1119 1541.12  1175.8 1539.01  1197.2  1541.5  1260.8 1540.14
    1273 1542.22  1300.5 1557.59  1317.5 1562.31 1537.421569.551  1730.5 1573.66
 1789.931577.544  2151.6 1608.53 2207.811620.783  2293.2 1650.99  2369.2 1674.71
#Mann= 9 ,-1 , 0
       0      .1       0   82.57      .1       0   208.7     .05       0
   744.3      .1       0   945.8    .045       0  1029.6      .1       0
 1537.42     .05       0 1789.93      .1       0 2207.81      .1       0
Bank Sta=945.8,1029.6
XS Rating Curve= 0 ,0
Exp/Cntr(USF)=0,0
Exp/Cntr=0.3,0.1

Type RM Length L Ch R = 1 ,88638   ,171,155.9,148.3
XS GIS Cut Line= 4
2473886.17174749599346.0165288282474574.01723225600015.271595081
2475027.62344382600387.0799652222476384.72399483600632.473489515
#Sta/Elev= 30
       0 1604.38    45.4 1578.55    78.9 1564.84  165.061557.878  287.121554.516
  303.371554.365   335.7 1555.31     358 1552.56   483.1 1547.91   765.4 1541.49
   832.4 1538.07  969.031539.119    1002 1540.49  1036.7 1536.38  1079.3 1534.26
  1141.7 1536.97  1260.6 1536.14    1271 1532.46  1309.6 1531.25  1363.6 1531.62
 1371.891536.807  1381.9 1544.28  1395.1 1550.73 1419.121553.132  1740.4 1550.34
  2309.5 1550.13  2630.6 1552.13 2720.991555.872  2809.5 1563.03  2925.3  1597.6
#Mann= 9 ,-1 , 0
       0      .1       0  165.06     .05       0  287.12    .055       0
  303.37     .05       0  969.03      .1       0  1260.6    .045       0
 1371.89      .1       0 1419.12     .05       0 2720.99      .1       0
Bank Sta=1260.6,1371.89
XS Rating Curve= 0 ,0
Exp/Cntr(USF)=0,0
Exp/Cntr=0.3,0.1

Type RM Length L Ch R = 1 ,88482   ,501.7,498.7,496.4
XS GIS Cut Line= 4
2473737.44839943599639.7451412392474529.40022783600238.356617166
2475273.01696811600662.2181591262476618.96326802600874.148930107
#Sta/Elev= 30
       0 1578.86   82.881577.243   101.9 1577.31  110.921584.666     127 1601.01
     152 1609.01   187.1 1634.51   225.9 1599.65   230.8 1591.08   237.3    1573
   247.3 1566.13   312.5 1549.64  398.391547.884   555.8 1546.86   801.2 1536.44
  1035.7 1538.23 1103.121533.671  1252.2 1535.65  1265.9 1531.46  1330.4 1531.47
 1347.271536.249    1390 1551.89 1485.931552.088    2393 1547.78  2732.4 1551.45
  2895.1 1560.73 3014.851577.316 3073.921588.302 3119.371593.705  3211.2 1605.83
#Mann= 11 ,-1 , 0
       0    .055       0   82.88     .06       0  110.92    .055       0
  398.39     .05       0 1103.12      .1       0  1252.2    .045       0
 1347.27      .1       0 1485.93     .05       0 3014.85      .1       0
 3073.92     .05       0 3119.37     .06       0
Bank Sta=1252.2,1347.27
XS Rating Curve= 0 ,0
Exp/Cntr(USF)=0,0
Exp/Cntr=0.3,0.1

Type RM Length L Ch R = 1 ,87983   ,561,544.3,527.9
XS GIS Cut Line= 4
2473592.44313508600234.6385334642474291.44287094600680.808577633
2475265.58080071601205.058379532 2476548.3196777601249.675383949
#Sta/Elev= 30
       0 1654.64     7.5 1648.12   22.841620.609    26.5 1617.05    50.2 1613.03
    97.4 1574.16   119.71565.922   140.3 1559.18   159.3 1562.58   197.3 1561.56
   235.3 1543.89  267.251539.685  1005.6 1534.74    1037 1536.93 1048.451534.646
  1082.8 1529.03  1137.2 1528.81  1182.8 1534.12  1223.7 1532.96  1282.7 1537.96
 1322.86  1535.8    1737  1532.9  1809.6 1535.42    1855 1545.65  2140.8 1548.77
  2392.9 1545.27  2701.1 1557.11  3017.1 1563.65 3161.171575.129    3219 1576.13
#Mann= 8 ,-1 , 0
       0      .1       0   22.84      .1       0   119.7     .06       0
  267.25     .05       0 1048.45    .045       0  1182.8      .1       0
 1322.86     .05       0 3161.17     .06       0
Bank Sta=1048.45,1182.8
XS Rating Curve= 0 ,0
Exp/Cntr(USF)=0,0
Exp/Cntr=0.3,0.1

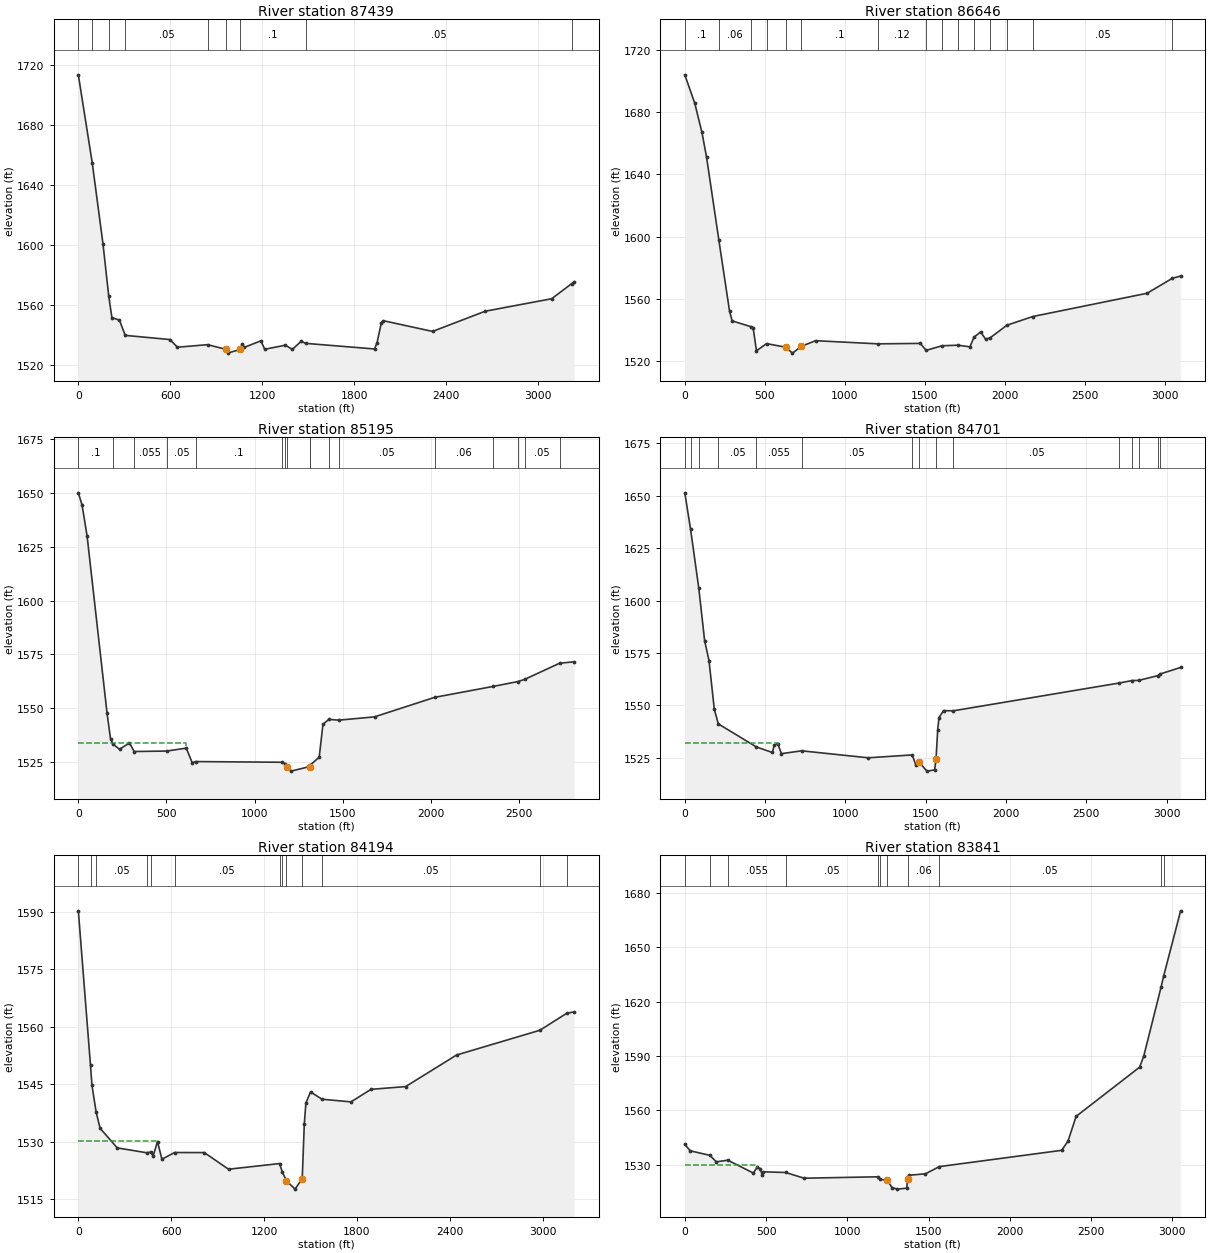
Type RM Length L Ch R = 1 ,87439   ,810,792.9,761.7
XS GIS Cut Line= 4
2473361.92194559601089.7977847882474038.61317925 601253.39346765
2475403.14989766601550.8401637632476508.40420485601260.280932182
#Sta/Elev= 30
       0 1713.46   90.581654.956   160.7  1601.1  198.321566.189     219  1551.9
   268.3 1550.13  306.051540.012   597.6 1537.24   646.9 1532.13  843.371533.834
   966.1 1530.64   974.7  1528.2  1056.6  1530.7  1068.9 1534.27  1081.2 1531.96
  1191.7 1536.41  1216.2 1530.75  1351.3  1533.5  1396.4 1530.66  1453.8 1536.06
 1483.861534.695  1932.7 1530.97  1949.1 1535.03  1977.7 1548.57    1990 1549.78
  2311.6 1542.65  2654.8 1556.08  3089.1 1564.42 3219.861574.484  3235.6 1575.73
#Mann= 9 ,-1 , 0
       0      .1       0   90.58      .1       0  198.32     .06       0
  306.05     .05       0  843.37      .1       0   966.1    .045       0
  1056.6      .1       0 1483.86     .05       0 3219.86     .06       0
Bank Sta=966.1,1056.6
XS Rating Curve= 0 ,0
Exp/Cntr(USF)=0,0
Exp/Cntr=0.3,0.1

Type RM Length L Ch R = 1 ,86646   ,1430.3,1451.5,1388.4
XS GIS Cut Line= 4
2473622.18780469 602257.276067032474016.30467704602168.042058197
2475399.43181396601811.106022861 2476543.5075177601267.062207549
#Sta/Elev= 30
       0 1703.89    62.1 1685.74   107.2 1666.95   135.9  1651.1  212.481598.133
   279.5 1552.35   295.9    1546  411.511542.324   427.3 1541.51   447.9 1526.79
  511.25  1531.4   629.7 1529.13   673.1  1525.3   728.8 1529.66   817.5 1533.28
  1209.4 1531.25  1472.4 1531.54 1508.61 1527.07 1608.351530.037 1708.081530.391
  1782.3 1529.33 1807.821535.563  1849.5  1538.9  1880.5 1534.19 1910.341535.243
 2013.771543.219 2175.171548.787  2890.4 1563.73 3048.121573.356  3099.4 1574.74
#Mann= 15 ,-1 , 0
       0      .1       0  212.48     .06       0  411.51     .05       0
  511.25      .1       0   629.7    .045       0   728.8      .1       0
  1209.4     .12       0 1508.61      .1       0 1608.35      .1       0
 1708.08     .05       0 1807.82     .06       0 1910.34     .05       0
 2013.77     .06       0 2175.17     .05       0 3048.12     .06       0
Bank Sta=629.7,728.8
XS Rating Curve= 0 ,0
Exp/Cntr(USF)=0,0
Exp/Cntr=0.3,0.1

Type RM Length L Ch R = 1 ,85195   ,496.5,493.9,490.8
XS GIS Cut Line= 4
2474530.70939804603216.9311495262474955.68636511602822.070660437
2475671.78928601602082.5438122262476565.24479945601276.091457391
#Sta/Elev= 30
       0  1650.1    21.3 1644.41    49.6  1630.1   162.8 1547.83   182.6 1535.84
  197.181533.357   233.6 1530.98   290.2 1533.92  316.531529.929  501.521530.153
   612.4  1531.5   645.8 1524.79  668.82 1525.26 1153.941524.943 1173.76 1524.23
  1185.9 1522.95  1206.8 1520.82  1313.9 1522.96 1315.641523.656  1366.5 1527.26
  1387.9 1542.59 1421.541544.866 1477.351544.496  1680.6 1546.03 2021.291555.087
 2353.67 1560.17 2494.231562.434 2531.581563.418  2730.71570.957  2813.1  1571.6
#Mann= 17 ,-1 , 0
       0      .1       0  197.18     .06       0  316.53    .055       0
  501.52     .05       0  668.82      .1       0 1153.94    .025       0
 1173.76      .1       0  1185.9    .045       0  1313.9      .1       0
 1315.64     .06       0 1421.54    .055       0 1477.35     .05       0
 2021.29     .06       0 2353.67     .05       0 2494.23     .06       0
 2531.58     .05       0  2730.7     .06       0
#XS Ineff= 2 , 0
          610.42 1534.05
Permanent Ineff=
       F       F
Bank Sta=1185.9,1313.9
XS Rating Curve= 0 ,0
Exp/Cntr(USF)=0,0
Exp/Cntr=0.3,0.1

Type RM Length L Ch R = 1 ,84701   ,509.1,506.8,501.2
XS GIS Cut Line= 4
2474704.71571527603715.5261738852475608.21005471602868.918515074
2476059.95722443 602356.938389392476578.62990078601312.900486035
#Sta/Elev= 30
       0 1651.43   35.631634.218    86.91606.016   123.4  1580.9   150.8  1571.3
   183.7 1548.12  208.661541.158  445.991530.155   545.2 1527.51   556.7 1531.02
   578.4  1531.8   601.8 1526.96  727.731528.312  1141.7 1524.98 1415.681526.356
  1438.2 1521.57  1459.6 1522.75  1507.6 1518.62  1555.6  1519.2 1564.151524.639
  1574.5 1538.38  1582.3 1544.15  1610.8 1547.48 1672.611547.417 2705.971560.688
 2784.831561.854  2825.41561.909 2944.821564.188 2955.331564.871  3086.7  1568.1
#Mann= 15 ,-1 , 0
       0     .12       0   35.63      .1       0    86.9      .1       0
  208.66     .05       0  445.99    .055       0  727.73     .05       0
 1415.68      .1       0  1459.6    .045       0 1564.15     .06       0
 1672.61     .05       0 2705.97     .06       0 2784.83     .05       0
  2825.4     .06       0 2944.82     .05       0 2955.33     .06       0
#XS Ineff= 2 , 0
          581.89 1532.12
Permanent Ineff=
       F       F
Bank Sta=1459.6,1564.15
XS Rating Curve= 0 ,0
Exp/Cntr(USF)=0,0
Exp/Cntr=0.3,0.1

Type RM Length L Ch R = 1 ,84194   ,344.2,353.1,361.9
XS GIS Cut Line= 4
 2475122.8871589603969.2082604622476039.55382556603160.874927118
2476364.55382556602730.3193715812476617.33160335601310.874927133
#Sta/Elev= 30
       01590.206   78.631549.925  88.173 1544.72  114.841537.803 140.4071533.554
 251.4641528.432  440.881527.173  466.941527.335 483.321 1526.32  511.521530.092
 540.0011525.484     6221527.229 813.9111527.208  970.431522.875 1299.851524.348
 1318.33  1522.1  1344.91519.8621400.0551517.688  1446.6 1520.441459.8361534.629
1470.2181540.1311500.2881543.006 1574.791541.1071761.6091540.4281891.0431543.691
2114.5041544.4062443.6011552.636 2981.911559.084 3155.711563.5223203.386 1563.88
#Mann= 13 ,-1 , 0
       0      .1       0   78.63      .1       0  114.84     .05       0
  440.88     .06       0  466.94    .055       0     622     .05       0
 1299.85     .05       0 1318.33      .1       0  1344.9    .045       0
  1446.6     .06       0 1574.79     .05       0 2981.91     .06       0
 3155.71     .05       0
#XS Ineff= 2 , 0
          508.06 1530.33
Permanent Ineff=
       F       F
Bank Sta=1344.9,1446.6
XS Rating Curve= 0 ,0
Exp/Cntr(USF)=0,0
Exp/Cntr=0.3,0.1

Type RM Length L Ch R = 1 ,83841   ,278.2,279.8,283.5
XS GIS Cut Line= 4
2475414.24508621604121.0517503352476311.04687499603351.408424143
2476659.05950944603013.4346156852477475.55069027601895.778655041
#Sta/Elev= 30
       0 1541.28      34 1537.76   154.5 1535.27   193.7  1531.7  264.771532.594
   421.7 1525.51   445.5 1528.74     464 1527.97   476.2 1524.51   484.1 1526.18
  620.061525.837   734.2 1522.68 1189.221523.454 1202.841522.026  1245.7 1521.52
  1275.3  1517.5  1308.8 1516.66  1365.4 1517.18  1371.71522.092  1377.1 1524.26
  1481.1 1525.12 1566.351529.067    2319 1538.04    2358 1543.12  2408.1 1556.77
  2798.8 1583.86  2824.3 1590.01 2930.841627.984  2946.9 1634.16    3051 1669.99
#Mann= 11 ,-1 , 0
       0      .1       0   154.5     .05       0  264.77    .055       0
  620.06     .05       0 1189.22     .05       0 1202.84      .1       0
  1245.7    .045       0  1371.7     .06       0 1566.35     .05       0
 2930.84     .12       0  2946.9      .1       0
#XS Ineff= 2 , 0
          442.93 1529.88
Permanent Ineff=
       F       F
Bank Sta=1245.7,1371.7
XS Rating Curve= 0 ,0
Exp/Cntr(USF)=0,0
Exp/Cntr=0.5,0.3

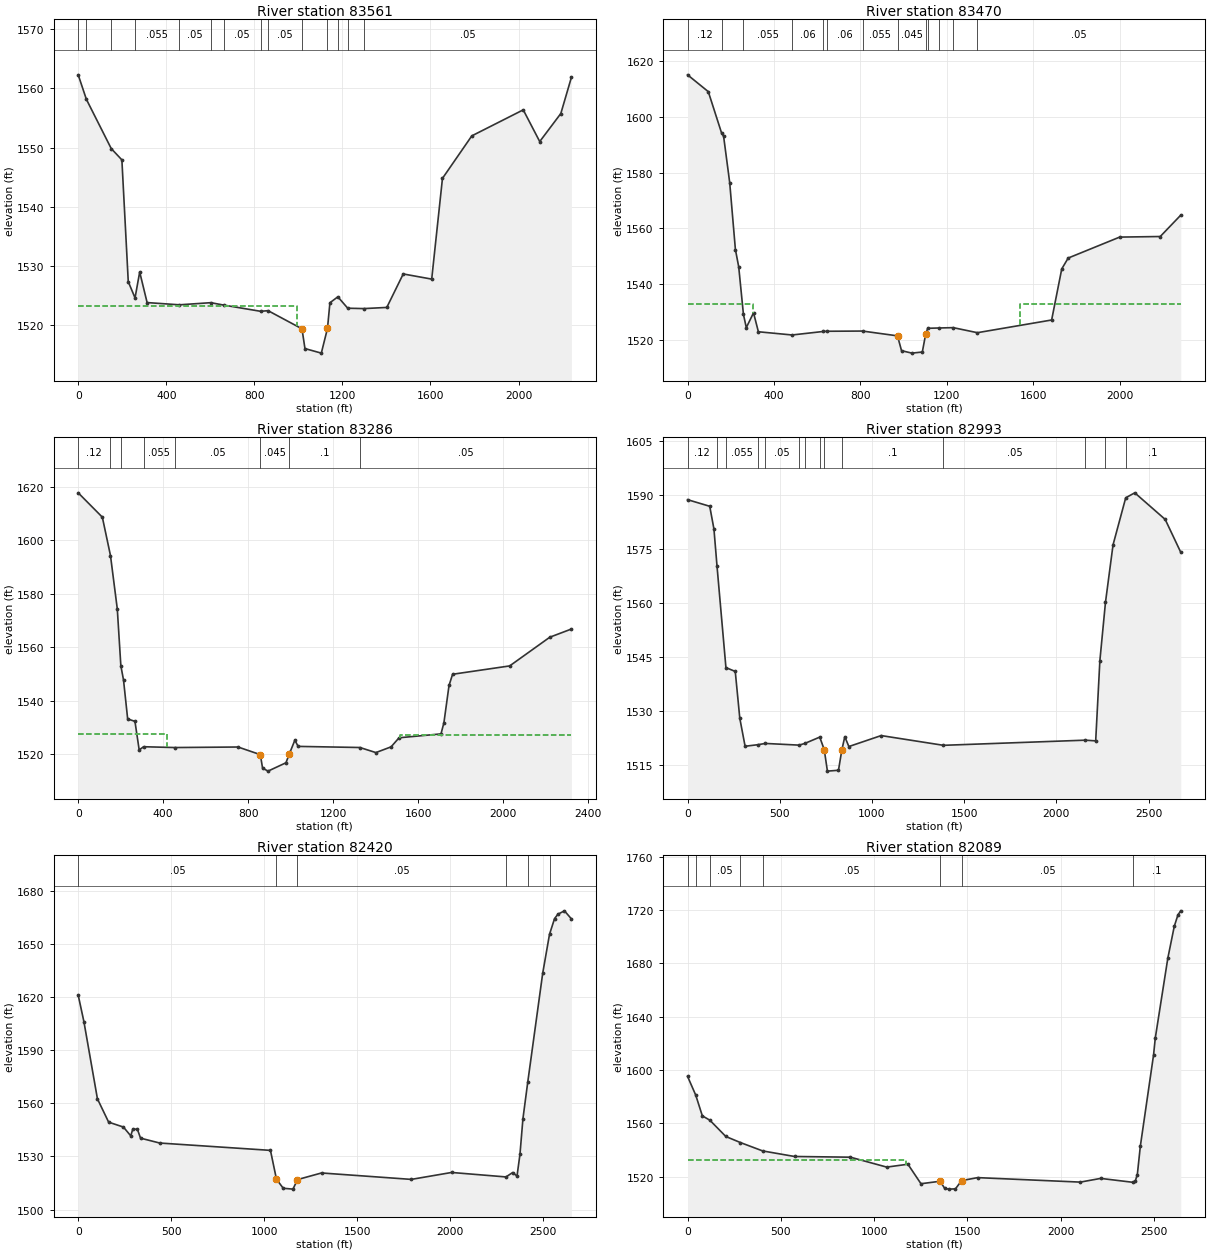
Type RM Length L Ch R = 1 ,83561   ,88.7,90.8,85.7
XS GIS Cut Line= 4
2475721.98341598604157.2345176132476451.47143819603591.713986628
2476846.33192728603233.6625261822477187.65201107602527.598431285
#Sta/Elev= 30
       0 1562.27   36.991558.149  150.081549.824   198.4 1547.92   227.4 1527.36
  258.191524.626   279.3    1529     313 1523.84  459.631523.463  602.441523.823
  661.081523.415  828.621522.367  862.531522.474  1016.5 1519.41    1030 1516.08
  1104.3 1515.31  1132.3 1519.48  1143.4 1523.81 1179.411524.811 1224.371522.887
 1297.821522.825  1401.7 1523.02  1476.4 1528.67  1605.7  1527.8  1654.6  1544.8
  1787.9 1551.97  2021.5 1556.36  2096.4 1551.01  2192.2 1555.74  2240.3 1561.84
#Mann= 14 ,-1 , 0
       0      .1       0   36.99     .12       0  150.08      .1       0
  258.19    .055       0  459.63     .05       0  602.44    .055       0
  661.08     .05       0  828.62    .055       0  862.53     .05       0
  1016.5    .045       0  1132.3     .06       0 1179.41    .055       0
 1224.37      .1       0 1297.82     .05       0
#XS Ineff= 2 , 0
          992.56 1523.32    1172          1523.2
Permanent Ineff=
       F       F
Bank Sta=1016.5,1132.3
XS Rating Curve= 0 ,0
Exp/Cntr(USF)=0,0
Exp/Cntr=0.5,0.3

Type RM Length L Ch R = 1 ,83470   ,163.9,184.2,167
XS GIS Cut Line= 4
2475869.21953055604301.1243568572476481.58791617 603675.37086991
2476950.06646255603257.0864535012477214.26309833602525.016880255
#Sta/Elev= 30
       0 1615.09      96 1609.05  158.151594.037   166.7  1593.1     195 1576.42
   221.4 1552.38   236.7 1546.18   258.61529.092   271.8 1524.35   305.3 1529.66
   327.7 1522.86  483.841521.706  628.821522.973  646.681523.041  809.531523.113
  971.41 1521.39     990 1516.07    1038 1515.19  1086.2 1515.59  1102.3 1522.22
 1111.281524.103 1161.611524.214  1229.11524.338 1341.011522.526  1684.5 1527.08
  1731.3 1545.42  1761.1 1549.32  1999.2 1556.84    2187 1557.05  2281.9 1564.72
#Mann= 13 ,-1 , 0
       0     .12       0  158.15      .1       0   258.6    .055       0
  483.84     .06       0  628.82     .05       0  646.68     .06       0
  809.53    .055       0  971.41    .045       0  1102.3    .055       0
 1111.28     .06       0 1161.61    .055       0  1229.1      .1       0
 1341.01     .05       0
#XS Ineff= 2 , 0
          303.97  1532.9  1539.9            1533
Permanent Ineff=
       F       F
Bank Sta=971.41,1102.3
XS Rating Curve= 0 ,0
Exp/Cntr(USF)=0,0
Exp/Cntr=0.5,0.3

Type RM Length L Ch R = 1 ,83286   ,290.6,292.8,308
XS GIS Cut Line= 4
2476033.18702178604374.742414145 2476494.9730175603869.454839124
2476953.41273788603481.2869006962477267.96261902602494.135677972
#Sta/Elev= 30
       0 1617.75   113.6 1608.65  151.931594.312     184 1574.36  200.711553.144
   213.3  1547.8   232.8 1533.27   267.1 1532.36     287 1521.69  307.751522.885
  454.041522.582   752.4 1522.78   857.2 1519.93   867.7 1514.92   893.4 1513.77
   977.7 1516.89   992.7 1519.99  1019.7 1525.33  1035.3 1523.01  1325.61522.597
  1401.1  1520.7  1472.5 1522.84  1510.2 1526.23  1707.5 1527.68  1721.2 1531.83
  1745.3 1545.77  1762.1 1549.96  2030.8 1553.08  2219.7 1563.81  2321.3 1566.86
#Mann= 8 ,-1 , 0
       0     .12       0  151.93      .1       0  200.71     .06       0
  307.75    .055       0  454.04     .05       0   857.2    .045       0
   992.7      .1       0  1325.6     .05       0
#XS Ineff= 2 , 0
          418.73  1527.8 1516.75         1527.34
Permanent Ineff=
       F       F
Bank Sta=857.2,992.7
XS Rating Curve= 0 ,0
Exp/Cntr(USF)=0,0
Exp/Cntr=0.3,0.1

Type RM Length L Ch R = 1 ,82993   ,607.6,573.7,524.8
XS GIS Cut Line= 4
2476161.38945907604453.4131426882476663.33075876 604089.04093995
2477187.58056066603694.9240676012478340.18650809602902.972239201
#Sta/Elev= 30
       0 1588.77   120.3 1586.93   143.1 1580.63  159.85 1570.28  208.131542.102
   258.7 1541.04   283.4    1528   312.1 1520.25  382.33 1520.69  421.861521.033
   604.81520.564  635.111521.019  716.86 1522.79   741.3  1519.3   758.5 1513.34
   818.5 1513.58   836.8 1519.24   852.8 1522.91   874.7 1520.17    1050 1523.22
 1387.661520.512 2156.521521.941  2213.3 1521.75    2236 1544.04 2266.361560.236
  2307.4 1576.21  2376.21589.297  2425.3 1590.67  2590.2 1583.28  2674.6 1574.15
#Mann= 14 ,-1 , 0
       0     .12       0  159.85     .06       0  208.13    .055       0
  382.33     .05       0  421.86     .05       0   604.8     .05       0
  635.11     .05       0  716.86      .1       0   741.3    .045       0
   836.8      .1       0 1387.66     .05       0 2156.52      .1       0
 2266.36     .12       0  2376.2      .1       0
Bank Sta=741.3,836.8
XS Rating Curve= 0 ,0
Exp/Cntr(USF)=0,0
Exp/Cntr=0.3,0.1

Type RM Length L Ch R = 1 ,82420   ,326.5,330.6,338
XS GIS Cut Line= 4
2476592.26083018605040.8092245182477247.06989988604371.615301257
 2477299.1230717603992.3707637142478303.00567108603114.903010181
#Sta/Elev= 30
       01620.952  30.666 1606.02 103.4191562.445 163.6931549.291 243.3291546.519
 282.5031541.571 293.6961545.351 318.1151545.307 335.2731540.263 438.2211537.511
1033.8981533.3691066.1981517.1091102.5361511.9851155.0231511.4981179.2481516.877
1308.4481520.6171791.389 1516.992008.131  1520.9 2300.591518.3772336.3441520.862
2359.8411518.8432375.7791531.1772391.7171551.249 2417.64  1571.9 2497.971633.282
 2534.681655.3172561.7211664.1322579.4651666.5912614.8481668.5352652.3821663.992
#Mann= 6 ,-1 , 0
       0     .05       01066.198    .045       01179.248     .05       0
 2300.59      .1       0 2417.64      .1       0 2534.68    .055       0
Bank Sta=1066.198,1179.248
XS Rating Curve= 0 ,0
Exp/Cntr(USF)=0,0
Exp/Cntr=0.3,0.1

Type RM Length L Ch R = 1 ,82089   ,1173.5,1251.5,1263.7
XS GIS Cut Line= 4
2476696.79351207605230.4926362832477548.23467969604434.822724181
2477633.75060483604070.4505214432478384.80351251603259.908274536
#Sta/Elev= 30
       0  1595.3   43.991581.187    79.3 1565.66  119.491562.405   205.2 1550.18
  283.171545.641  402.761539.339   573.5 1535.17   873.2 1534.64    1068  1527.2
  1181.7 1529.35  1251.6 1514.72  1354.3 1516.58  1378.9 1511.22  1399.5 1510.67
  1436.5 1510.86  1469.3 1517.05  1555.4  1519.3  2106.1 1515.94  2215.2 1518.72
 2389.971515.757  2400.5 1516.62  2411.8 1521.62  2427.9 1542.93  2498.8 1611.38
    2508 1624.02  2575.1 1683.86  2609.9 1707.93  2629.7 1716.55  2644.6 1719.53
#Mann= 8 ,-1 , 0
       0      .1       0   43.99      .1       0  119.49     .05       0
  283.17    .055       0  402.76     .05       0  1354.3    .045       0
  1469.3     .05       0 2389.97      .1       0
#XS Ineff= 2 , 0
         1168.73 1532.34
Permanent Ineff=
       F       F
Bank Sta=1354.3,1469.3
XS Rating Curve= 0 ,0
Exp/Cntr(USF)=0,0
Exp/Cntr=0.3,0.1