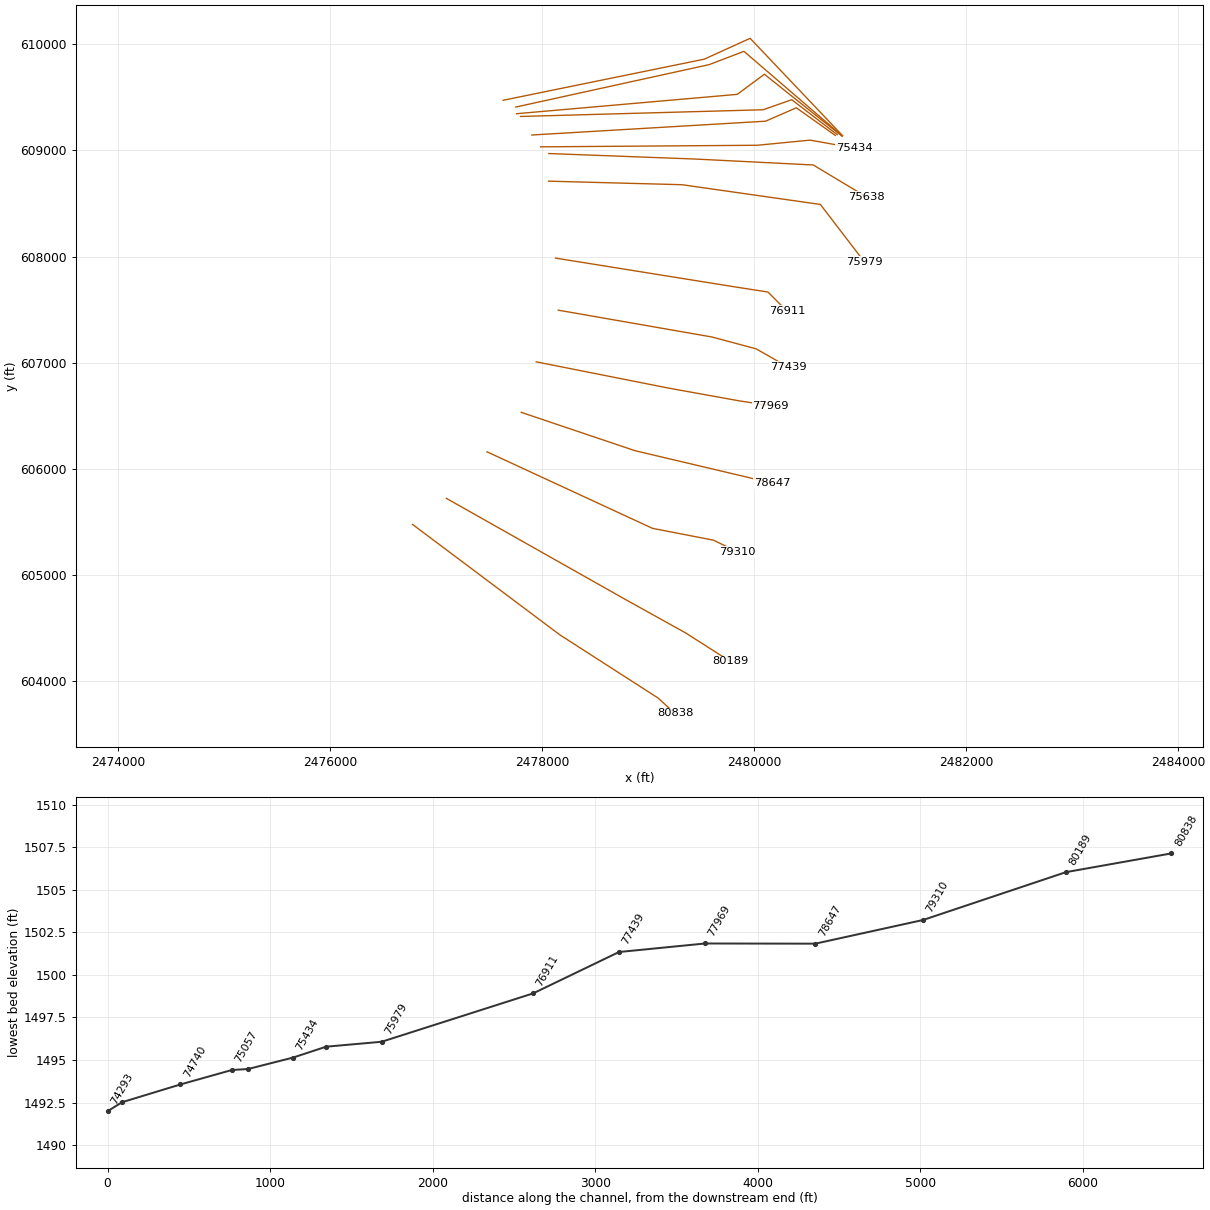
HEC-RAS study SFSBPOTOMC.prj: SFSBPOTOMC

--- SFSBPOTOMC.g01 (geometry) --- (continued)

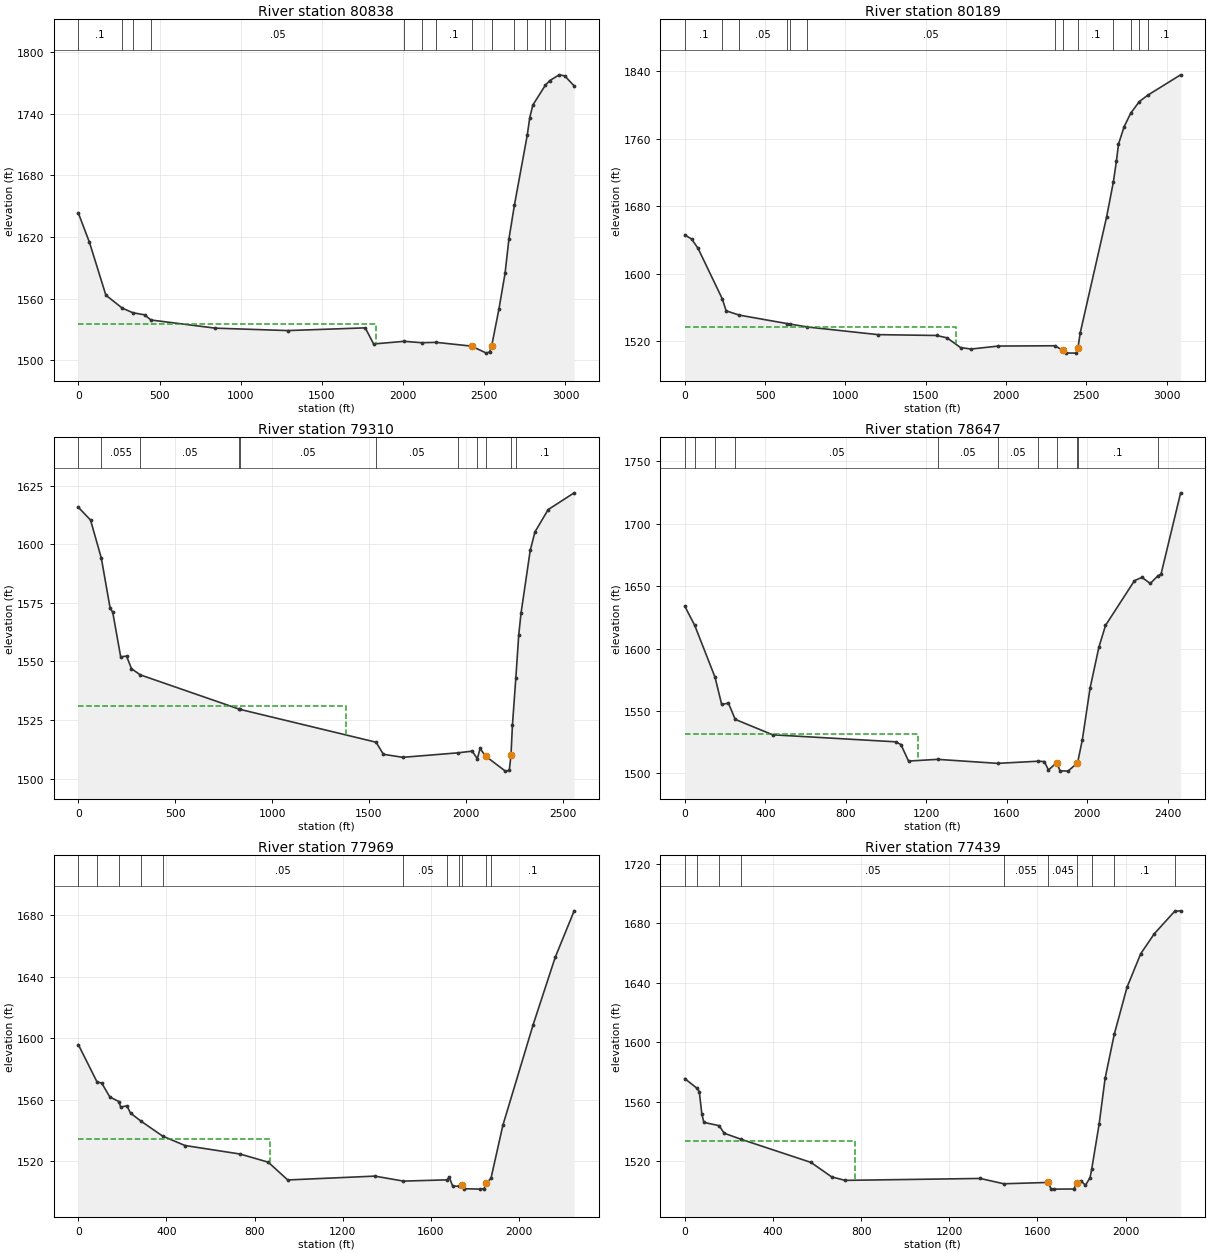
Type RM Length L Ch R = 1 ,80838   ,647,648.5,650.8
XS GIS Cut Line= 4
 2476774.8732698605475.8861605762478165.43657413604434.822724181
2479091.23941578603839.9293319562479251.11701494603694.924067601
#Sta/Elev= 30
       0 1643.46    68.4 1614.95   169.7  1563.5  269.771551.002  334.821546.467
   408.8 1544.34   446.91539.368   844.3 1531.42  1289.3 1529.07  1766.9 1531.71
  1818.4 1516.04 2006.651518.614 2114.971517.257 2203.781517.622 2421.231513.944
  2513.2 1507.13  2532.7 1508.33 2545.141513.943  2589.7 1549.59  2627.8 1584.68
  2651.5 1617.98 2685.311650.909 2764.831719.422  2779.9 1736.12  2798.9 1748.44
 2876.461767.869 2902.731772.208  2961.1 1777.86 2994.881776.887  3053.4 1767.09
#Mann= 14 ,-1 , 0
       0      .1       0  269.77     .05       0  334.82    .055       0
   446.9     .05       0 2006.65      .1       0 2114.97     .05       0
 2203.78      .1       0 2421.23    .045       0 2545.14      .1       0
 2685.31    .055       0 2764.83     .12       0 2876.46      .1       0
 2902.73      .1       0 2994.88      .1       0
#XS Ineff= 2 , 0
         1832.51 1535.33
Permanent Ineff=
       F       F
Bank Sta=2421.23,2545.14
XS Rating Curve= 0 ,0
Exp/Cntr(USF)=0,0
Exp/Cntr=0.3,0.1

Type RM Length L Ch R = 1 ,80189   ,851.4,879.4,890.2
XS GIS Cut Line= 4
2477094.62846812605721.2796848692478775.20230116 604773.16834101
2479351.50527488604453.4131426882479771.64873314604185.711116187
#Sta/Elev= 30
       0 1646.12    42.9 1641.21    82.8 1630.16  233.34 1570.39   257.3 1556.18
  339.181551.089  634.03 1541.15  656.691540.458  762.531537.022  1202.7 1527.95
  1567.9 1526.96    1633 1524.11  1716.6 1512.62  1782.1 1510.88  1951.9 1514.41
 2304.061514.765  2351.6 1509.55  2372.8  1506.2  2436.8 1506.03 2447.771512.419
  2461.9  1530.2  2625.7 1667.17 2667.591708.448  2687.3 1733.93    2700 1753.77
  2734.8 1774.35 2775.721790.379 2829.721804.291 2883.851812.032  3086.8 1835.98
#Mann= 13 ,-1 , 0
       0      .1       0  233.34     .06       0  339.18     .05       0
  634.03     .05       0  656.69     .05       0  762.53     .05       0
 2304.06      .1       0  2351.6    .045       0 2447.77      .1       0
 2667.59     .12       0 2775.72      .1       0 2829.72      .1       0
 2883.85      .1       0
#XS Ineff= 2 , 0
         1689.21 1537.16
Permanent Ineff=
       F       F
Bank Sta=2351.6,2447.77
XS Rating Curve= 0 ,0
Exp/Cntr(USF)=0,0
Exp/Cntr=0.3,0.1

Type RM Length L Ch R = 1 ,79310   ,665.2,662.6,660.3
XS GIS Cut Line= 4
2477477.59108937606160.0135616362479039.18624396605438.705323562
2479615.48921768 605327.162812522479842.29232346605215.620301477
#Sta/Elev= 30
       0 1615.82      63 1610.36  118.851594.056   164.3 1572.68   177.5 1571.06
   218.7 1551.98   248.9  1552.3   274.4 1546.93  320.181544.286     8281529.748
  835.711529.552 1537.15 1515.56    1575  1510.4  1675.6 1509.11  1960.81511.036
  2033.4 1511.75 2060.161508.505  2074.1 1512.88  2102.7 1509.61  2204.8 1503.22
  2224.9 1503.53 2233.761509.997  2241.2 1522.82 2258.891543.106  2273.8 1561.35
  2285.6 1570.61    2333 1597.38  2357.5 1605.29  2425.6 1614.81  2559.9 1621.97
#Mann= 11 ,-1 , 0
       0      .1       0  118.85    .055       0  320.18     .05       0
     828     .05       0  835.71     .05       0 1537.15     .05       0
  1960.8    .025       0 2060.16      .1       0  2102.7    .045       0
 2233.76      .1       0 2258.89      .1       0
#XS Ineff= 2 , 0
         1380.89 1531.08
Permanent Ineff=
       F       F
Bank Sta=2102.7,2233.76
XS Rating Curve= 0 ,0
Exp/Cntr(USF)=0,0
Exp/Cntr=0.3,0.1

Type RM Length L Ch R = 1 ,78647   ,676,678.4,681.4
XS GIS Cut Line= 4
2477801.06437139606531.821931777 2478871.8724774 606171.16781274
 2479927.8082486605922.0562047452480169.48368919605862.566865523
#Sta/Elev= 30
       0 1633.88   49.281618.535  149.941577.123   183.3 1555.21   216.8 1556.28
  250.611543.261   436.5 1530.92  1048.5 1525.29  1073.9 1523.08  1111.8 1509.89
 1255.911511.259  1554.61508.048 1753.741509.745  1786.3 1509.51  1806.9 1502.76
    1848 1508.62  1864.4 1502.16    1904 1501.83 1950.871508.339 1952.871509.397
  1975.4 1526.98  2013.7 1568.26  2057.6 1601.04  2090.4 1618.46  2234.3 1654.29
  2271.4 1656.99  2312.6 1652.05 2351.231658.277  2366.2 1659.43  2463.7 1724.63
#Mann= 11 ,-1 , 0
       0    .055       0   49.28      .1       0  149.94     .06       0
  250.61     .05       0 1255.91     .05       0  1554.6     .05       0
 1753.74      .1       0    1848    .045       0 1950.87      .1       0
 1952.87      .1       0 2351.23      .1       0
#XS Ineff= 2 , 0
         1160.05 1531.85
Permanent Ineff=
       F       F
Bank Sta=1848,1950.87
XS Rating Curve= 0 ,0
Exp/Cntr(USF)=0,0
Exp/Cntr=0.3,0.1

Type RM Length L Ch R = 1 ,77969   ,534.5,529.4,525.1
XS GIS Cut Line= 4
2477942.35155204607007.7366455572479180.47342461606762.343121264
2479860.88274197606639.6463591182480154.61135438606595.029354701
#Sta/Elev= 30
       0 1595.85   84.681571.636   106.4 1570.79   143.1 1561.75  184.061558.827
   192.1 1555.23   220.6 1556.03   236.9 1551.28  283.431546.169  382.811536.328
   484.3 1530.21   734.4 1524.67   862.1 1519.36   950.5 1507.81  1345.8  1510.3
 1475.851507.061 1674.511507.879  1683.2 1509.83  1699.4  1503.7 1730.061503.795
  1740.1 1504.75  1752.7 1502.12  1821.4 1501.84  1841.7  1502.1  1849.8 1505.57
 1873.171508.859    1927 1543.32  2064.6 1608.83  2164.8 1652.67  2250.7 1682.88
#Mann= 11 ,-1 , 0
       0      .1       0   84.68      .1       0  184.06     .06       0
  283.43     .05       0  382.81     .05       0 1475.85     .05       0
 1674.51    .055       0 1730.06      .1       0  1740.1    .045       0
  1849.8      .1       0 1873.17      .1       0
#XS Ineff= 2 , 0
          871.59 1534.75
Permanent Ineff=
       F       F
Bank Sta=1740.1,1849.8
XS Rating Curve= 0 ,0
Exp/Cntr(USF)=0,0
Exp/Cntr=0.3,0.1

Type RM Length L Ch R = 1 ,77439   ,524.4,528.6,535.3
XS GIS Cut Line= 4
2478150.56423932607494.8056104422479600.61688287607241.975918746
2480017.04225743607130.4334077042480318.20703724606959.401557439
#Sta/Elev= 30
       0 1575.69   56.371569.053    65.8 1566.85    77.3 1551.85    86.5 1546.24
   155.71544.018   178.8 1538.94  255.021534.887   572.7 1519.29   666.1 1509.59
     727 1507.23  1340.1 1508.52  1446.91504.948  1649.3 1505.84  1660.5 1501.69
  1672.9 1501.34  1764.7 1501.44  1779.9 1505.56  1797.1 1506.81  1817.8 1503.95
  1838.5 1509.09 1846.071514.799    1880 1545.38  1906.9 1575.92 1948.521605.596
  2006.2 1637.09  2068.2 1659.64  2129.9 1673.09 2222.781688.276  2249.4 1688.52
#Mann= 10 ,-1 , 0
       0     .12       0   56.37     .06       0   155.7     .05       0
  255.02     .05       0  1446.9    .055       0  1649.3    .045       0
  1779.9      .1       0 1846.07      .1       0 1948.52      .1       0
 2222.78      .1       0
#XS Ineff= 2 , 0
          772.33 1533.59
Permanent Ineff=
       F       F
Bank Sta=1649.3,1779.9
XS Rating Curve= 0 ,0
Exp/Cntr(USF)=0,0
Exp/Cntr=0.3,0.1

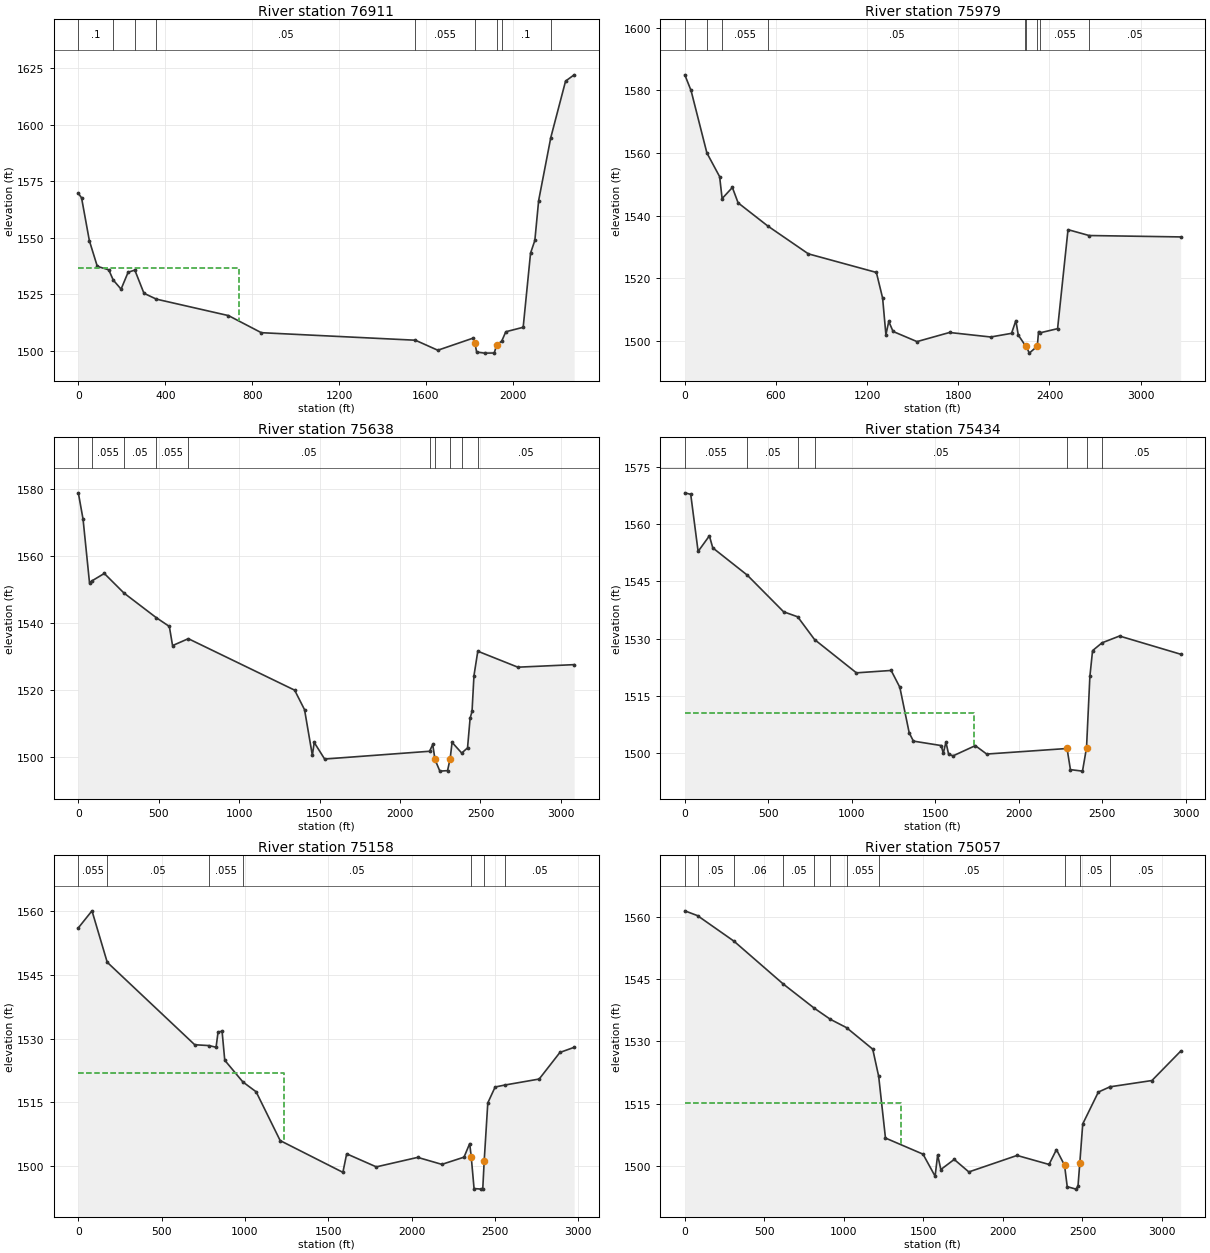
Type RM Length L Ch R = 1 ,76911   ,930.2,931.4,922.8
XS GIS Cut Line= 4
2478124.53765341607985.5926590282479793.95723535607717.890632527
2480128.58476847607665.8374607072480307.05278614607487.369443039
#Sta/Elev= 30
       0 1569.64    14.8 1567.68    50.8 1548.68    87.3 1537.33     140  1535.8
  160.611531.273   196.7 1527.24   229.1 1534.72  259.931535.679     302 1525.41
  359.24 1522.81   690.9 1515.53   842.2 1507.96 1551.041504.626  1654.3 1500.19
    1817 1505.56  1825.1 1503.22  1833.2 1499.37  1869.7 1498.91  1914.2 1498.97
  1925.3 1502.63 1948.311504.207  1967.3 1508.38  2047.2 1510.35  2081.1 1543.18
  2100.9 1548.81  2118.4 1566.47  2174.31594.371  2242.3 1619.36  2281.8 1622.13
#Mann= 9 ,-1 , 0
       0      .1       0  160.61    .055       0  259.93     .05       0
  359.24     .05       0 1551.04    .055       0  1825.1    .045       0
  1925.3    .055       0 1948.31      .1       0  2174.3      .1       0
#XS Ineff= 2 , 0
          738.21 1536.53
Permanent Ineff=
       F       F
Bank Sta=1825.1,1925.3
XS Rating Curve= 0 ,0
Exp/Cntr(USF)=0,0
Exp/Cntr=0.3,0.1

Type RM Length L Ch R = 1 ,75979   ,339.8,341.9,345.3
XS GIS Cut Line= 4
2478057.61214679608710.6189808032479318.04252156 608677.15622749
2480623.08990076 608491.252042422481039.51527532607948.411822014
#Sta/Elev= 30
       0 1584.92    41.1 1579.92  145.381559.981   229.2 1552.41   245.61545.413
   313.2 1548.96   350.8 1544.05  546.251536.656   813.4 1527.76  1260.9 1521.83
    1302 1513.64  1323.6 1501.93  1342.4 1506.19  1370.7 1502.99  1528.2 1499.75
  1742.4 1502.66  2013.3 1501.22  2150.5 1502.39  2178.8 1506.45  2194.9 1501.84
 2241.231498.481  2246.7 1498.28  2267.3 1496.07  2320.2  1498.3  2328.2 1502.94
 2340.561502.581  2453.5 1503.88  2522.2 1535.49 2660.791533.617  3263.3 1533.17
#Mann= 9 ,-1 , 0
       0     .05       0  145.38     .06       0   245.6    .055       0
  546.25     .05       0 2241.23      .1       0  2246.7    .045       0
  2320.2      .1       0 2340.56    .055       0 2660.79     .05       0
Bank Sta=2246.7,2320.2
XS Rating Curve= 0 ,0
Exp/Cntr(USF)=0,0
Exp/Cntr=0.3,0.1

Type RM Length L Ch R = 1 ,75638   ,195,204,212.6
XS GIS Cut Line= 4
2478061.33023049608970.8848399022479448.17545111608918.831668082
2480556.16439413608863.0604125612481058.10569382608561.895632747
#Sta/Elev= 30
       0 1578.86    29.4 1570.98    69.5    1552   83.381552.541   161.5 1554.79
  283.521548.952  483.671541.623   565.8 1538.97   585.8 1533.26  683.821535.318
  1344.8 1519.95  1406.4 1514.12    1455 1500.49  1466.5 1504.34  1531.3 1499.39
 2183.74 1501.71  2203.4 1503.75  2217.2 1499.28  2247.5 1495.78  2295.5 1495.93
  2311.6 1499.48  2323.6 1504.37 2383.591501.168  2419.7 1502.72  2435.7 1511.57
  2447.7 1513.62  2459.7 1524.28 2483.511531.578  2732.5 1526.81  3082.6 1527.57
#Mann= 10 ,-1 , 0
       0     .05       0   83.38    .055       0  283.52     .05       0
  483.67    .055       0  683.82     .05       0 2183.74      .1       0
  2217.2    .045       0  2311.6      .1       0 2383.59    .055       0
 2483.51     .05       0
Bank Sta=2217.2,2311.6
XS Rating Curve= 0 ,0
Exp/Cntr(USF)=0,0
Exp/Cntr=0.3,0.1

Type RM Length L Ch R = 1 ,75434   ,264.3,276,293.4
XS GIS Cut Line= 4
2477983.25047276609034.0922628262480028.19650853609048.964597631
2480526.41972452 609097.299685752480942.84509908609022.938011721
#Sta/Elev= 30
       0 1568.31    35.5 1567.91    79.7  1552.9   147.2    1557   167.5 1553.84
  373.831546.679   591.5 1537.04  676.031535.708  776.771529.736  1027.5 1520.98
  1235.5 1521.61  1287.5 1517.18  1343.5 1505.22  1368.7 1503.03  1535.5 1501.86
  1547.5 1499.81  1563.5 1502.77  1579.5 1499.59  1606.4 1499.16  1739.4 1501.84
  1807.5 1499.63  2288.7 1501.09  2308.8 1495.53  2381.1 1495.14  2405.2 1501.28
  2425.3 1520.03  2441.4 1526.82 2497.921528.873  2602.8 1530.66  2968.6 1525.88
#Mann= 7 ,-1 , 0
       0    .055       0  373.83     .05       0  676.03    .055       0
  776.77     .05       0  2288.7    .045       0  2405.2      .1       0
 2497.92     .05       0
#XS Ineff= 2 , 0
         1734.25 1510.52
Permanent Ineff=
       F       F
Bank Sta=2288.7,2405.2
XS Rating Curve= 0 ,0
Exp/Cntr(USF)=0,0
Exp/Cntr=0.5,0.3

Type RM Length L Ch R = 1 ,75158   ,106.6,100.4,94.8
XS GIS Cut Line= 4
2477901.45263133609145.6347738682480106.27626626609275.767703417
2480396.28679497609402.1825492652480764.05360813609141.433339285
#Sta/Elev= 30
       0  1556.1    81.9 1560.12  173.381547.986   698.5 1528.53  783.951528.333
   826.7 1527.94   838.7 1531.56   862.8 1531.69   878.8 1524.87  987.471519.759
  1067.1 1517.43  1211.4 1505.92  1587.8 1498.43  1610.5  1502.8  1788.3 1499.72
  2036.8 1501.96  2181.8 1500.31  2314.7 1502.01  2348.8 1505.21  2358.2 1502.05
    2375 1494.61  2418.6 1494.47  2427.3 1494.53 2435.881501.126  2457.5 1514.81
  2501.5 1518.56 2560.511519.029  2765.9 1520.44  2890.3 1526.71  2975.8 1527.92
#Mann= 7 ,-1 , 0
       0    .055       0  173.38     .05       0  783.95    .055       0
  987.47     .05       0  2358.2    .045       0 2435.88      .1       0
 2560.51     .05       0
#XS Ineff= 2 , 0
          1232.2 1521.89 2482.19         1508.64
Permanent Ineff=
       F       F
Bank Sta=2358.2,2435.88
XS Rating Curve= 0 ,0
Exp/Cntr(USF)=0,0
Exp/Cntr=0.5,0.3

Type RM Length L Ch R = 1 ,75057   ,306.8,317,326.1
XS GIS Cut Line= 4
2477793.62820399609320.3847078342480083.96776406609383.592130758
2480353.23138571609478.1764620382480782.26106402609149.111182129
#Sta/Elev= 30
       0 1561.42   79.861560.265  309.081554.115  619.771543.774  814.591537.961
   915.71535.289  1016.81533.292  1181.6 1528.11 1219.011521.549  1261.6 1506.71
  1497.7 1502.83  1573.7 1497.52  1589.7 1502.66  1609.7 1499.13  1693.8 1501.56
  1785.8 1498.55    2089 1502.52    2290 1500.35  2336.6 1503.93  2387.4 1500.18
  2404.4    1495  2459.5 1494.41  2472.2 1495.18 2483.351500.656  2501.9 1510.11
    2600 1517.78 2673.721519.056 2674.841519.055  2936.9 1520.56  3117.3 1527.62
#Mann= 12 ,-1 , 0
       0    .055       0   79.86     .05       0  309.08     .06       0
  619.77     .05       0  814.59    .055       0   915.7    .035       0
  1016.8    .055       0 1219.01     .05       0  2387.4    .045       0
 2483.35     .05       0 2673.72      .1       0 2674.84     .05       0
#XS Ineff= 2 , 0
         1357.06 1515.07
Permanent Ineff=
       F       F
Bank Sta=2387.4,2483.35
XS Rating Curve= 0 ,0
Exp/Cntr(USF)=0,0
Exp/Cntr=0.5,0.3

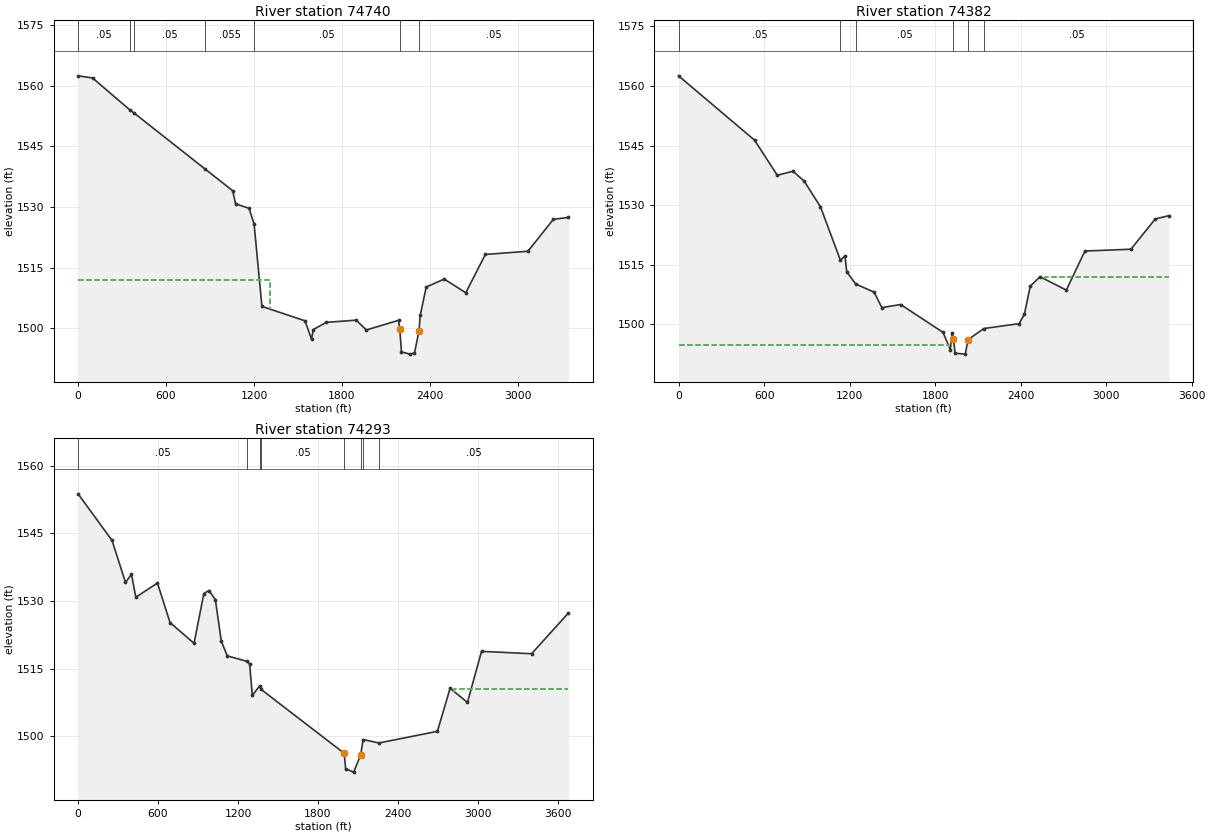
Type RM Length L Ch R = 1 ,74740   ,381.7,358,363
XS GIS Cut Line= 4
2477756.44736697609346.4112937442479838.57423976609528.597395113
2480095.12201516609718.2196638852480826.94871202609134.651554614
#Sta/Elev= 30
       0 1562.47    98.7 1561.94  355.361553.972  384.72 1553.18  867.611539.368
  1054.8 1534.02  1074.4 1530.77  1166.7 1529.66 1200.921525.723  1254.2 1505.37
  1548.2 1501.81  1592.4 1497.27  1604.4 1499.63  1693.6 1501.43  1896.7 1501.97
  1966.8 1499.54  2186.2 1501.93  2194.4 1499.83  2206.2 1494.11  2264.4 1493.56
  2294.9 1493.83 2325.621499.322    2334 1503.16    2375 1510.18  2497.8 1512.15
  2644.6 1508.76  2778.4 1518.24  3068.9 1519.03  3242.1 1526.94  3345.1 1527.41
#Mann= 7 ,-1 , 0
       0     .05       0  355.36     .06       0  384.72     .05       0
  867.61    .055       0 1200.92     .05       0  2194.4    .045       0
 2325.62     .05       0
#XS Ineff= 2 , 0
          1307.3    1512 2493.15         1511.99
Permanent Ineff=
       F       F
Bank Sta=2194.4,2325.62
XS Rating Curve= 0 ,0
Exp/Cntr(USF)=0,0
Exp/Cntr=0.5,0.3

Type RM Length L Ch R = 1 ,74382   ,72.9,89.2,76.2
XS GIS Cut Line= 4
2477749.97049221609409.1388160142479574.97049224609809.138816014
2479902.05382556609934.1388160292480829.02141815609137.854093805
#Sta/Elev= 30
       0 1562.55   533.1 1546.37   692.8 1537.53   803.4 1538.54   881.2 1536.06
   995.9 1529.59 1135.671516.142  1167.9 1517.25  1180.1 1513.24 1242.471510.166
  1372.1 1508.12  1426.2 1504.23  1558.9    1505  1855.8 1497.99  1906.5 1493.67
  1919.5 1497.88  1928.4  1496.3  1940.9 1492.74    2012 1492.52  2030.6 1496.15
  2142.31498.967  2389.2 1500.18    2426 1502.52    2468 1509.65  2536.1 1511.99
  2720.7 1508.63    2851 1518.46  3173.8 1518.92  3344.5 1526.523440.499 1527.37
#Mann= 6 ,-1 , 0
       0     .05       0 1135.67     .06       0 1242.47     .05       0
  1928.4    .045       0  2030.6      .1       0  2142.3     .05       0
#XS Ineff= 2 , 0
            1900 1494.83 2569.86         1511.99
Permanent Ineff=
       F       F
Bank Sta=1928.4,2030.6
XS Rating Curve= 0 ,0
Exp/Cntr(USF)=0,0
Exp/Cntr=0.5,0.3

Type RM Length L Ch R = 1 ,74293   ,445.9,435.5,421.1
XS GIS Cut Line= 4
2477630.03252113609472.8261396142479527.14063111 609860.11971879
2479960.47396442610056.6474965662480833.65133902609138.313749403
#Sta/Elev= 30
       0 1553.79   254.8 1543.44   355.9 1534.12   400.8 1535.92   433.5 1530.84
   595.7 1533.97   690.2 1525.19   870.3  1520.6   943.8 1531.65   982.2 1532.32
  1030.2 1530.29  1074.4 1521.12  1119.3 1517.81 1266.871516.585  1286.7 1516.09
  1307.6 1509.01 1362.331511.141 1373.071510.365  1997.3 1496.16  2007.5 1492.73
  2067.6 1491.99  2120.3  1495.8 2138.63 1499.23 2257.881498.464    2696 1501.05
  2791.2 1510.61  2921.4 1507.47  3027.1 1518.81  3402.5 1518.28  3679.2 1527.33
#Mann= 8 ,-1 , 0
       0     .05       0 1266.87     .06       0 1362.33    .055       0
 1373.07     .05       0  1997.3    .045       0  2120.3      .1       0
 2138.63      .1       0 2257.88     .05       0
#XS Ineff= 2 , 0
                         2821.92         1510.54
Permanent Ineff=
       F       F
Bank Sta=1997.3,2120.3
XS Rating Curve= 0 ,0
Exp/Cntr(USF)=0,0
Exp/Cntr=0.5,0.3