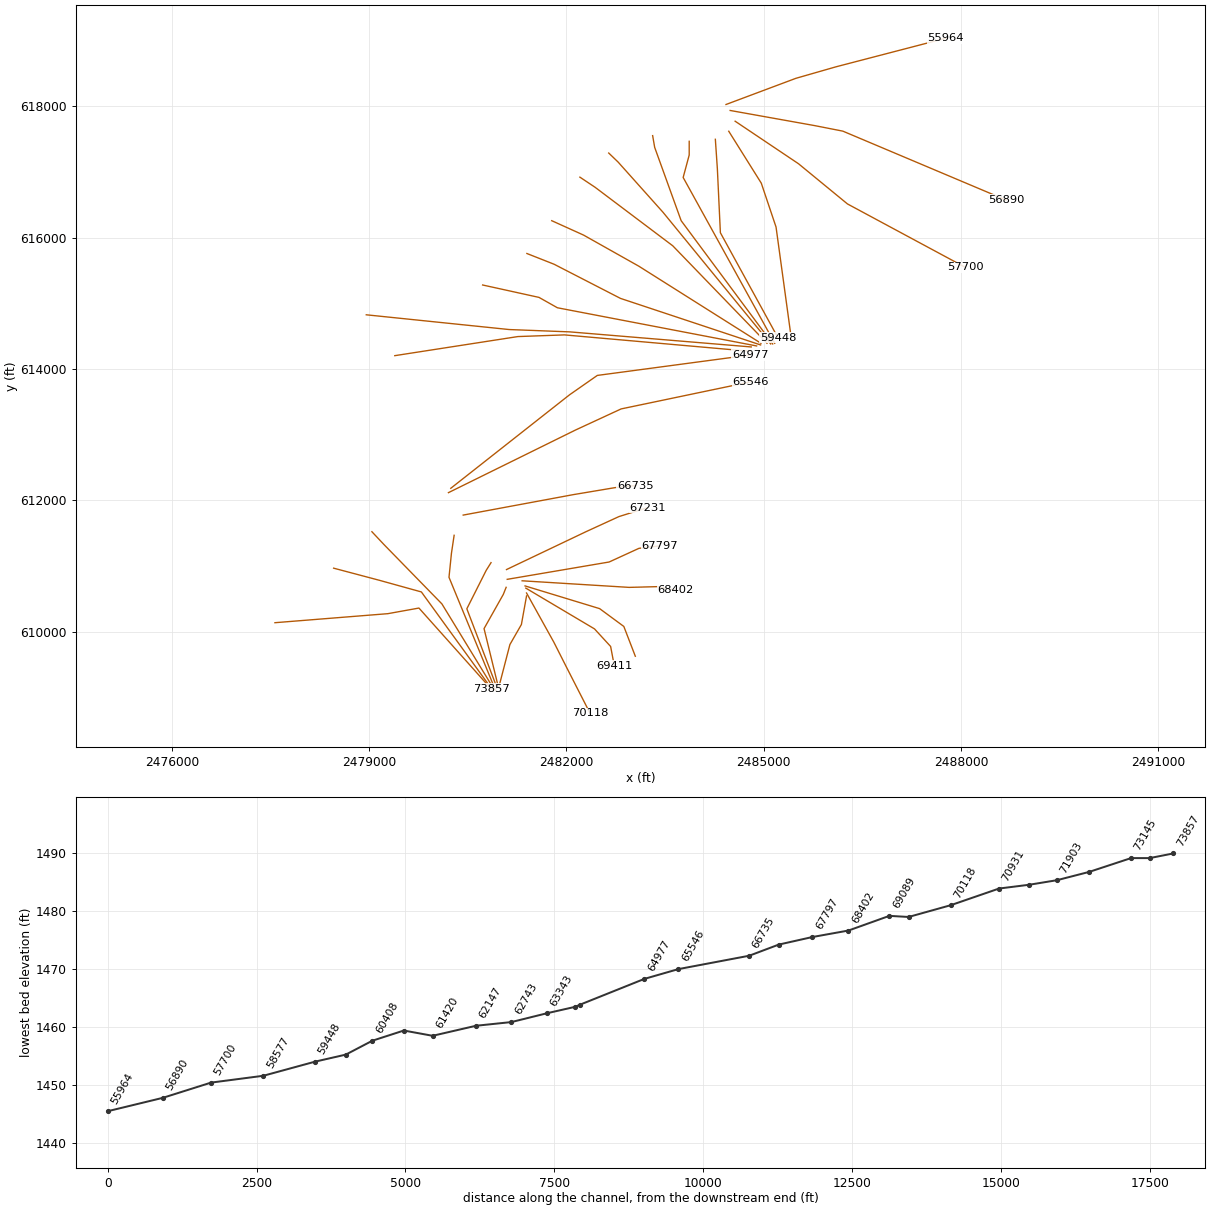
HEC-RAS study SFSBPOTOMC.prj: SFSBPOTOMC

--- SFSBPOTOMC.g01 (geometry) --- (continued)

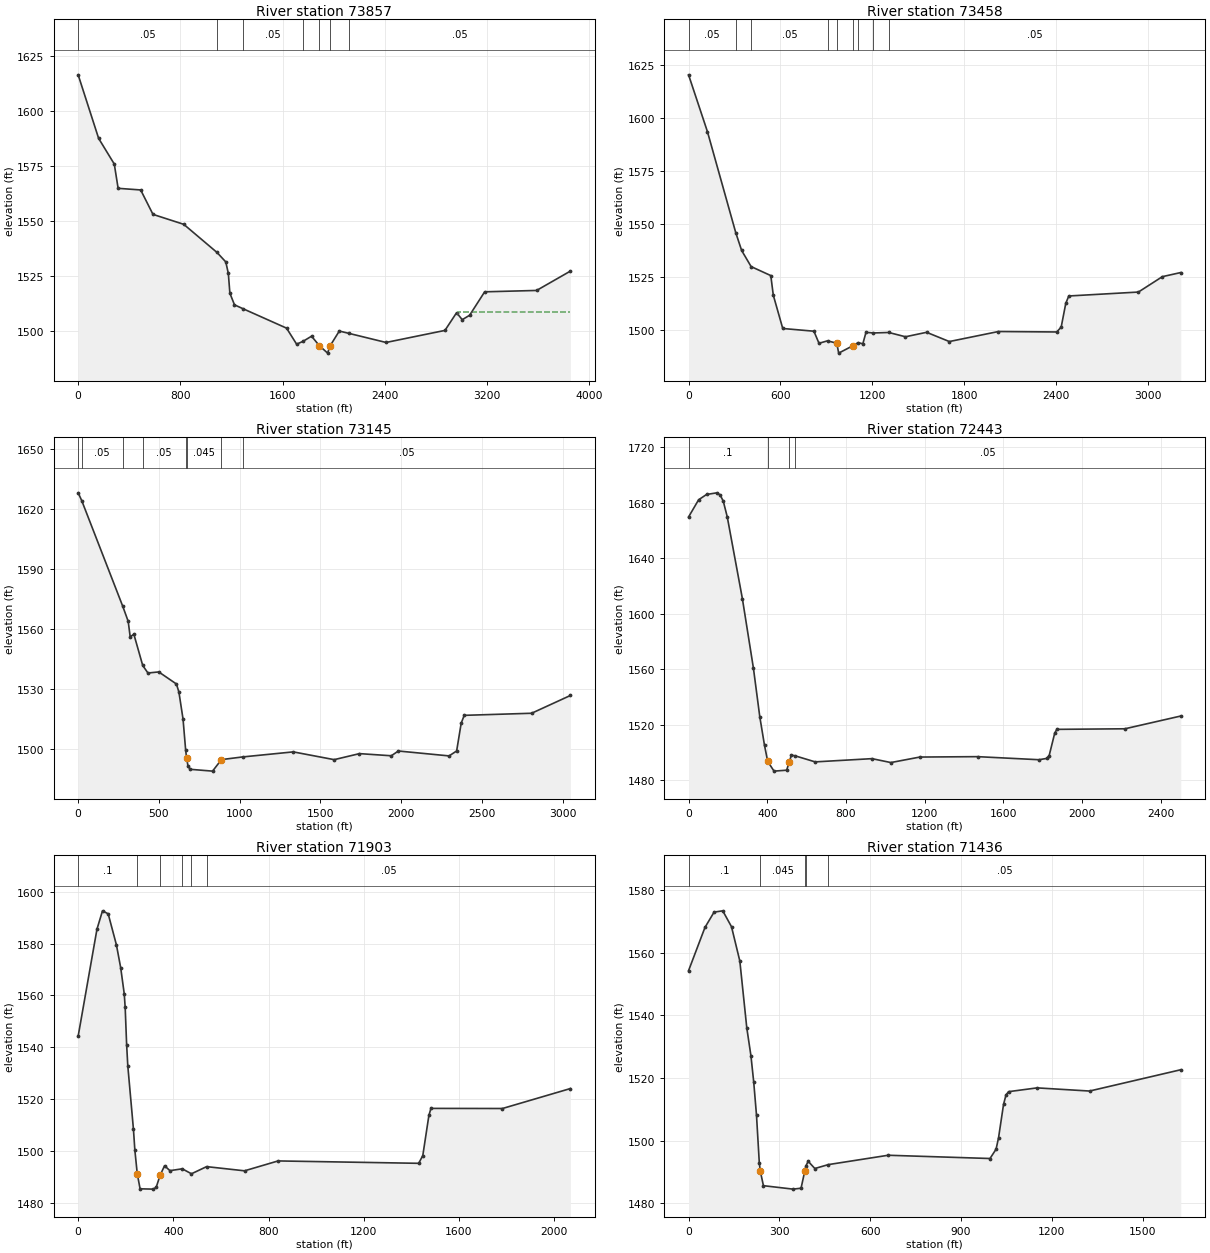
Type RM Length L Ch R = 1 ,73857   ,418.7,399.8,372
XS GIS Cut Line= 4
 2477566.8250982610138.3631221442479284.57976825610275.932219097
2479756.77639833610361.4481442292480855.50412015609130.073266667
#Sta/Elev= 30
       0 1616.27   160.4 1587.41   282.8 1575.77   312.9 1564.75   489.5 1564.01
   585.8 1552.92   826.6 1548.41    10871535.636  1155.6 1531.35  1175.7 1526.12
  1187.7 1517.15  1223.8 1511.86 1291.531510.074  1631.4 1501.28  1710.2 1494.01
 1759.361495.261  1827.1 1497.62  1888.1 1493.32  1953.1 1489.94  1969.4 1492.96
  2044.3 1499.97 2121.271498.884  2410.3 1494.78  2871.3 1500.25  2962.4 1508.28
  3006.7 1505.12  3064.3 1507.12  3182.2 1517.77  3588.8 1518.39  3853.4 1527.18
#Mann= 7 ,-1 , 0
       0     .05       0    1087     .06       0 1291.53     .05       0
 1759.36      .1       0  1888.1    .045       0  1969.4      .1       0
 2121.27     .05       0
#XS Ineff= 2 , 0
                         2975.34         1508.41
Permanent Ineff=
       F       F
Bank Sta=1888.1,1969.4
XS Rating Curve= 0 ,0
Exp/Cntr(USF)=0,0
Exp/Cntr=0.3,0.1

Type RM Length L Ch R = 1 ,73458   ,348.7,312.2,259.5
XS GIS Cut Line= 4
2478459.50576364610968.755278377  2479150.728755 610785.30968619
2479793.95723535610606.8416685222480869.52077041609122.307516725
#Sta/Elev= 30
       0 1620.27   123.4 1593.48   308.91545.752   346.8 1537.51   408.71529.907
   537.3 1525.67   553.6 1516.44   615.4 1500.74   818.9 1499.46   852.2 1493.77
  907.941494.924   968.4  1493.8   980.8 1489.13  1071.3 1492.53 1107.781494.068
  1138.6 1493.53  1159.3 1498.93  1207.71498.629 1307.621498.861  1417.2 1496.84
  1555.1 1498.94  1703.7 1494.59  2024.4 1499.31  2405.1  1499.1  2434.4 1501.38
  2464.4 1512.58  2484.1 1516.06  2938.8 1517.91  3095.3 1525.16  3215.9 1527.11
#Mann= 9 ,-1 , 0
       0     .05       0   308.9     .06       0   408.7     .05       0
  907.94      .1       0   968.4    .045       0  1071.3      .1       0
 1107.78    .025       0  1207.7      .1       0 1307.62     .05       0
Bank Sta=968.4,1071.3
XS Rating Curve= 0 ,0
Exp/Cntr(USF)=0,0
Exp/Cntr=0.3,0.1

Type RM Length L Ch R = 1 ,73145   ,767.7,702.1,586.8
XS GIS Cut Line= 4
  2479041.610993 611523.642017692479228.80851273611324.431822894
2480106.27626626610424.6555671532480895.85967535609129.814327718
#Sta/Elev= 30
       0 1628.11   21.881624.268  276.091571.439   309.8 1563.92     322 1556.23
   344.9 1557.46  399.661541.888     432 1538.13     499 1538.67   608.4 1532.63
   623.7 1528.58   649.2 1515.13  665.591499.444   671.4 1495.68   680.3 1491.45
   694.5 1490.03   831.9 1489.13   886.91494.884 1017.481496.211  1331.5 1498.74
  1584.8 1494.86  1741.3 1497.87  1938.3  1496.8    1982 1499.18  2295.9 1496.73
  2342.7  1499.2  2370.9 1513.09  2389.6 1516.99  2806.7 1518.03  3046.8 1526.91
#Mann= 8 ,-1 , 0
       0      .1       0   21.88     .05       0  276.09     .06       0
  399.66     .05       0  665.59      .1       0   671.4    .045       0
   886.9      .1       0 1017.48     .05       0
Bank Sta=671.4,886.9
XS Rating Curve= 0 ,0
Exp/Cntr(USF)=0,0
Exp/Cntr=0.3,0.1

Type RM Length L Ch R = 1 ,72443   ,558.4,540,520.3
XS GIS Cut Line= 4
2480292.18045133611469.4370872492480251.28153062611194.298893345
2480214.10069361610829.9266906072480920.53659687609112.172020555
#Sta/Elev= 30
       0 1669.87    51.1 1682.27    91.5  1686.1   144.1 1687.28   160.3 1685.79
   176.5 1681.26   196.7 1669.95   273.5 1611.07   329.8 1560.83     362 1525.95
   386.1 1505.25   402.2 1493.78   402.2 1493.75   434.4 1486.75   498.7 1487.43
   511.6 1493.33   522.8 1498.28  542.281497.751   643.5 1493.41   932.3 1495.74
  1028.3 1492.93  1175.4 1496.89  1468.6 1497.18  1780.9 1494.97  1819.8 1495.89
  1832.8 1497.97  1860.9 1514.07  1871.7 1516.85  2217.7 1517.26  2501.8 1526.46
#Mann= 4 ,-1 , 0
       0      .1       0   402.2    .045       0   511.6      .1       0
  542.28     .05       0
Bank Sta=402.2,511.6
XS Rating Curve= 0 ,0
Exp/Cntr(USF)=0,0
Exp/Cntr=0.3,0.1

Type RM Length L Ch R = 1 ,71903   ,451.7,467.1,472.9
XS GIS Cut Line= 4
2480853.61109025611053.0117126912480779.24941622610934.033034246
2480485.52080381610350.2938931252480939.68100985 609159.32847614
#Sta/Elev= 30
       0 1544.26    79.1 1585.54   102.3  1592.6   126.2 1591.44   160.9 1579.44
   178.8 1570.64   193.7  1560.6   197.6 1555.36   203.7 1541.02   208.6 1532.84
   232.4 1508.33   238.3 1500.31   248.31491.287   260.2 1485.44   315.8 1485.32
   327.7 1485.98   345.3 1490.89   363.2 1494.34   385.6 1492.44  437.311493.149
  476.171491.237  539.791493.992   699.1 1492.38   840.2 1496.19    1431 1495.27
  1448.2 1498.27  1473.8 1513.73  1482.4 1516.44  1782.9  1516.4  2068.4 1524.09
#Mann= 6 ,-1 , 0
       0      .1       0   248.3    .045       0   345.3      .1       0
  437.31     .05       0  476.17      .1       0  539.79     .05       0
Bank Sta=248.3,345.3
XS Rating Curve= 0 ,0
Exp/Cntr(USF)=0,0
Exp/Cntr=0.3,0.1

Type RM Length L Ch R = 1 ,71436   ,502,505.5,510
XS GIS Cut Line= 4
2481083.33660982610677.1989664042481039.96888153610568.779645671
2480747.23671555610048.3669061522480964.07535702609162.038959159
#Sta/Elev= 30
       0 1554.24    54.2 1568.04    84.3 1572.93     113 1573.34   141.9 1568.27
   169.4 1557.32   192.4 1535.97   206.1 1527.08   215.3  1518.7   224.5 1508.09
   233.7 1492.96  237.081490.231   247.4 1485.63   345.2 1484.53   371.7 1484.82
  383.84 1490.23  388.351492.039   395.2 1493.42   417.2 1491.11  461.881492.358
   659.5 1495.34   995.9  1494.3    1016 1497.27  1024.2 1500.94  1040.7 1511.59
  1048.9 1514.61  1057.2 1515.63  1151.4 1516.84  1324.8 1515.83  1626.3 1522.63
#Mann= 5 ,-1 , 0
       0      .1       0  237.08    .045       0  383.84      .1       0
  388.35    .025       0  461.88     .05       0
Bank Sta=237.08,383.84
XS Rating Curve= 0 ,0
Exp/Cntr(USF)=0,0
Exp/Cntr=0.3,0.1

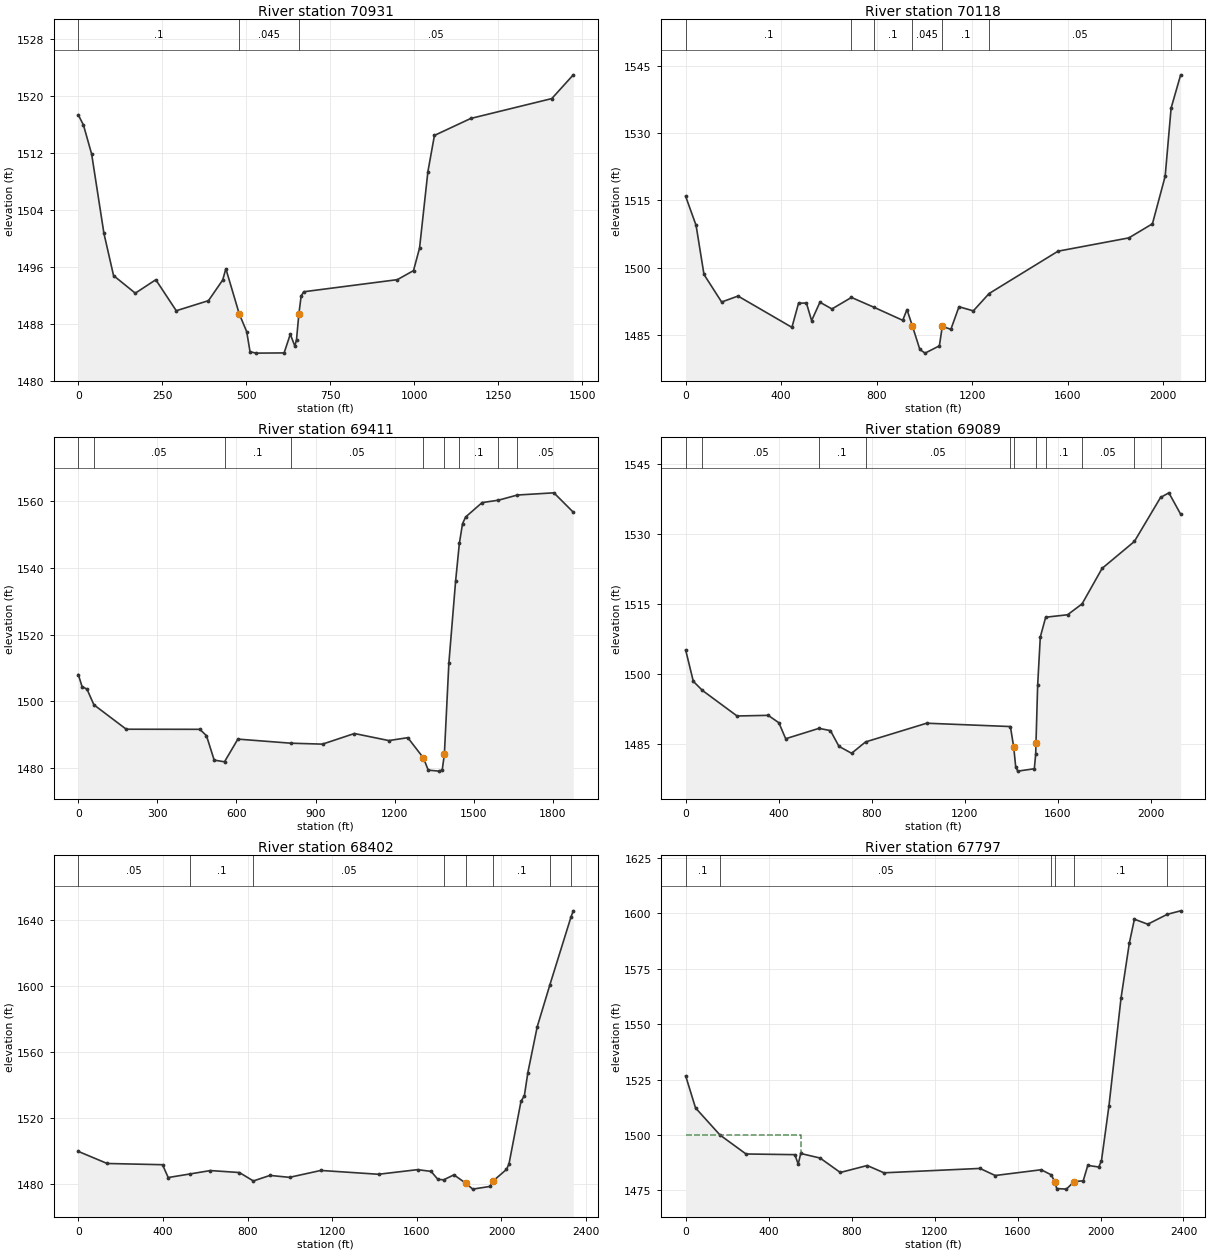
Type RM Length L Ch R = 1 ,70931   ,741.2,812.4,872.3
XS GIS Cut Line= 4
2481393.56791616610545.9508391932481315.48815843610110.935046128
2481140.73822446609806.052182613 2480969.7063742609147.951367463
#Sta/Elev= 30
       0 1517.38    15.3 1515.96    39.7 1511.88    76.3 1500.72     105 1494.78
   169.7 1492.31   230.7  1494.2   291.6 1489.84   387.5 1491.26   429.8 1494.16
   439.2 1495.75  479.071489.399   501.2  1486.9   511.2 1484.07   529.6 1483.88
   612.6 1483.91     631 1486.54   644.6 1484.86   649.5 1485.78  656.57  1489.4
   663.3 1491.92   671.1 1492.51   949.6 1494.21   997.7 1495.48  1015.7 1498.65
  1040.5 1509.38    1060 1514.49  1168.3 1516.88  1409.3 1519.67  1473.3 1523.01
#Mann= 3 ,-1 , 0
       0      .1       0  479.07    .045       0  656.57     .05       0
Bank Sta=479.07,656.57
XS Rating Curve= 0 ,0
Exp/Cntr(USF)=0,0
Exp/Cntr=0.3,0.1

Type RM Length L Ch R = 1 ,70118   ,695.9,707.4,711.7
XS GIS Cut Line= 4
2481393.56791616 610590.567843612481809.99329072609839.514935926
2481995.89747579609471.4246494862482360.26967853608757.552578815
#Sta/Elev= 30
       0  1515.9    43.7 1509.44    76.7 1498.52   150.6 1492.38   219.2 1493.71
   444.9 1486.74   472.6 1492.11   505.6 1492.17   527.3 1488.24   562.2 1492.33
   612.5 1490.84  694.141493.403  788.43 1491.21   908.8 1488.31   926.7 1490.69
     949 1487.09   980.5 1481.82  1002.4    1481  1062.3 1482.62  1074.6 1486.98
  1110.4 1486.29  1144.4 1491.33  1204.5 1490.41 1270.371494.266  1559.1  1503.7
  1855.6 1506.66  1954.4  1509.8  2007.7 1520.38 2032.621535.575  2072.6 1542.97
#Mann= 7 ,-1 , 0
       0      .1       0  694.14     .05       0  788.43      .1       0
     949    .045       0  1074.6      .1       0 1270.37     .05       0
 2032.62      .1       0
Bank Sta=949,1074.6
XS Rating Curve= 0 ,0
Exp/Cntr(USF)=0,0
Exp/Cntr=0.3,0.1

Type RM Length L Ch R = 1 ,69411   ,312.5,322.5,330
XS GIS Cut Line= 4
2481382.41366506610664.9295176392482427.19518515610044.009539503
2482672.58870945609776.3075130022482728.35996497 609482.57890059
#Sta/Elev= 30
       0 1507.99    14.3 1504.37      33  1503.6   59.191498.897   181.9 1491.56
     461 1491.53   486.2 1489.62   515.4 1482.28  554.561481.774   605.3 1488.59
  806.46 1487.36   926.3 1487.08  1047.3 1490.27  1177.9 1488.15  1249.8 1489.02
  1309.3 1482.91  1327.2 1479.27  1368.6 1478.97  1380.4 1479.34  1388.5 1484.02
  1405.5 1511.35    1431 1535.96 1445.361547.392  1457.4 1553.32  1469.2 1555.33
  1531.6 1559.64 1593.741560.373 1665.581561.922  1803.9 1562.58  1877.5 1556.76
#Mann= 9 ,-1 , 0
       0      .1       0   59.19     .05       0  554.56      .1       0
  806.46     .05       0  1309.3    .045       0  1388.5      .1       0
 1445.36      .1       0 1593.74      .1       0 1665.58     .05       0
Bank Sta=1309.3,1388.5
XS Rating Curve= 0 ,0
Exp/Cntr(USF)=0,0
Exp/Cntr=0.3,0.1

Type RM Length L Ch R = 1 ,69089   ,665.2,686.3,752.4
XS GIS Cut Line= 4
2481371.25941395610698.3922709512482505.27494288 610352.61048672
2482873.36522932610081.1903765172483048.11516329609627.584164945
#Sta/Elev= 30
       0 1505.14    32.9 1498.43   72.091496.474   221.1 1490.99   354.9 1491.13
   400.9 1489.54   430.2 1486.11  573.241488.334   622.6 1487.86   659.3 1484.48
   713.8 1482.99   773.71485.425  1036.6 1489.44 1396.691488.723  1410.9 1484.31
  1419.5  1480.1  1428.1 1479.16  1499.6 1479.67  1505.5 1482.83 1506.74  1485.2
  1513.9 1497.55  1525.3 1507.94 1548.481512.179  1642.7 1512.71 1704.981515.046
  1791.1 1522.66 1929.991528.437 2042.491537.874  2078.3 1538.87    2129 1534.28
#Mann= 11 ,-1 , 0
       0      .1       0   72.09     .05       0  573.24      .1       0
   773.7     .05       0 1396.69      .1       0  1410.9    .045       0
 1506.74      .1       0 1548.48      .1       0 1704.98     .05       0
 1929.99      .1       0 2042.49     .05       0
Bank Sta=1410.9,1506.74
XS Rating Curve= 0 ,0
Exp/Cntr(USF)=0,0
Exp/Cntr=0.3,0.1

Type RM Length L Ch R = 1 ,68402   ,587.1,605.2,641.3
XS GIS Cut Line= 4
2481326.64240954610776.4720286812482955.16307075610676.083768743
2483379.02461271610687.2380198472483657.88089032610635.184848027
#Sta/Elev= 30
       0 1499.53   136.4 1492.19     398 1491.45   424.9 1483.67  527.821485.836
   624.4  1487.9   761.5  1486.7  827.241481.587   905.8 1484.95   998.2 1483.78
  1146.3 1487.97  1418.8 1485.65  1603.1 1488.45  1667.2  1487.4  1699.2 1482.58
 1726.691482.277  1775.2  1485.3  1832.8 1480.07    1864 1476.63  1947.3  1478.3
  1959.3 1481.47  2023.3 1488.55  2035.3 1491.85    2092 1529.84  2108.2 1533.41
  2124.5 1547.32  2168.8 1575.16 2229.061600.788  2328.41641.789  2339.3 1645.53
#Mann= 8 ,-1 , 0
       0     .05       0  527.82      .1       0  827.24     .05       0
 1726.69      .1       0  1832.8    .045       0  1959.3      .1       0
 2229.06      .1       0  2328.4      .1       0
Bank Sta=1832.8,1959.3
XS Rating Curve= 0 ,0
Exp/Cntr(USF)=0,0
Exp/Cntr=0.3,0.1

Type RM Length L Ch R = 1 ,67797   ,566.4,566.5,566.6
XS GIS Cut Line= 4
2481099.83930375610798.7805308892482650.28020724611062.764473689
2483103.88641881611270.9771609682483416.20544973611308.157997983
#Sta/Elev= 30
       0 1526.66    47.6 1512.18  165.691499.933     291 1491.38   526.2 1491.08
   542.6 1486.83   554.8  1491.6   648.1 1489.55   745.5 1483.03   875.3 1486.17
   956.1 1482.88    1419 1484.86  1492.1 1481.66  1714.1 1484.26 1763.411481.912
  1780.1 1478.58  1788.9 1475.78  1835.6 1475.51  1872.6 1478.94  1916.6 1479.26
  1938.6 1486.23  1991.4  1485.5  2004.6 1488.34  2040.8 1513.18  2098.9 1561.79
  2139.2 1586.75  2163.4 1597.39  2227.8 1595.14 2322.011599.612  2386.4 1601.18
#Mann= 6 ,-1 , 0
       0      .1       0  165.69     .05       0 1763.41      .1       0
  1780.1    .045       0  1872.6      .1       0 2322.01      .1       0
#XS Ineff= 2 , 0
           554.8    1500
Permanent Ineff=
       F       F
Bank Sta=1780.1,1872.6
XS Rating Curve= 0 ,0
Exp/Cntr(USF)=0,0
Exp/Cntr=0.3,0.1

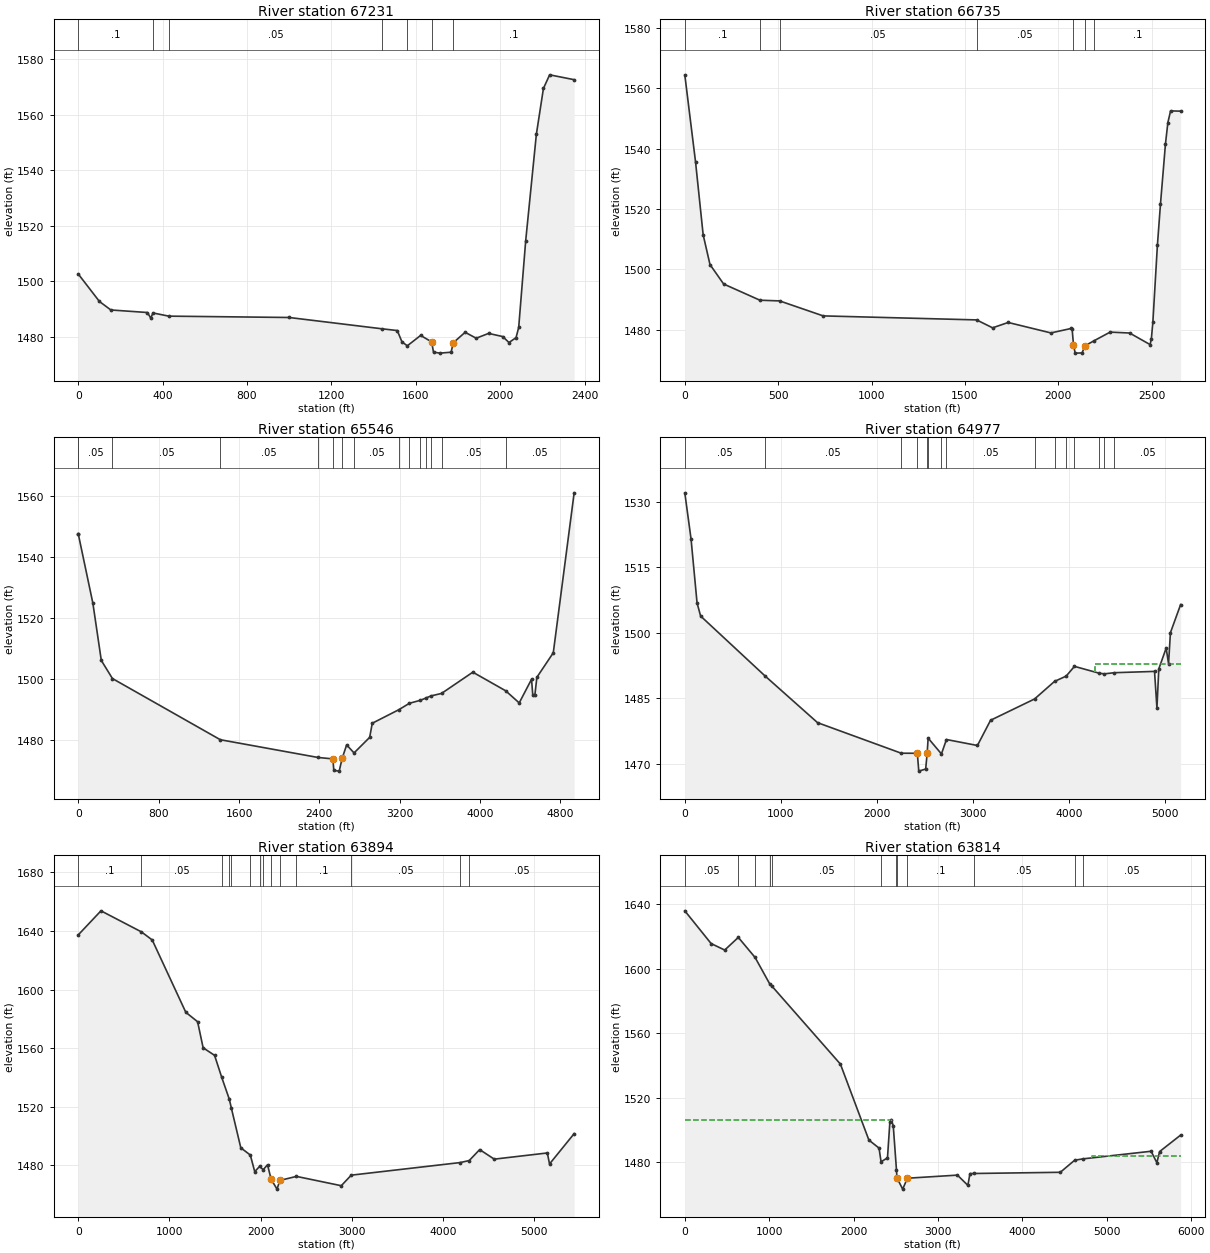
Type RM Length L Ch R = 1 ,67231   ,505.6,495.2,481.7
XS GIS Cut Line= 4
2481088.68505265610947.503878946 2482297.0622556611523.806852664
2482799.00355529611754.3280421522483237.73743206611891.897139104
#Sta/Elev= 30
       0 1502.65   100.1 1492.79   154.1 1489.74   327.6 1488.82   343.5  1486.8
  353.881488.669  428.741487.516   999.4 1487.03 1440.171482.955  1512.3 1482.33
  1534.3 1478.28 1559.791476.832  1622.9 1480.57  1675.1 1478.26    1684 1474.55
  1714.8  1474.2  1767.6 1474.53  1777.5 1477.93    1834  1481.7  1886.4 1479.57
  1945.3  1481.3  2012.4 1480.16  2041.8 1478.01  2075.3 1479.77  2087.9 1483.43
  2121.1 1514.64  2171.7 1552.98  2205.2 1569.48  2234.6 1574.39  2350.9 1572.64
#Mann= 7 ,-1 , 0
       0      .1       0  353.88     .05       0  428.74     .05       0
 1440.17     .05       0 1559.79      .1       0  1675.1    .045       0
  1777.5      .1       0
Bank Sta=1675.1,1777.5
XS Rating Curve= 0 ,0
Exp/Cntr(USF)=0,0
Exp/Cntr=0.3,0.1

Type RM Length L Ch R = 1 ,66735   ,1169.8,1189.3,1197.1
XS GIS Cut Line= 4
2480430.07931255611777.0649655272482102.96196558612088.180336976
2482740.49346445612195.2856287862483046.50858391612225.887140732
#Sta/Elev= 30
       0 1564.43    57.6 1535.56    98.3 1511.48   134.9 1501.61     208 1495.17
  402.231489.802  507.751489.572   741.2 1484.61 1562.94 1483.28  1648.5 1480.66
  1732.1 1482.43  1960.9 1478.97  2070.4 1480.46  2074.5 1480.29 2081.78 1475.05
  2090.7 1472.28  2127.2 1472.34  2144.8 1474.75 2193.061476.418  2278.1 1479.24
  2382.3 1478.94  2492.3  1475.1    2499 1477.12  2506.9 1482.49  2531.2 1507.97
  2547.5  1521.5  2574.3 1541.49  2587.3 1548.63  2601.9 1552.49  2655.6  1552.4
#Mann= 7 ,-1 , 0
       0      .1       0  402.23     .05       0  507.75     .05       0
 1562.94     .05       0 2081.78    .045       0  2144.8     .05       0
 2193.06      .1       0
Bank Sta=2081.78,2144.8
XS Rating Curve= 0 ,0
Exp/Cntr(USF)=0,0
Exp/Cntr=0.3,0.1

Type RM Length L Ch R = 1 ,65546   ,558.5,568.7,576.7
XS GIS Cut Line= 4
2480205.66822495612118.7818489222482138.66372952613072.528971231
2482832.29800029613393.8448466612484806.09552079613806.965257929
#Sta/Elev= 30
       0 1547.44     .161547.415   144.9 1524.86   228.7 1506.17   339.51500.248
 1413.761480.237  2385.41474.441  2534.7 1473.97  2543.5 1470.21  2597.2 1469.97
  2627.1  1474.2  2671.3 1478.54 2745.071475.921  2900.6 1481.01  2926.5 1485.63
 3190.351490.049 3296.761492.159 3403.161493.119  3459.4 1493.85 3509.561494.554
 3615.971495.377  3927.7 1502.33 4254.391496.249  4389.5 1492.28  4512.1    1500
  4524.4 1494.88  4544.8 1494.71  4565.3 1500.65  4728.7 1508.67  4936.5 1560.98
#Mann= 15 ,-1 , 0
       0      .1       0     .16     .05       0   339.5     .05       0
 1413.76     .05       0  2385.4      .1       0  2534.7    .045       0
  2627.1     .06       0 2745.07     .05       0 3190.35    .055       0
 3296.76     .05       0 3403.16     .05       0  3459.4     .05       0
 3509.56     .05       0 3615.97     .05       0 4254.39     .05       0
Bank Sta=2534.7,2627.1
XS Rating Curve= 0 ,0
Exp/Cntr(USF)=0,0
Exp/Cntr=0.3,0.1

Type RM Length L Ch R = 1 ,64977   ,1111.4,1082.9,1055.9
XS GIS Cut Line= 4
2480241.36998888612185.0851248042482046.85919368613608.055430282
2482470.18010893613903.8700457582484795.89501681614214.985417206
#Sta/Elev= 30
       0 1532.03    64.9  1521.5   127.6 1506.81   164.7 1503.81  835.621490.083
    1382 1479.39 2253.76 1472.39  2420.7 1472.38  2435.8 1468.29  2507.6 1468.77
  2523.2 1472.41  2533.21475.843 2671.631472.233    2724 1475.53  3046.3 1474.16
  3183.1 1479.94 3641.44 1484.82 3848.951488.836 3970.311490.055 4056.471492.283
 4314.821490.712 4367.751490.568 4471.511490.832  4890.1 1491.13    4915 1482.74
  4934.5  1491.7  5011.1 1496.46    5036 1492.92  5055.6    1500  5161.7 1506.44
#Mann= 15 ,-1 , 0
       0     .05       0  835.62     .05       0 2253.76      .1       0
  2420.7    .045       0  2523.2      .1       0  2533.2     .06       0
 2671.63      .1       0    2724     .05       0 3641.44     .06       0
 3848.95     .05       0 3970.31    .035       0 4056.47     .02       0
 4314.82    .035       0 4367.75    .055       0 4471.51     .05       0
#XS Ineff= 2 , 0
                         4265.75         1492.77
Permanent Ineff=
       F       F
Bank Sta=2420.7,2523.2
XS Rating Curve= 0 ,0
Exp/Cntr(USF)=0,0
Exp/Cntr=0.5,0.3

Type RM Length L Ch R = 1 ,63894   ,89.9,80.9,78
XS GIS Cut Line= 4
2479389.62790639614204.7849132242481261.42038707614495.499276709
2481970.35541382614521.0005366632484795.89501681614271.088189106
#Sta/Elev= 30
       0 1637.38   248.3 1653.75  691.521639.406   810.7 1633.87  1179.1 1584.51
  1308.6 1578.07  1369.3 1560.29  1494.8 1555.12 1573.531540.075 1656.291525.233
 1677.981519.407  1782.7 1492.02 1886.881487.103  1935.6 1475.75 1988.371479.294
 2028.571477.114  2075.7 1480.44 2115.431470.589  2179.7 1463.83  2211.8 1469.79
 2393.441472.518  2885.1 1466.16 2994.41 1473.36 4189.321481.957  4288.91483.326
  4403.5 1490.81  4563.6 1484.29  5145.9 1488.51    5170    1481  5440.2 1501.71
#Mann= 14 ,-1 , 0
       0      .1       0  691.52     .05       0 1573.53      .1       0
 1656.29     .05       0 1677.98      .1       0 1886.88     .06       0
 1988.37      .1       0 2028.57     .06       0 2115.43    .045       0
  2211.8     .06       0 2393.44      .1       0 2994.41     .05       0
 4189.32     .06       0  4288.9     .05       0
#XS Ineff= 2 , 0
            2075 1476.36 4405.48         1490.59
Permanent Ineff=
       F       F
Bank Sta=2115.43,2211.8
XS Rating Curve= 0 ,0
Exp/Cntr(USF)=0,0
Exp/Cntr=0.5,0.3

Type RM Length L Ch R = 1 ,63814   ,514,470.5,452.4
XS GIS Cut Line= 4
2478956.10648716614827.0156561212481128.81383531614602.604568519
2482051.95944567614566.9028045822484811.19577278614337.391464989
#Sta/Elev= 30
       0  1635.7   312.3 1615.43   473.1 1611.43  634.371619.254  833.331606.823
 1007.97 1590.34 1032.291589.112  1844.4 1540.84  2182.1 1493.82  2302.3 1488.86
 2326.371480.342  2402.4 1482.85  2430.4 1504.74  2448.9 1506.52    2471 1502.57
 2509.231475.072 2514.841470.392  2582.5 1463.46  2638.5 1470.21  3231.3 1472.13
  3355.3 1465.79  3379.8 1473.06 3425.611473.133  4450.8 1473.88 4621.011481.352
 4720.621482.195  5527.2  1486.9  5595.4 1479.78  5627.6 1486.69  5876.9  1496.9
#Mann= 12 ,-1 , 0
       0     .05       0  634.37      .1       0  833.33     .05       0
 1007.97      .1       0 1032.29     .05       0 2326.37     .06       0
 2509.23      .1       0 2514.84    .045       0  2638.5      .1       0
 3425.61     .05       0 4621.01     .06       0 4720.62     .05       0
#XS Ineff= 2 , 0
         2457.53 1506.49 4824.66         1484.24
Permanent Ineff=
       F       F
Bank Sta=2514.84,2638.5
XS Rating Curve= 0 ,0
Exp/Cntr(USF)=0,0
Exp/Cntr=0.5,0.3

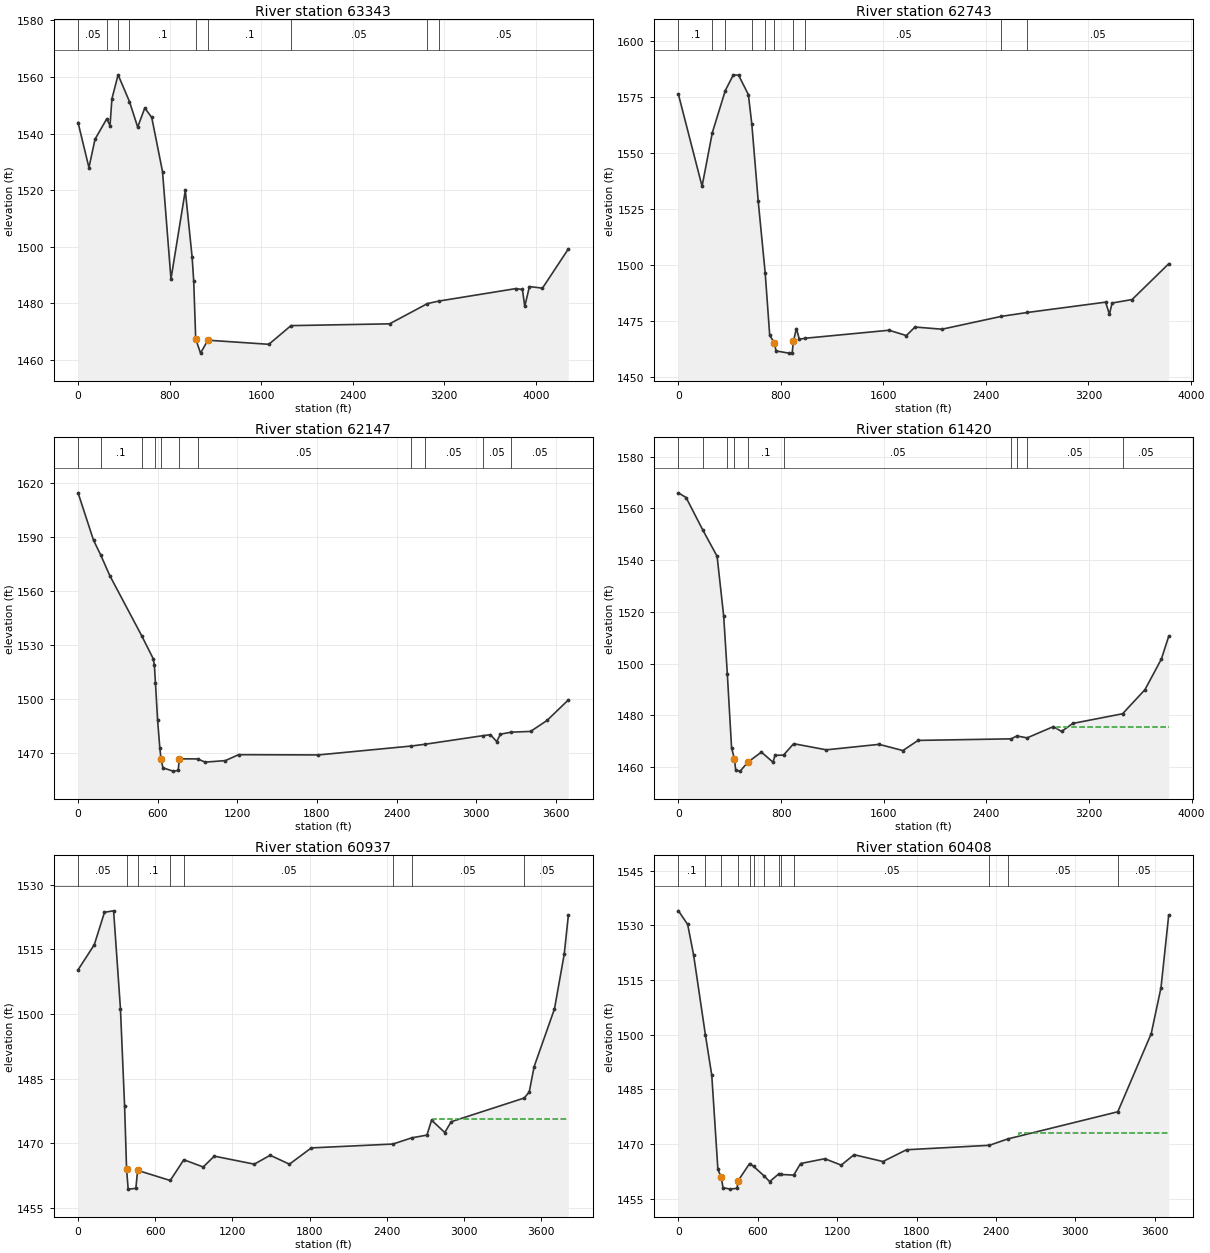
Type RM Length L Ch R = 1 ,63343   ,574.5,600,590.3
XS GIS Cut Line= 4
2480725.89392802615280.9380833172481582.73626251615092.228759651
2481863.25012201614934.1209479312484892.79980464614352.692220962
#Sta/Elev= 30
       0  1543.9    95.1 1527.96   148.3    1538  250.481545.187   279.4 1542.81
   295.8 1552.29  349.951560.765  449.421551.291     521 1542.28   583.1 1549.05
   643.9 1545.68   738.1 1526.54   811.9 1488.55   937.1 1519.87   996.8 1496.28
  1010.7  1487.8  1028.1 1467.34  1070.2 1462.36  1134.5 1466.93  1667.3 1465.48
 1860.591472.083  2722.4 1472.72 3052.871479.881 3152.231480.762    3826 1485.18
    3883 1484.86  3903.3 1478.86  3944.1 1485.89  4058.1 1485.34  4284.2  1499.2
#Mann= 9 ,-1 , 0
       0     .05       0  250.48    .055       0  349.95      .1       0
  449.42      .1       0  1028.1    .045       0  1134.5      .1       0
 1860.59     .05       0 3052.87     .06       0 3152.23     .05       0
#XS Ineff= 2 , 0
                         3760.27         1484.35
Permanent Ineff=
       F       F
Bank Sta=1028.1,1134.5
XS Rating Curve= 0 ,0
Exp/Cntr(USF)=0,0
Exp/Cntr=0.3,0.1

Type RM Length L Ch R = 1 ,62743   ,597.2,595.6,592.3
XS GIS Cut Line= 4
2481399.12719083615760.361770467 2481812.2476021615597.153706756
2482822.09749631615076.9280036782484954.00282853614367.992976935
#Sta/Elev= 30
       0 1576.04   184.5 1535.12  264.271558.963  365.931577.772   428.6 1584.76
   469.5  1584.6     546 1575.93   572.71562.884   622.9  1528.4  677.151496.575
   712.5 1468.74   748.5 1465.46     762 1461.81     861 1460.83     888    1461
     897 1466.02   920.8 1471.74   943.7 1467.02  990.511467.463  1644.1 1471.02
    1779 1468.65  1846.4 1472.45  2057.2 1471.48 2521.321477.211 2722.531478.922
  3334.4 1483.53  3363.9 1478.13    3385 1483.15    3541 1484.69  3826.9 1500.63
#Mann= 10 ,-1 , 0
       0      .1       0  264.27      .1       0  365.93     .12       0
   572.7      .1       0  677.15      .1       0   748.5    .045       0
     897      .1       0  990.51     .05       0 2521.32     .06       0
 2722.53     .05       0
Bank Sta=748.5,897
XS Rating Curve= 0 ,0
Exp/Cntr(USF)=0,0
Exp/Cntr=0.3,0.1

Type RM Length L Ch R = 1 ,62147   ,721.7,727.2,712
XS GIS Cut Line= 4
2481776.54583816616260.186465581 2482261.0697773616040.875629969
2483102.61135581 615566.552194812484959.10308052 614393.49423689
#Sta/Elev= 30
       0  1614.7   116.6 1588.38  170.131580.276   239.5 1568.68  478.791535.448
   565.9 1522.67   575.1  1519.1   583.11509.226   599.1 1488.63   616.4 1472.79
  625.181466.908   639.4 1462.04   715.1 1460.19   754.2 1460.54   763.4 1467.02
  900.571466.976   957.4 1465.19  1109.8 1466.03  1209.9 1469.32  1810.3 1469.18
 2507.851474.104 2615.811475.125 3047.631479.854  3106.8 1480.43  3154.1 1476.62
  3182.1  1480.7 3263.541481.821  3409.6 1482.24    3534 1488.36  3693.9 1499.73
#Mann= 11 ,-1 , 0
       0      .1       0  170.13      .1       0  478.79     .12       0
   583.1      .1       0  625.18    .045       0   763.4      .1       0
  900.57     .05       0 2507.85     .06       0 2615.81     .05       0
 3047.63     .05       0 3263.54     .05       0
Bank Sta=625.18,763.4
XS Rating Curve= 0 ,0
Exp/Cntr(USF)=0,0
Exp/Cntr=0.3,0.1

Type RM Length L Ch R = 1 ,61420   ,488.2,483.2,468.5
XS GIS Cut Line= 4
 2482204.9670054616923.219224405  2482434.478345616770.211664677
 2483617.7368069615877.6675662592485050.90761636 614393.49423689
#Sta/Elev= 30
       0    1566    59.8 1564.17  190.391551.585   301.3 1541.49   352.7  1518.4
  380.961496.108   414.2 1467.41   436.5  1463.2   446.5 1458.73   481.2 1458.46
   541.7 1461.95   646.7 1465.81   737.1 1461.91   752.5 1464.55  818.981464.661
   898.2 1469.06  1152.3 1466.69  1563.8 1468.81  1749.3 1466.41  1867.5 1470.33
 2593.541470.939 2637.721472.055 2717.561471.314  2922.6 1475.67    2986 1473.79
  3073.2 1476.89 3461.681480.634  3635.7 1489.93  3763.5 1501.72  3821.2 1510.57
#Mann= 10 ,-1 , 0
       0      .1       0  190.39      .1       0  380.96      .1       0
   436.5    .045       0   541.7      .1       0  818.98     .05       0
 2593.54     .06       0 2637.72    .055       0 2717.56     .05       0
 3461.68     .05       0
#XS Ineff= 2 , 0
                         2953.42         1475.65
Permanent Ineff=
       F       F
Bank Sta=436.5,541.7
XS Rating Curve= 0 ,0
Exp/Cntr(USF)=0,0
Exp/Cntr=0.3,0.1

Type RM Length L Ch R = 1 ,60937   ,540.3,528.7,502.1
XS GIS Cut Line= 4
2482643.58867662617290.4373677542482786.39573237617152.730563999
2483469.82949916616387.6927653552485107.01038826614383.293732908
#Sta/Elev= 30
       0 1510.22   126.1 1516.03   205.6 1523.57   276.4  1523.9   329.6 1501.23
   361.8 1478.71  377.39 1463.98   389.7 1459.37   449.2 1459.54   463.4 1463.72
  716.681461.371  822.391466.184   973.2  1464.5    1059 1467.02  1370.4 1465.16
  1493.8 1467.22  1643.6 1465.16  1813.9 1468.93 2448.031469.821 2593.981471.256
  2712.7  1471.9  2748.9 1475.36  2851.5  1472.5  2901.3    1475  3469.71480.498
  3508.2 1481.91  3546.3 1487.77  3704.4 1501.16  3780.2 1513.84  3812.3 1522.83
#Mann= 8 ,-1 , 0
       0     .05       0  377.39    .045       0   463.4      .1       0
  716.68     .05       0  822.39     .05       0 2448.03     .06       0
 2593.98     .05       0  3469.7     .05       0
#XS Ineff= 2 , 0
                         2756.16         1475.54
Permanent Ineff=
       F       F
Bank Sta=377.39,463.4
XS Rating Curve= 0 ,0
Exp/Cntr(USF)=0,0
Exp/Cntr=0.3,0.1

Type RM Length L Ch R = 1 ,60408   ,468.6,446.4,385.4
XS GIS Cut Line= 4
2483311.72168744617555.6504712842483342.32319939617377.141651601
2483745.24310667616260.186465581 2485137.6119002614383.293732908
#Sta/Elev= 30
       0 1534.01    69.8 1530.28   114.4 1521.96  204.341499.828     252 1488.86
   298.3 1463.03   323.8 1460.84   336.6 1458.02   391.9 1457.61   442.9 1457.85
   451.4 1459.92   537.81464.643  567.94 1463.85  648.951461.195   689.5 1459.68
  760.111461.853   772.51461.634  871.261461.463   923.4 1464.64  1106.3 1465.96
  1230.1  1464.2  1327.4 1467.06  1545.6 1465.19  1723.7 1468.42 2350.571469.641
 2489.151471.392 3320.641478.847  3573.1 1500.29    3647  1512.9  3705.5 1532.87
#Mann= 13 ,-1 , 0
       0      .1       0  204.34      .1       0   323.8    .045       0
   451.4      .1       0   537.8      .1       0  567.94      .1       0
  648.95     .05       0  760.11     .05       0   772.5     .05       0
  871.26     .05       0 2350.57     .06       0 2489.15     .05       0
 3320.64     .05       0
#XS Ineff= 2 , 0
                         2575.34         1473.03
Permanent Ineff=
       F       F
Bank Sta=323.8,451.4
XS Rating Curve= 0 ,0
Exp/Cntr(USF)=0,0
Exp/Cntr=0.3,0.1

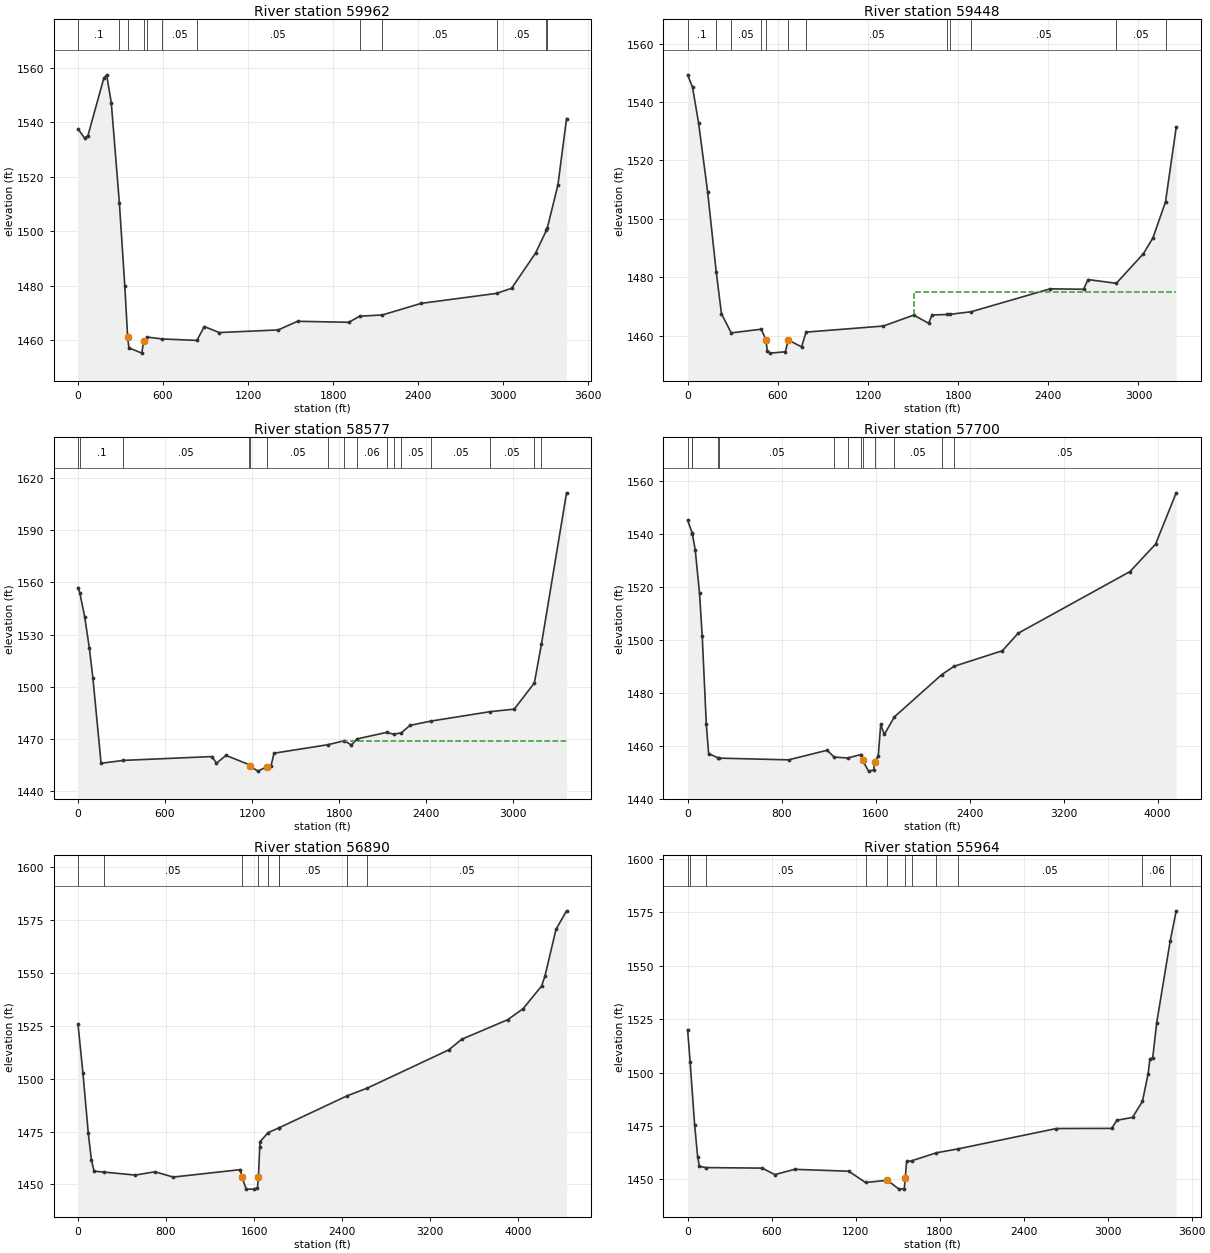
Type RM Length L Ch R = 1 ,59962   ,491.1,514.4,539.7
XS GIS Cut Line= 4
2483867.64915445617468.9461874382483867.64915445617259.835855809
2483775.84461862616918.1189724142485168.21341215614393.494236889
#Sta/Elev= 30
       0 1537.57    46.1 1534.27    70.1 1535.08   182.1  1556.2   202.1 1557.46
   234.9 1547.24   292.2 1510.25   330.2 1480.01  350.561460.956   359.2 1457.16
   450.3 1455.21   462.7 1459.52  488.421461.109  592.571460.419  839.121459.883
     891 1464.98     996 1462.77  1411.7 1463.73  1548.8 1466.91    1910 1466.54
 1986.611468.765 2147.61 1469.25  2421.2  1473.5 2952.631477.164  3058.3 1479.03
  3227.7 1491.98  3304.61500.381 3311.111501.349  3385.1 1516.96  3446.1 1541.41
#Mann= 12 ,-1 , 0
       0      .1       0   292.2      .1       0  350.56    .045       0
   462.7      .1       0  488.42    .025       0  592.57     .05       0
  839.12     .05       0 1986.61     .06       0 2147.61     .05       0
 2952.63     .05       0  3304.6      .1       0 3311.11     .05       0
Bank Sta=350.56,462.7
XS Rating Curve= 0 ,0
Exp/Cntr(USF)=0,0
Exp/Cntr=0.3,0.1

Type RM Length L Ch R = 1 ,59448   ,849.7,870,861.3
XS GIS Cut Line= 4
2484265.46880975617499.547699384 2484296.0703217617050.725524179
2484341.97258961616076.5773939062485219.21593206614475.098268745
#Sta/Elev= 30
       0 1549.32    32.7 1545.05    73.1 1532.81     133 1509.29  190.121481.937
   225.2 1467.49  290.111460.933  489.911462.195   521.8 1458.48   529.8 1454.72
   549.8    1454   649.9 1454.46   669.9 1458.48     758 1456.16  788.531461.198
  1302.6 1463.28  1504.5 1467.03  1603.7 1464.23  1626.5 1467.07 1725.591467.234
  1745.51467.278 1887.191468.183  2412.1 1476.02    2635 1475.88  2664.5 1479.19
  2852.51477.919  3032.8 1488.05  3096.3 1493.47 3179.971505.839  3251.1 1531.37
#Mann= 12 ,-1 , 0
       0      .1       0  190.12      .1       0  290.11     .05       0
  489.91      .1       0   521.8    .045       0   669.9      .1       0
  788.53     .05       0 1725.59     .05       0  1745.5     .06       0
 1887.19     .05       0  2852.5     .05       0 3179.97      .1       0
#XS Ineff= 2 , 0
                          1504.5            1475
Permanent Ineff=
       F       F
Bank Sta=521.8,669.9
XS Rating Curve= 0 ,0
Exp/Cntr(USF)=0,0
Exp/Cntr=0.3,0.1

Type RM Length L Ch R = 1 ,58577   ,852.7,877.5,906.2
XS GIS Cut Line= 4
2484469.47888939617621.9537471672484964.20333251616831.414688568
2485188.61442011616163.281677752 2485423.2260117 614449.59700879
#Sta/Elev= 30
       0 1556.92   12.431554.025    46.1 1540.31    78.6 1522.07   102.7 1505.15
   159.3 1456.07   313.71457.726   923.8 1459.93   954.2 1456.09  1020.3 1460.59
  1177.71455.351  1186.3 1454.23  1241.2 1451.56  1304.2 1454.18  1329.8 1454.35
  1350.9 1461.85 1720.381466.699 1835.861469.027  1884.1 1466.54 1923.951470.066
 2127.521473.795 2175.45 1472.73 2229.311473.577  2287.8 1477.82 2432.881480.301
 2840.031485.706  3006.4 1487.15 3145.391502.197 3194.24 1524.59  3367.1 1611.35
#Mann= 16 ,-1 , 0
       0      .1       0   12.43      .1       0   313.7     .05       0
  1177.7    .025       0  1186.3    .045       0  1304.2     .05       0
 1720.38     .06       0 1835.86     .05       0 1923.95     .06       0
 2127.52     .05       0 2175.45     .06       0 2229.31     .05       0
 2432.88     .05       0 2840.03     .05       0 3145.39      .1       0
 3194.24      .1       0
#XS Ineff= 2 , 0
                         1817.12         1468.89
Permanent Ineff=
       F       F
Bank Sta=1186.3,1304.2
XS Rating Curve= 0 ,0
Exp/Cntr(USF)=0,0
Exp/Cntr=0.3,0.1

Type RM Length L Ch R = 1 ,57700   ,787.4,810.3,842.6
XS GIS Cut Line= 4
2484566.38367722617774.9613068952485530.33130351617127.229304044
2486274.96809419616515.1990651282488065.15654301615551.251438837
#Sta/Elev= 30
       0  1545.3   38.011540.637      401540.287    64.7 1534.12   101.2 1517.77
   124.3 1501.46   158.8 1468.35   178.7 1457.04  258.62 1455.41  268.161455.297
   859.3 1454.65  1187.5 1458.28 1246.551455.717 1361.47 1455.34 1476.391456.668
  1488.7 1454.54  1539.9 1450.38    1584 1450.83  1591.6 1453.97  1622.3 1455.99
  1643.4 1468.03  1674.5 1464.24 1759.121470.877 2162.441486.875 2267.531490.039
  2679.2 1495.94  2813.3 1502.55    3765 1525.88  3982.7 1536.26  4158.5 1555.68
#Mann= 13 ,-1 , 0
       0      .1       0   38.01      .1       0      40      .1       0
  258.62     .05       0  268.16     .05       0 1246.55      .1       0
 1361.47     .05       0 1476.39      .1       0  1488.7    .045       0
  1591.6      .1       0 1759.12     .05       0 2162.44     .06       0
 2267.53     .05       0
#XS Ineff= 2 , 0
                         1643.84          1467.9
Permanent Ineff=
       F       F
Bank Sta=1488.7,1591.6
XS Rating Curve= 0 ,0
Exp/Cntr(USF)=0,0
Exp/Cntr=0.3,0.1

Type RM Length L Ch R = 1 ,56890   ,886.2,925.3,954.5
XS GIS Cut Line= 4
2484490.55153547617938.6031368932485777.85793648617707.727532364
2486204.62799334617623.7727670812488688.28979964 616574.33820104
#Sta/Elev= 30
       0 1525.91    44.9 1502.76    93.7 1474.26   122.1 1461.51   146.5 1456.25
  236.741455.814   520.2 1454.41   699.2 1455.96   865.8 1453.46  1475.9 1456.98
 1490.53 1453.26  1528.9 1447.76  1602.3 1447.75  1630.8 1448.33 1639.291453.264
  1651.2 1467.47  1655.3 1470.25 1726.851474.462 1827.211476.764 1828.621476.805
 2441.951491.836 2629.041495.568  3369.2 1513.66  3486.4 1518.67  3903.2  1527.9
  4043.7 1533.09  4211.6 1543.84  4242.4 1548.45  4342.8 1570.65  4439.1 1579.45
#Mann= 9 ,-1 , 0
       0      .1       0  236.74     .05       0 1490.53    .045       0
 1639.29      .1       0 1726.85     .05       0 1827.21      .1       0
 1828.62     .05       0 2441.95     .06       0 2629.04     .05       0
Bank Sta=1490.53,1639.29
XS Rating Curve= 0 ,0
Exp/Cntr(USF)=0,0
Exp/Cntr=0.3,0.1

Type RM Length L Ch R = 1 ,55964   ,667.6,703.5,729.1
XS GIS Cut Line= 4
2484427.58546151618029.5541326172485491.01248843618428.339267713
2486099.68453674618603.2450287192487764.78738152619037.011316016
#Sta/Elev= 30
       0  1520.1   17.821505.031    50.1 1475.58    71.7 1460.51    84.5 1456.09
  132.231455.524   533.1 1455.27   622.8 1452.23   763.8  1454.7  1150.5 1453.83
 1270.671448.555  1426.8 1449.56    1510 1445.44  1547.5 1445.64 1554.511450.686
  1564.3  1458.4 1600.061458.697 1776.651462.443 1927.651464.233  2633.7  1473.8
  3028.8 1473.86    3066 1477.67  3177.6    1479 3248.551486.511  3289.2 1499.44
  3301.6 1506.27  3322.3 1507.03  3350.1 1523.19 3447.421561.786  3489.7 1575.68
#Mann= 11 ,-1 , 0
       0      .1       0   17.82      .1       0  132.23     .05       0
 1270.67      .1       0  1426.8    .045       0 1554.51      .1       0
 1600.06     .05       0 1776.65     .05       0 1927.65     .05       0
 3248.55     .06       0 3447.42      .1       0
Bank Sta=1426.8,1554.51
XS Rating Curve= 0 ,0
Exp/Cntr(USF)=0,0
Exp/Cntr=0.3,0.1