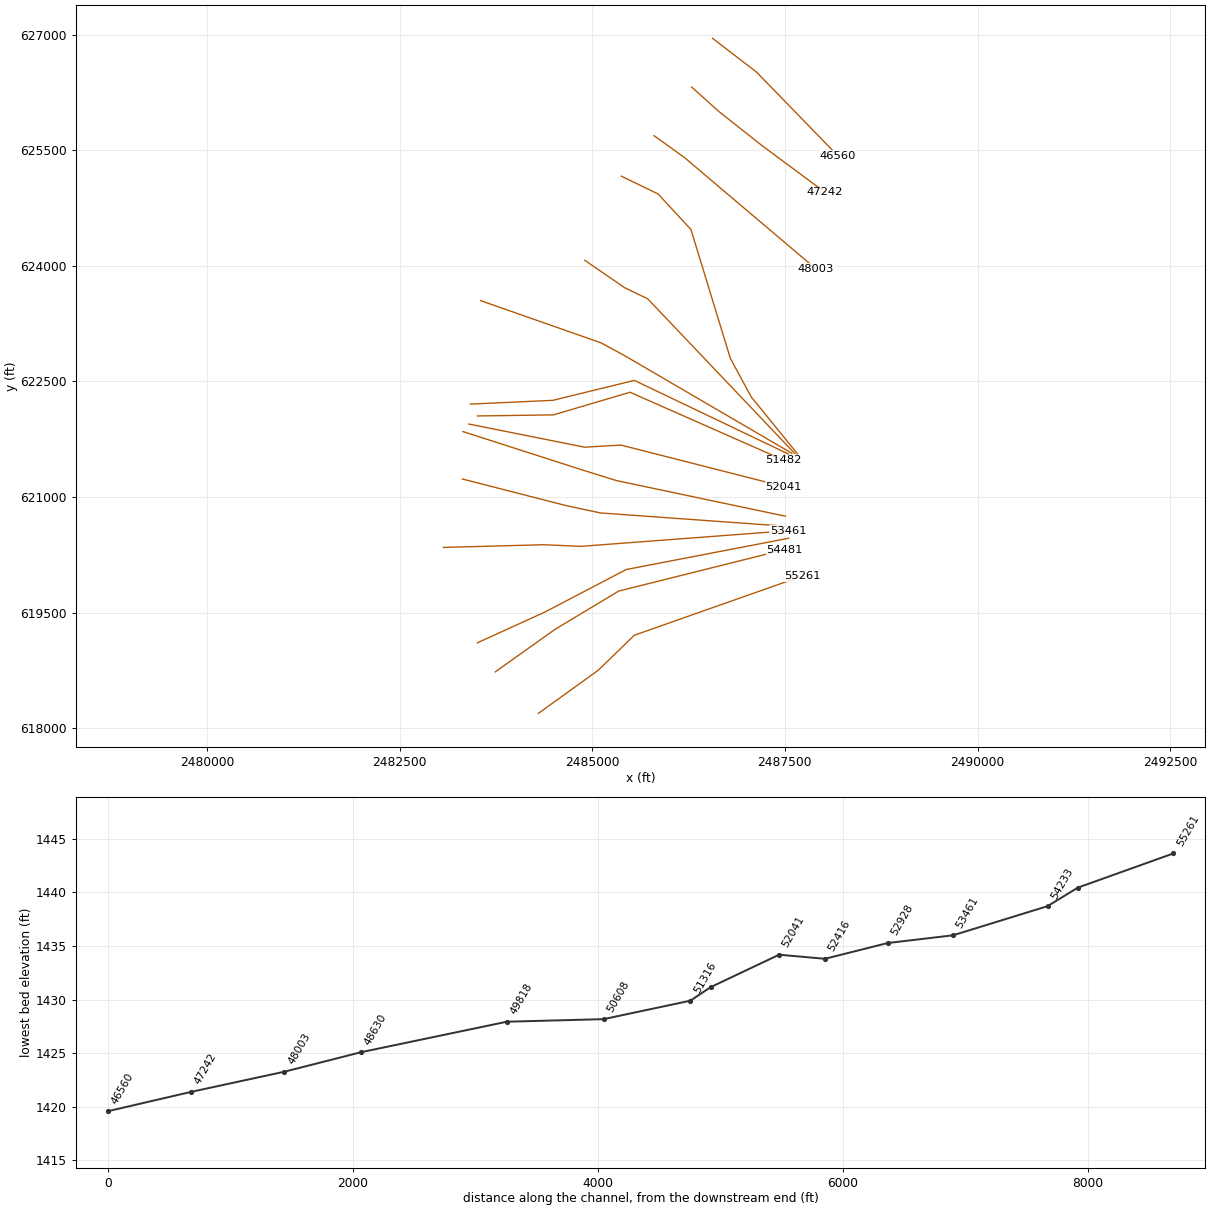
HEC-RAS study SFSBPOTOMC.prj: SFSBPOTOMC

--- SFSBPOTOMC.g01 (geometry) --- (continued)

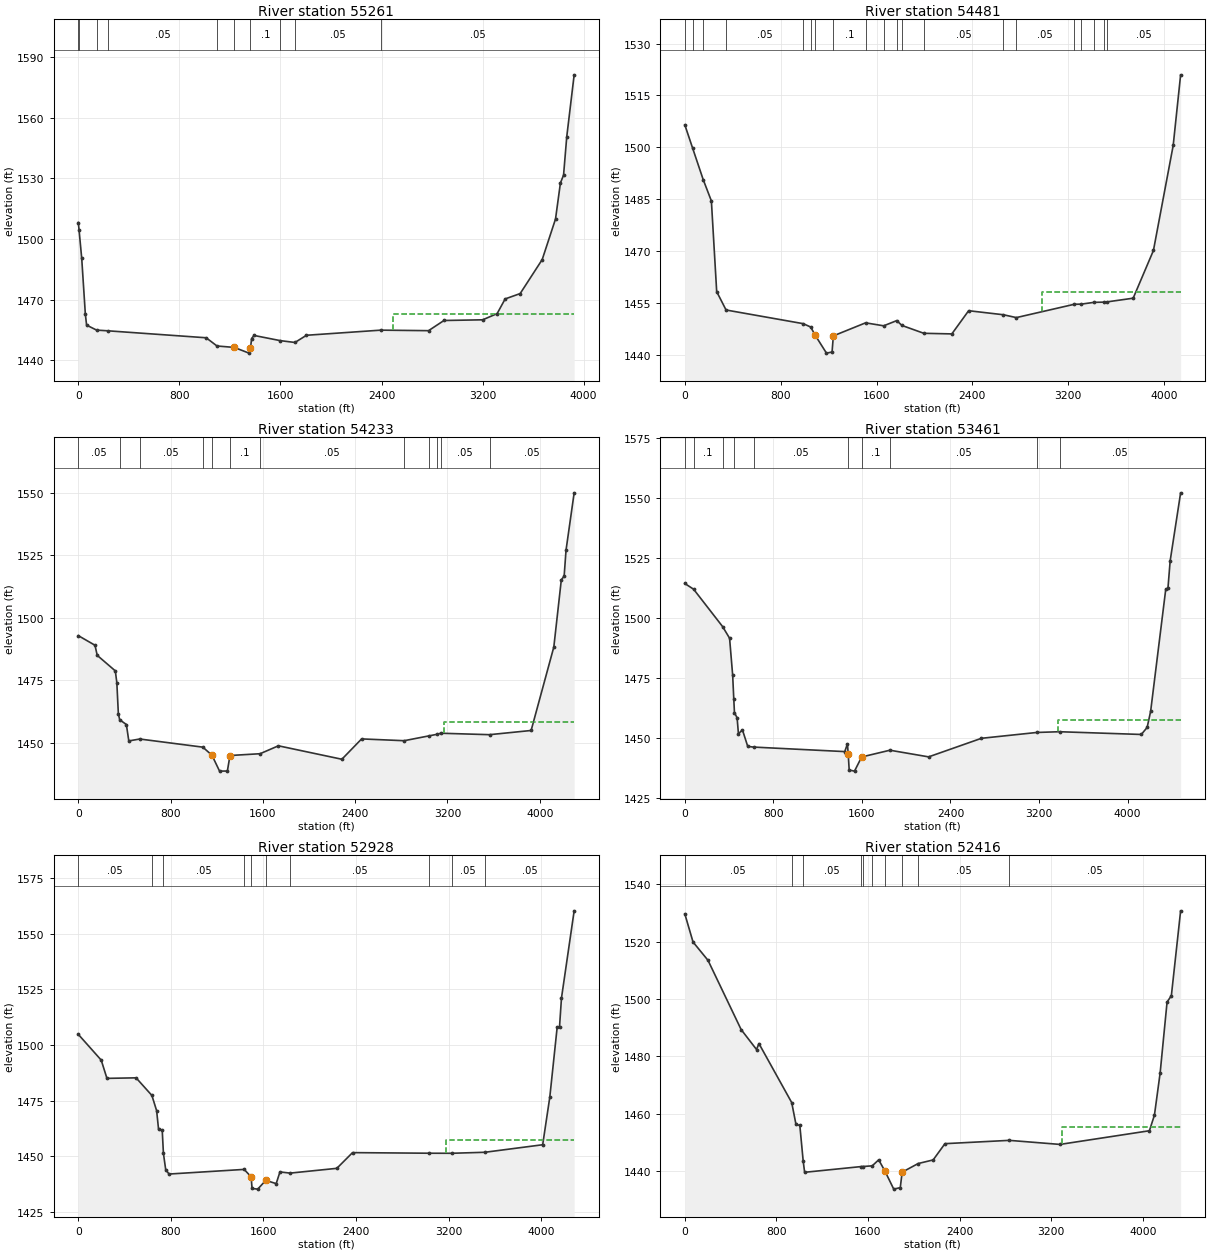
Type RM Length L Ch R = 1 ,55261   ,794.7,779.8,756.2
XS GIS Cut Line= 4
2484301.65331359618190.4674327432485078.23489246618750.165867965
2485546.98233196619204.9208465832487729.80622932619974.506195013
#Sta/Elev= 30
       0 1508.19    5.781504.493    26.9 1490.42    55.5 1462.92    65.4 1457.49
  144.671455.016  234.051454.673  1011.9 1451.23 1097.691447.166    1234 1446.47
  1351.3 1443.64  1362.6 1446.07  1371.9 1450.87  1390.9 1452.38 1597.681449.828
 1714.871448.907  1806.1 1452.47 2394.391455.002  2772.2 1454.74  2894.2 1459.77
  3200.6 1460.11  3315.1 1463.17  3378.7 1470.44  3497.5 1473.08  3671.9 1489.88
  3777.4 1509.97  3816.1 1527.74    3841 1531.63  3866.3 1550.63  3924.9 1581.22
#Mann= 10 ,-1 , 0
       0      .1       0    5.78      .1       0  144.67     .05       0
  234.05     .05       0 1097.69      .1       0    1234    .045       0
  1362.6      .1       0 1597.68     .05       0 1714.87     .05       0
 2394.39     .05       0
#XS Ineff= 2 , 0
                         2491.32         1462.86
Permanent Ineff=
       F       F
Bank Sta=1234,1362.6
XS Rating Curve= 0 ,0
Exp/Cntr(USF)=0,0
Exp/Cntr=0.3,0.1

Type RM Length L Ch R = 1 ,54481   ,257.4,247.8,248.6
XS GIS Cut Line= 4
2483741.95487836618729.1771766442484518.53645724619281.879381426
2485344.09164919619778.6117426852487498.93062479620317.321486586
#Sta/Elev= 30
       0  1506.5   64.861499.788  153.241490.671   221.9 1484.46   266.1 1458.24
  344.331452.926  988.281448.972 1050.991447.993 1085.55 1445.77  1182.2 1440.45
  1228.9 1440.77  1239.7 1445.44 1508.741449.212 1659.691448.352 1768.961449.858
 1811.871448.459 1994.831446.185  2228.6 1446.01  2368.8 1452.72 2658.681451.551
 2766.771450.728 3250.031454.578 3307.221454.615 3415.311455.139 3501.071455.198
  3523.4 1455.27  3741.8 1456.34  3910.9 1470.14  4075.8 1500.52  4137.8 1520.95
#Mann= 20 ,-1 , 0
       0     .05       0   64.86    .055       0  153.24     .05       0
  344.33     .05       0  988.28    .025       0 1050.99      .1       0
 1085.55    .045       0  1239.7      .1       0 1508.74     .05       0
 1659.69      .1       0 1768.96     .05       0 1811.87      .1       0
 1994.83     .05       0 2658.68     .05       0 2766.77     .05       0
 3250.03     .05       0 3307.22     .05       0 3415.31     .05       0
 3501.07     .05       0  3523.4     .05       0
#XS Ineff= 2 , 0
                         2983.87         1458.15
Permanent Ineff=
       F       F
Bank Sta=1085.55,1239.7
XS Rating Curve= 0 ,0
Exp/Cntr(USF)=0,0
Exp/Cntr=0.3,0.1

Type RM Length L Ch R = 1 ,54233   ,807.1,772.4,725.3
XS GIS Cut Line= 4
2483511.07927384619106.9736204192484385.60807887619505.758755515
2485442.03887535620058.4609602962487547.90423787620464.242325832
#Sta/Elev= 30
       0 1492.92   144.4 1489.08   163.7 1485.04   320.6 1478.82   333.7 1474.12
   346.9 1461.75  358.361459.269   416.4 1457.37   437.5  1450.8  532.341451.569
 1079.241448.312 1158.051445.103  1224.3 1438.72    1292 1438.76  1314.6 1444.97
 1575.531445.684  1734.4 1448.85  2284.5 1443.47  2455.6 1451.61 2824.23 1450.89
 3035.761452.791 3113.071453.488 3141.531453.882  3564.61453.302  3924.9 1454.98
  4121.7 1488.37  4186.6 1515.22  4211.3 1516.78  4227.6 1527.14    4298 1550.06
#Mann= 12 ,-1 , 0
       0     .05       0  358.36     .06       0  532.34     .05       0
 1079.24      .1       0 1158.05    .045       0  1314.6      .1       0
 1575.53     .05       0 2824.23     .05       0 3035.76     .05       0
 3113.07     .05       0 3141.53     .05       0  3564.6     .05       0
#XS Ineff= 2 , 0
                         3169.98         1458.38
Permanent Ineff=
       F       F
Bank Sta=1158.05,1314.6
XS Rating Curve= 0 ,0
Exp/Cntr(USF)=0,0
Exp/Cntr=0.3,0.1

Type RM Length L Ch R = 1 ,53461   ,541.1,533.1,521.4
XS GIS Cut Line= 4
 2483070.3167561620345.3064083482484371.61561799620380.287560549
2484854.35551837620359.2988692282487540.90800743620562.189551996
#Sta/Elev= 30
       0  1514.2   79.661511.814  341.431496.247   404.6 1491.39   432.6 1475.86
  442.521466.036   448.6 1460.35   472.6 1458.21   484.6 1451.53   520.6 1453.22
   568.6  1446.3  621.711446.023    1445 1444.14  1469.1 1447.33 1476.12 1443.27
  1485.1 1436.45  1533.1    1436  1597.7  1441.9 1853.231444.715  2202.5 1441.94
  2679.7 1449.68 3181.18 1452.12 3385.48 1452.42    4124 1451.28  4176.7 1454.21
  4208.2 1460.89  4344.6 1511.71  4364.7 1512.19  4384.7 1523.65  4479.2 1551.99
#Mann= 10 ,-1 , 0
       0     .05       0   79.66      .1       0  341.43     .05       0
  442.52     .06       0  621.71     .05       0 1476.12    .045       0
  1597.7      .1       0 1853.23     .05       0 3181.18     .05       0
 3385.48     .05       0
#XS Ineff= 2 , 0
                         3368.49          1457.3
Permanent Ineff=
       F       F
Bank Sta=1476.12,1597.7
XS Rating Curve= 0 ,0
Exp/Cntr(USF)=0,0
Exp/Cntr=0.3,0.1

Type RM Length L Ch R = 1 ,52928   ,502.9,511.9,496.4
XS GIS Cut Line= 4
2483315.18482151621233.827674262 2484651.4648356620891.012382689
2485106.21981422620793.0651565252487540.90800743620618.159395518
#Sta/Elev= 30
       0 1504.79   197.8 1493.24   247.3 1485.04   499.2 1485.28  635.781477.371
   676.8 1470.51   693.3 1462.23   725.1 1461.77   735.51451.346   755.3    1444
   784.2 1442.06 1433.411444.142  1493.5  1440.8  1501.6 1435.58  1550.7 1435.28
  1620.2 1439.22  1710.2 1437.75  1742.6    1443 1831.191442.479  2234.3 1444.62
  2370.1 1451.68 3027.681451.412  3227.11451.383 3514.331451.839  4013.6 1455.22
    4075 1476.55  4139.2 1508.18  4159.2 1508.21  4176.1 1521.14  4285.7 1560.31
#Mann= 10 ,-1 , 0
       0     .05       0  635.78     .06       0   735.5     .05       0
 1433.41      .1       0  1493.5    .045       0  1620.2      .1       0
 1831.19     .05       0 3027.68     .05       0  3227.1     .05       0
 3514.33     .05       0
#XS Ineff= 2 , 0
                         3176.18         1457.37
Permanent Ineff=
       F       F
Bank Sta=1493.5,1620.2
XS Rating Curve= 0 ,0
Exp/Cntr(USF)=0,0
Exp/Cntr=0.3,0.1

Type RM Length L Ch R = 1 ,52416   ,342.3,374.7,396.8
XS GIS Cut Line= 4
2483322.18105195621849.4959530062484889.33667057621345.767361307
2485316.10672743621212.8389829422487505.92685523620751.087773883
#Sta/Elev= 30
       0 1529.67      72 1519.86   202.8 1513.48   492.2 1489.37   626.6 1482.43
   647.6  1484.5  933.971463.945   971.2 1456.33  1004.8 1455.99 1034.411443.484
  1046.8 1439.67 1536.651441.647 1553.041441.681  1637.11441.917  1693.7 1444.01
  1748.1  1440.1  1825.2 1433.81  1882.2 1434.33  1898.7 1439.72 2038.37 1442.72
  2169.4 1443.98  2272.5 1449.64 2834.261450.791  3277.2 1449.38  4058.5 1454.14
  4102.4 1459.59  4152.1 1474.24  4212.7 1498.96  4250.2 1501.18  4331.1 1530.72
#Mann= 10 ,-1 , 0
       0     .05       0  933.97    .055       0 1034.41     .05       0
 1536.65      .1       0 1553.04     .05       0  1637.1      .1       0
  1748.1    .045       0  1898.7      .1       0 2038.37     .05       0
 2834.26     .05       0
#XS Ineff= 2 , 0
                         3294.04         1455.44
Permanent Ineff=
       F       F
Bank Sta=1748.1,1898.7
XS Rating Curve= 0 ,0
Exp/Cntr(USF)=0,0
Exp/Cntr=0.3,0.1

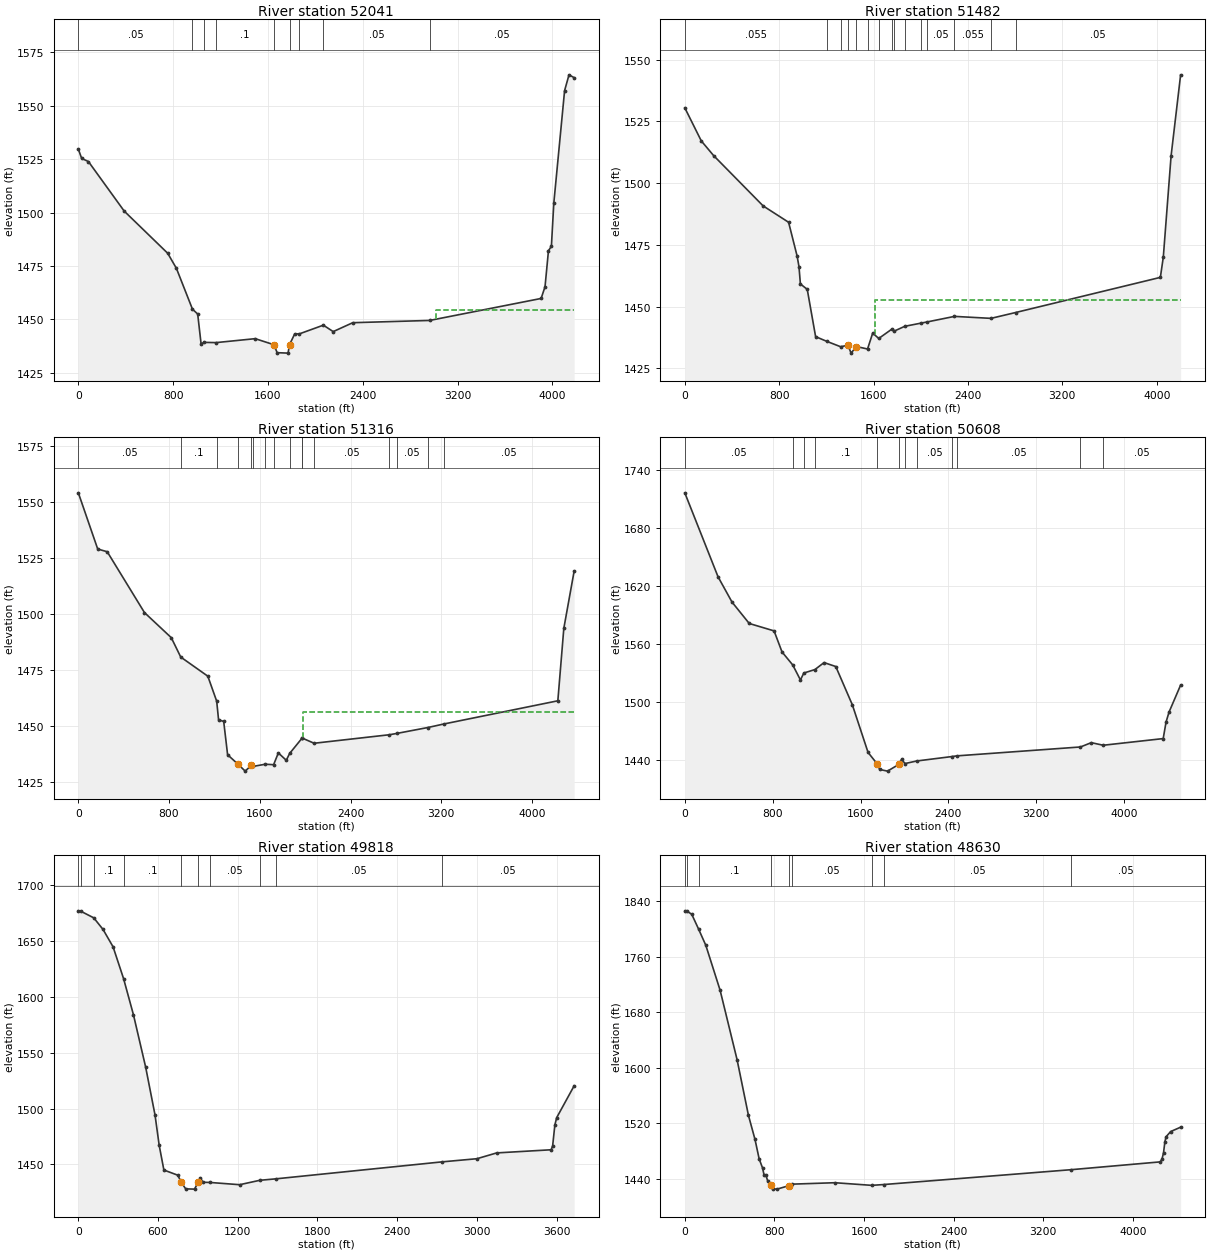
Type RM Length L Ch R = 1 ,52041   ,545.1,559.3,577.8
XS GIS Cut Line= 4
2483399.13958679 621947.443179172484903.32913145621646.605270238
2485372.07657095   621674.5901922487484.93816391621135.880448099
#Sta/Elev= 30
       0  1529.7    28.2 1525.37    85.3 1523.89   387.1  1500.7   754.3 1480.95
   827.7 1473.88  963.111454.768  1007.2  1452.5  1035.7 1438.59 1062.491439.224
 1161.871439.114  1492.4 1440.96 1650.521438.132  1677.6  1434.4  1769.8 1434.19
 1782.041438.132  1825.9  1443.2 1865.341443.209 2067.56 1447.28  2150.8 1444.27
  2315.9 1448.44 2964.941449.495  3905.2 1459.79  3938.2 1465.28  3967.1 1482.13
  3991.9 1484.23  4012.5 1504.54  4103.3 1557.12  4140.5 1564.51    4184 1563.18
#Mann= 9 ,-1 , 0
       0     .05       0  963.11     .06       0 1062.49     .05       0
 1161.87      .1       0 1650.52    .045       0 1782.04      .1       0
 1865.34     .05       0 2067.56     .05       0 2964.94     .05       0
#XS Ineff= 2 , 0
                         3021.09         1454.59
Permanent Ineff=
       F       F
Bank Sta=1650.52,1782.04
XS Rating Curve= 0 ,0
Exp/Cntr(USF)=0,0
Exp/Cntr=0.5,0.3

Type RM Length L Ch R = 1 ,51482   ,167.9,165.5,165
XS GIS Cut Line= 4
2483511.07927384622052.3866357742484497.54776591622066.379096655
2485491.01248843622360.2207751472487484.93816391621478.695739672
#Sta/Elev= 30
       0 1530.52   139.7 1517.12   243.7  1511.2   663.7  1490.8   879.8 1484.16
   951.8 1470.53   967.8  1466.2   979.8 1459.18  1037.9 1456.99  1108.8 1437.84
 1203.171435.936 1320.81 1433.75  1383.9 1434.37  1409.1 1431.16    1455 1433.83
 1549.011432.832  1592.7 1439.27    16441437.102  1754.21440.854 1777.211440.129
 1864.411442.023 2005.411443.341  2050.9 1443.76 2285.85 1446.04  2595.2 1445.24
 2803.38  1447.6    4031 1461.84    4056 1470.08    4122 1511.11  4202.7 1543.88
#Mann= 15 ,-1 , 0
       0    .055       0 1203.17      .1       0 1320.81    .055       0
  1383.9    .045       0    1455      .1       0 1549.01    .055       0
    1644      .1       0  1754.2     .05       0 1777.21     .06       0
 1864.41     .05       0 2005.41    .055       0  2050.9     .05       0
 2285.85    .055       0  2595.2     .06       0 2803.38     .05       0
#XS Ineff= 2 , 0
                         1610.08         1452.58
Permanent Ineff=
       F       F
Bank Sta=1383.9,1455
XS Rating Curve= 0 ,0
Exp/Cntr(USF)=0,0
Exp/Cntr=0.5,0.3

Type RM Length L Ch R = 1 ,51316   ,751.3,708.5,677.4
XS GIS Cut Line= 4
2483420.12827811 622206.303705462484490.55153547622255.277318542
2485546.98233196622514.1378448332487543.30628025621559.570946217
#Sta/Elev= 30
       0 1553.95   170.8 1528.91   254.9 1527.68   583.2 1500.57   819.5 1489.39
  903.041480.746  1141.8 1472.22    1220 1461.07  1236.5 1452.81  1281.8 1452.03
  1316.2  1437.2  1408.8 1432.95  1471.2  1429.9  1524.6 1432.43 1539.651431.988
 1647.521432.972  1721.91432.771  1763.6 1438.01  1833.6 1434.73 1863.271437.781
 1971.151444.499 1975.761444.595 2079.021442.325 2742.94 1446.12 2806.771446.689
 3081.771449.339 3220.761450.887  4228.1 1461.25  4280.9 1493.55    4372 1519.09
#Mann= 16 ,-1 , 0
       0     .05       0  903.04      .1       0    1220     .05       0
  1408.8    .045       0  1524.6     .06       0 1539.65     .05       0
 1647.52     .06       0  1721.9     .05       0 1863.27     .06       0
 1971.15    .055       0 1975.76     .05       0 2079.02     .05       0
 2742.94     .06       0 2806.77     .05       0 3081.77     .06       0
 3220.76     .05       0
#XS Ineff= 2 , 0
                            1977         1456.13
Permanent Ineff=
       F       F
Bank Sta=1408.8,1524.6
XS Rating Curve= 0 ,0
Exp/Cntr(USF)=0,0
Exp/Cntr=0.5,0.3

Type RM Length L Ch R = 1 ,50608   ,785.5,789.6,797.3
XS GIS Cut Line= 4
2483553.05665648623549.5799499932485114.06958477623001.911533013
2485410.82799173622841.4082119912487589.44168355621568.525512509
#Sta/Elev= 30
       0 1716.04   302.8 1629.16   429.9 1603.04   586.8  1580.9   813.1 1573.22
   885.2 1551.46  982.931537.983  1053.1 1522.46 1083.811529.661  1184.71533.223
  1268.1 1540.45  1374.8 1536.37  1525.4 1496.84  1668.8  1447.5 1754.621435.283
  1775.1 1429.88  1845.9 1428.18 1951.041435.284  1973.4 1440.24 2006.281436.048
 2112.721438.689 2432.051443.253  2477.81443.968 3602.93 1453.17  3701.4 1457.63
 3810.171454.947  4356.2 1461.84  4382.5 1479.08  4409.8 1489.34  4514.9 1517.19
#Mann= 12 ,-1 , 0
       0     .05       0  982.93      .1       0 1083.81     .06       0
  1184.7      .1       0 1754.62    .045       0 1951.04      .1       0
 2006.28     .05       0 2112.72     .05       0 2432.05     .05       0
  2477.8     .05       0 3602.93     .06       0 3810.17     .05       0
Bank Sta=1754.62,1951.04
XS Rating Curve= 0 ,0
Exp/Cntr(USF)=0,0
Exp/Cntr=0.3,0.1

Type RM Length L Ch R = 1 ,49818   ,1213.9,1188.5,1150.7
XS GIS Cut Line= 4
2484903.32913145624074.2972330142485420.41165907623718.128005523
2485719.68840815623574.0881370142487629.21938138621564.168903844
#Sta/Elev= 30
       0 1677.15   18.451676.793   116.11670.867   186.1 1660.46   261.6 1644.88
  340.741616.363     415 1584.03   506.7 1537.24   577.2 1494.43   608.7 1467.13
     644 1445.05   748.9  1440.4  773.291434.333     808 1428.18   874.6 1427.94
   901.8 1434.05     919 1438.09   936.8 1434.08  990.96 1433.92  1214.2  1431.9
  1365.31435.827 1490.091437.187 2737.91 1452.35  3000.3 1455.17  3149.3 1460.37
    3559 1463.18  3570.3 1466.51  3587.2 1485.43    3601 1491.97  3732.4 1520.49
#Mann= 10 ,-1 , 0
       0     .06       0   18.45     .12       0   116.1      .1       0
  340.74      .1       0  773.29    .045       0   901.8      .1       0
  990.96     .05       0  1365.3     .05       0 1490.09     .05       0
 2737.91     .05       0
Bank Sta=773.29,901.8
XS Rating Curve= 0 ,0
Exp/Cntr(USF)=0,0
Exp/Cntr=0.3,0.1

Type RM Length L Ch R = 1 ,48630   ,615.3,626.6,641.9
XS GIS Cut Line= 6
2485379.07280139625165.7091816962485854.81647133624934.833577167
2486281.58652818624473.0823681092486792.31135032622800.983292884
2487065.16433749622297.2547011842487663.12207166621561.969219031
#Sta/Elev= 30
       0 1826.54   20.541825.977    61.9  1821.6  124.221799.783   187.5 1776.86
   315.3 1711.94   466.5 1611.97   568.3 1531.44   626.8 1496.75   664.2 1468.46
   693.7 1455.86     707 1446.04     724 1445.39     741 1436.34  767.641430.881
   784.7 1425.52   822.9  1425.1   929.4 1430.05  957.54 1432.29  1339.5 1434.34
 1669.521430.546 1777.871431.746 3449.151453.138  4244.9 1464.41  4260.4  1468.5
  4273.8 1477.54  4286.1 1493.42  4296.5  1500.6  4337.2 1508.12  4426.5 1514.46
#Mann= 9 ,-1 , 0
       0     .06       0   20.54      .1       0  124.22      .1       0
  767.64    .045       0   929.4      .1       0  957.54     .05       0
 1669.52     .05       0 1777.87     .05       0 3449.15     .05       0
Bank Sta=767.64,929.4
XS Rating Curve= 0 ,0
Exp/Cntr(USF)=0,0
Exp/Cntr=0.3,0.1

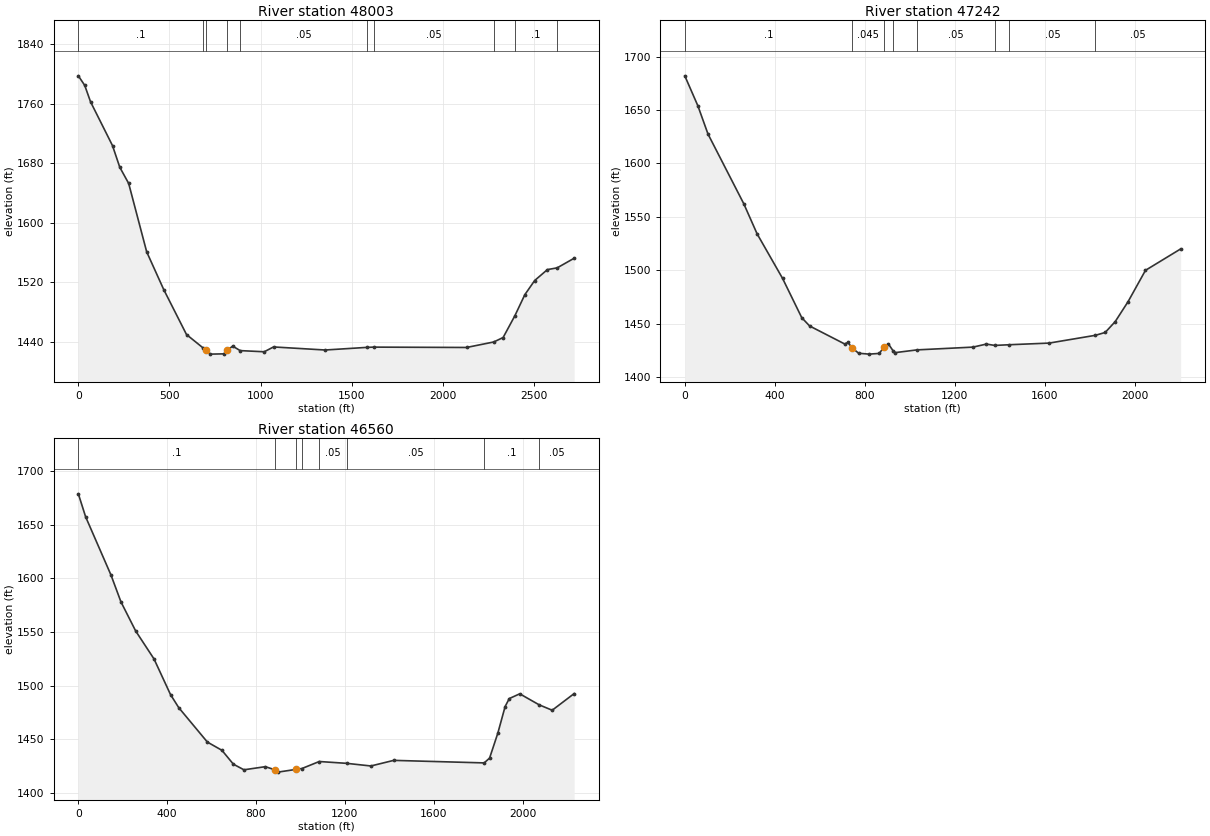
Type RM Length L Ch R = 1 ,48003   ,756.4,760.8,762.8
XS GIS Cut Line= 4
 2485802.3325486625692.1559958482486201.11768369625405.310547797
2486529.94051438625125.4613301862487901.20168068  623964.0870771
#Sta/Elev= 30
       0 1797.26      35 1784.47    67.1 1762.29   187.5 1703.46   227.2 1674.49
   276.2 1652.64     375 1560.72   468.3 1510.12   593.4 1449.61  685.621431.364
  700.021428.754   724.5 1423.28   797.4 1423.65   815.9 1428.26   846.8 1434.05
  887.561428.005  1019.8 1426.45  1070.8 1432.94    1354 1428.82 1583.191432.349
 1619.711432.701  2129.7 1432.22 2278.761439.605  2330.3  1445.6 2394.69 1474.82
  2449.5 1503.18  2503.4 1522.21  2573.3 1536.88 2626.551539.178    2720 1552.14
#Mann= 10 ,-1 , 0
       0      .1       0  685.62    .025       0  700.02    .045       0
   815.9      .1       0  887.56     .05       0 1583.19     .05       0
 1619.71     .05       0 2278.76     .05       0 2394.69      .1       0
 2626.55      .1       0
Bank Sta=700.02,815.9
XS Rating Curve= 0 ,0
Exp/Cntr(USF)=0,0
Exp/Cntr=0.3,0.1

Type RM Length L Ch R = 1 ,47242   ,685.1,682.1,676.5
XS GIS Cut Line= 4
2486292.06867942626321.8167354732486641.88020143 626006.98636566
2487208.57486709625559.2276174832488020.13759816624957.551799619
#Sta/Elev= 30
       0  1682.1    58.2 1653.96   103.1 1627.55   261.9 1562.35   321.2 1534.11
   434.5  1492.3   519.7 1455.53   554.7 1447.76   710.5 1430.91   724.8 1432.34
   744.31427.073   772.5 1422.23   818.4  1421.4   864.3 1422.06   884.7 1428.06
   904.2  1431.1  925.58 1424.48   935.5 1422.82 1031.921425.378  1280.4 1427.97
    1340 1430.81 1377.18 1429.56 1441.87  1430.2  1618.8 1431.74 1824.411439.029
  1867.8 1441.69  1912.4 1451.85  1969.6 1470.56    2047 1499.91  2203.1 1519.93
#Mann= 8 ,-1 , 0
       0      .1       0   744.3    .045       0   884.7      .1       0
  925.58     .12       0 1031.92     .05       0 1377.18     .05       0
 1441.87     .05       0 1824.41     .05       0
Bank Sta=744.3,884.7
XS Rating Curve= 0 ,0
Exp/Cntr(USF)=0,0
Exp/Cntr=0.3,0.1

Type RM Length L Ch R = 1 ,46560   ,590,572.7,551.9
XS GIS Cut Line= 4
2486561.62924054626955.673184455 2487128.3239062626521.207274114
2487562.78981654 626074.148148982488186.15394877625431.894194563
#Sta/Elev= 30
       0 1678.57    32.7 1657.27   146.9 1603.06   191.9 1578.03   258.1 1550.97
   340.9 1524.87     415 1491.78   452.1 1479.59     581 1447.57   646.6 1439.89
   698.2 1426.96   745.7 1421.76   841.9 1424.66   884.3 1421.83   898.5 1419.59
   979.5 1422.11  1007.11422.966 1084.79 1429.47 1208.511427.763  1317.1 1425.31
  1420.1 1430.53 1827.361428.174  1851.7 1432.66  1888.8 1455.83  1921.7 1480.65
  1940.4 1488.05  1987.5 1492.47 2074.921482.219  2133.6 1477.18  2232.5 1492.69
#Mann= 8 ,-1 , 0
       0      .1       0   884.3    .045       0   979.5    .025       0
  1007.1      .1       0 1084.79     .05       0 1208.51     .05       0
 1827.36      .1       0 2074.92     .05       0
Bank Sta=884.3,979.5
XS Rating Curve= 0 ,0
Exp/Cntr(USF)=0,0
Exp/Cntr=0.3,0.1