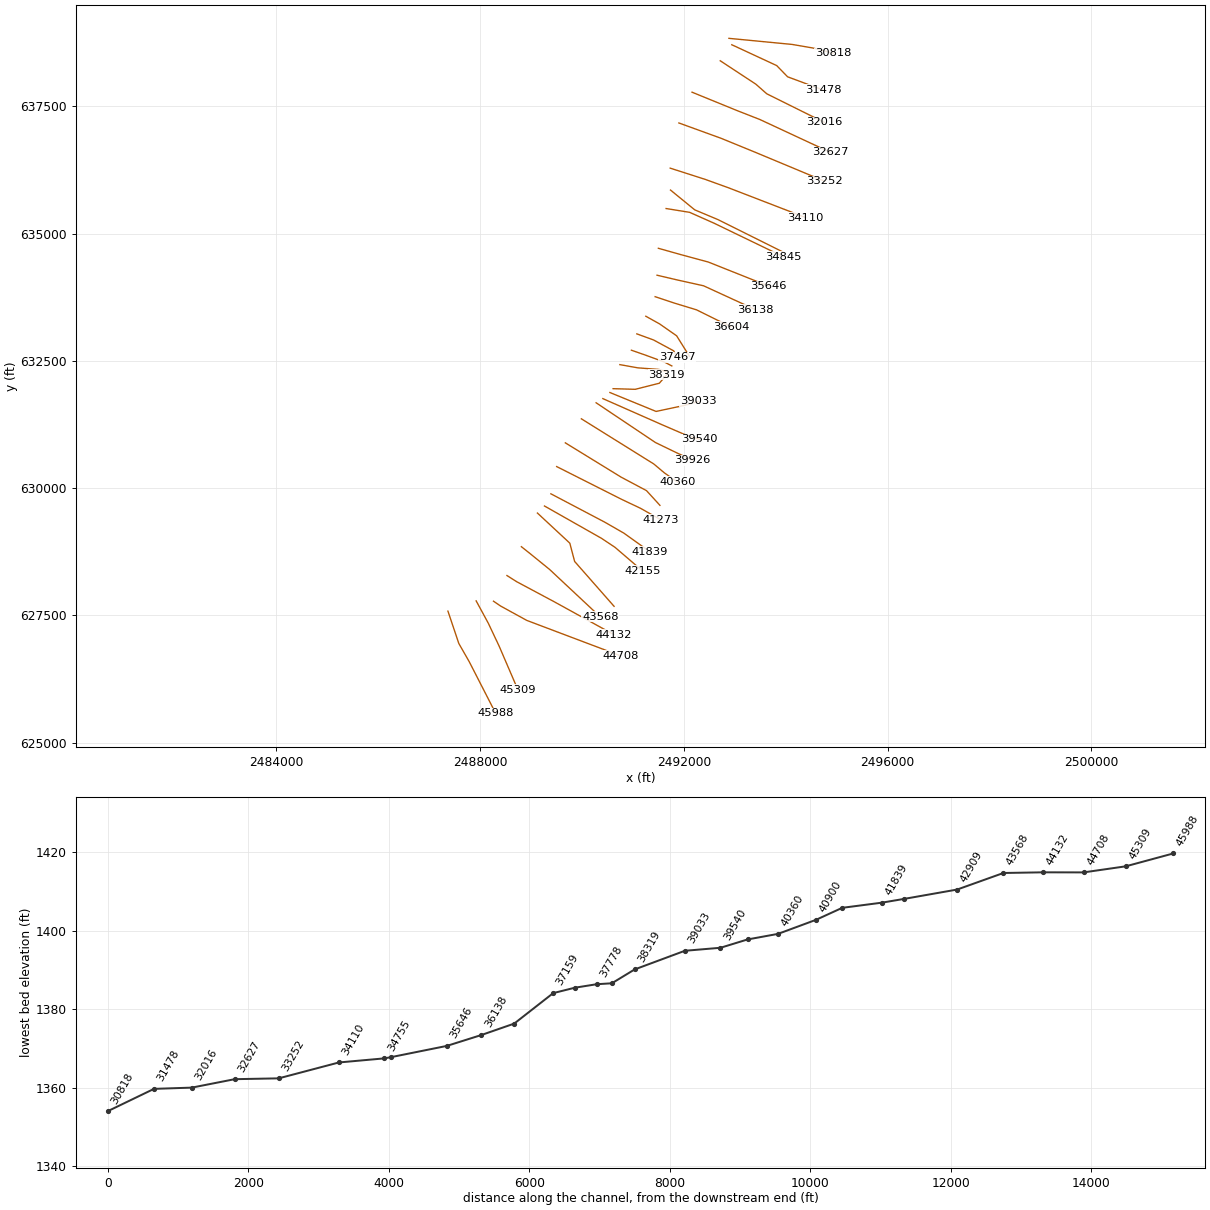
HEC-RAS study SFSBPOTOMC.prj: SFSBPOTOMC

--- SFSBPOTOMC.g01 (geometry) --- (continued)

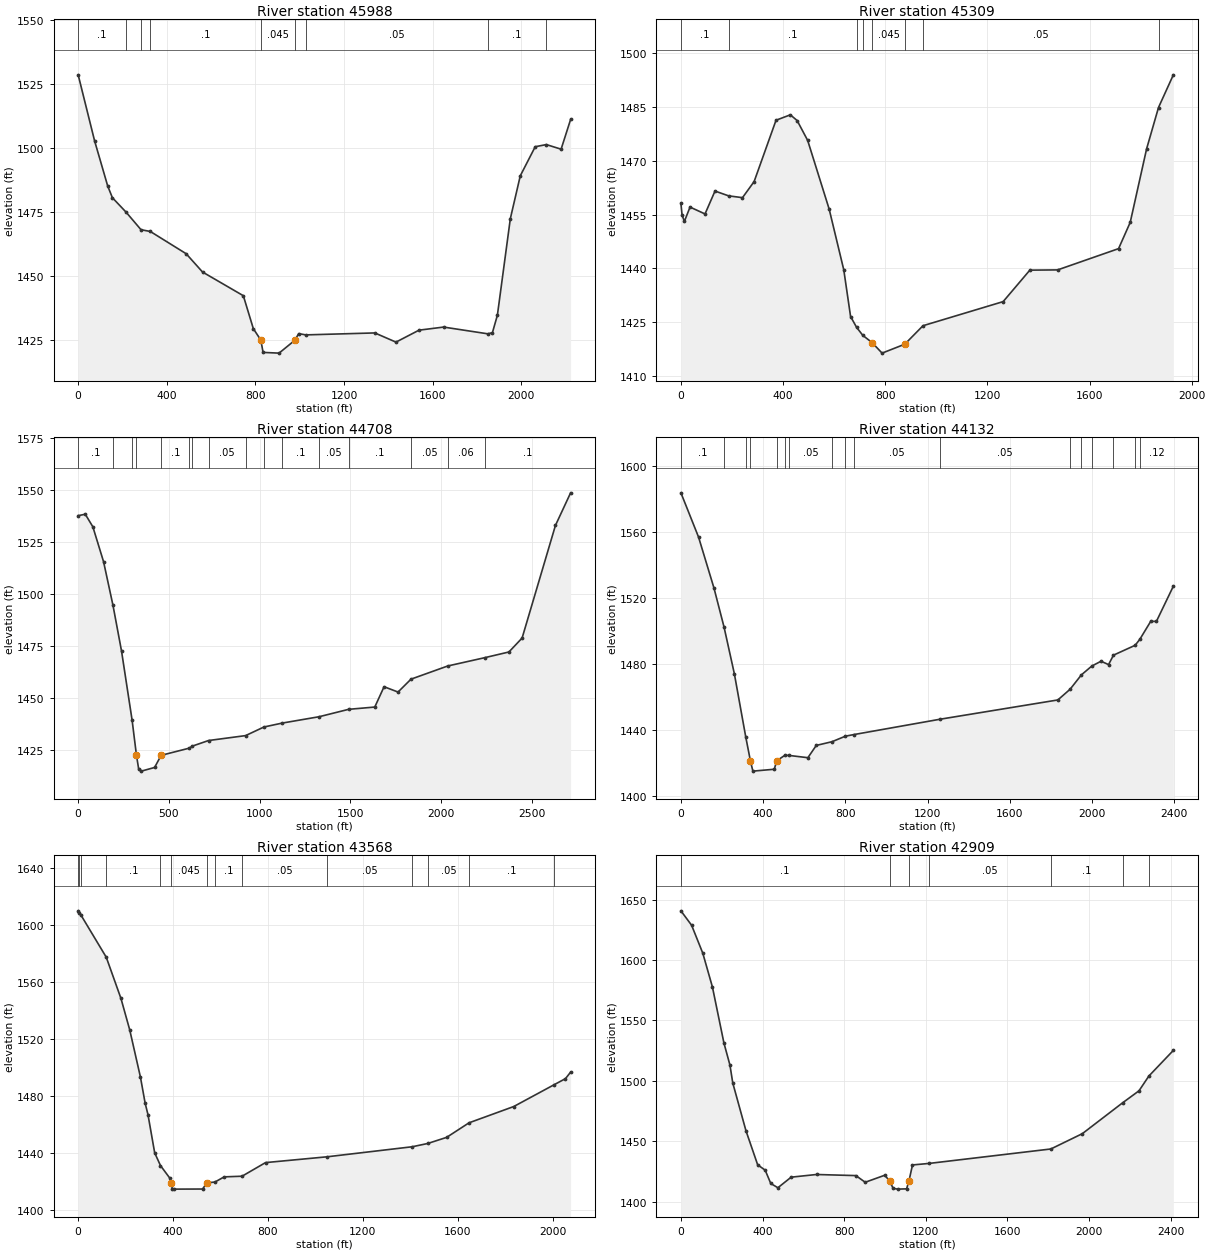
Type RM Length L Ch R = 1 ,45988   ,683.7,678.7,671.6
XS GIS Cut Line= 4
2487367.59498726627585.3339240792487581.67963873626949.376577058
2487783.17107541626596.766562868 2488305.7894893625576.716164676
#Sta/Elev= 30
       0 1528.41    74.3 1502.57   133.4 1484.96   154.5  1480.4  215.96 1474.79
   283.71467.901  325.851467.206   487.5 1458.52   561.5 1451.37   745.7 1442.11
   790.9 1429.23  824.691424.782   834.9 1419.96     907 1419.68   977.9 1424.68
   995.7  1427.3 1027.671426.806  1339.4 1427.57  1434.8 1423.98  1538.9 1428.65
    1650 1429.86 1849.731427.219  1870.3 1427.68  1892.7 1434.47  1951.2 1472.23
  1996.1 1488.96  2063.5 1500.32 2113.751501.157  2180.4 1499.36  2223.3 1510.97
#Mann= 9 ,-1 , 0
       0      .1       0  215.96      .1       0   283.7      .1       0
  325.85      .1       0  824.69    .045       0   977.9     .12       0
 1027.67     .05       0 1849.73      .1       0 2113.75     .05       0
Bank Sta=824.69,977.9
XS Rating Curve= 0 ,0
Exp/Cntr(USF)=0,0
Exp/Cntr=0.3,0.1

Type RM Length L Ch R = 1 ,45309   ,557,600.6,636.7
XS GIS Cut Line= 4
2487921.69643813627786.8253607592488160.96751919627346.062843022
2488375.05217066626892.7071104922488740.25539964626042.665111999
#Sta/Elev= 30
       0 1458.13     4.5 1454.88    13.6 1453.11    35.7  1457.1    94.4 1455.19
   133.5 1461.57  186.791460.231   241.1 1459.73   286.7 1464.22   372.4 1481.31
   428.5 1482.82     455 1481.23   496.3 1475.69   580.4 1456.55   637.7  1439.6
   664.3  1426.6  687.771423.585  712.271421.332   748.6 1419.32   787.7 1416.39
   876.6 1418.88  947.861424.032  1261.7 1430.75  1366.2 1439.52    1475 1439.59
  1713.6 1445.52  1759.2 1452.84  1823.3 1473.32 1869.961484.861  1928.1 1493.97
#Mann= 8 ,-1 , 0
       0      .1       0  186.79      .1       0  687.77      .1       0
  712.27    .025       0   748.6    .045       0   876.6      .1       0
  947.86     .05       0 1869.96      .1       0
Bank Sta=748.6,876.6
XS Rating Curve= 0 ,0
Exp/Cntr(USF)=0,0
Exp/Cntr=0.3,0.1

Type RM Length L Ch R = 1 ,44708   ,572.6,576.2,574.3
XS GIS Cut Line= 4
2488261.71323753627780.5287533632488400.23860024627686.079642419
2488916.56040674627402.7323095882490748.87315905626710.105496001
#Sta/Elev= 30
       0 1537.58    39.3 1538.25      81 1532.22   140.1 1515.44  192.07 1494.45
     239  1472.6  297.461439.322  321.521422.421   333.9 1415.75   348.5 1414.84
   421.5  1416.6  457.471422.423  613.631425.897  628.431426.824  719.021429.542
  923.161431.904 1024.511436.042 1125.861437.934 1328.561440.973 1491.841444.536
  1635.6 1445.62  1686.9 1455.39  1763.9 1452.83 1835.311459.022 2038.011465.355
  2240.71469.317  2375.4 1472.08  2448.1 1478.79  2631.9 1532.88  2715.5 1548.54
#Mann= 16 ,-1 , 0
       0      .1       0  192.07    .025       0  297.46     .05       0
  321.52    .045       0  457.47      .1       0  613.63     .05       0
  628.43      .1       0  719.02     .05       0  923.16      .1       0
 1024.51     .05       0 1125.86      .1       0 1328.56     .05       0
 1491.84      .1       0 1835.31     .05       0 2038.01     .06       0
  2240.7      .1       0
Bank Sta=321.52,457.47
XS Rating Curve= 0 ,0
Exp/Cntr(USF)=0,0
Exp/Cntr=0.3,0.1

Type RM Length L Ch R = 1 ,44132   ,582.6,564.2,554.8
XS GIS Cut Line= 4
2488526.17074817628284.2573450632488715.06897006628164.621804534
2489445.47542802627774.2321459672490622.94101112627125.681584153
#Sta/Elev= 30
       0 1583.56    85.9 1556.71   160.8 1525.87  209.941502.162   260.1 1473.85
  315.311435.691  338.241421.045   350.2 1414.86   454.5    1416  465.531421.044
  505.151424.413  525.271424.386   617.8    1423   658.6 1430.44  735.241432.696
  800.281436.039  840.23 1436.99 1261.081446.326  1834.1 1458.01 1893.77 1464.52
 1948.571473.209 1999.221478.563  2044.2 1481.47  2080.7 1479.43 2104.67 1485.16
 2210.111491.142 2233.461494.878  2285.8 1505.64  2313.6 1505.64    2396 1526.98
#Mann= 17 ,-1 , 0
       0      .1       0  209.94    .025       0  315.31      .1       0
  338.24    .045       0  465.53    .025       0  505.15    .055       0
  525.27     .05       0  735.24     .05       0  800.28     .05       0
  840.23     .05       0 1261.08     .05       0 1893.77      .1       0
 1948.57     .05       0 1999.22     .06       0 2104.67     .12       0
 2210.11      .1       0 2233.46     .12       0
Bank Sta=338.24,465.53
XS Rating Curve= 0 ,0
Exp/Cntr(USF)=0,0
Exp/Cntr=0.3,0.1

Type RM Length L Ch R = 1 ,43568   ,729.3,658.8,629.2
XS GIS Cut Line= 4
  2488809.518081628850.9520107252488960.63665851628731.316470196
2489363.61953187628403.8928855912490358.48350048627471.994990947
#Sta/Elev= 30
       0 1610.07    4.641608.699   11.09 1607.27  118.361577.508   180.3 1548.57
   217.3 1526.48   262.5 1493.29   282.2 1475.05   294.1 1467.06   322.5 1440.14
  346.921431.214   386.2 1422.41  391.76 1419.14   396.4 1415.13   402.7 1414.69
   524.4 1414.76  542.441419.141  576.011419.643   615.4  1423.3  690.561423.751
   789.5 1433.31 1048.651437.383 1407.691444.438 1473.191446.743  1552.6 1451.02
 1647.061461.245  1835.5 1472.68  2006.11488.029  2053.5 1492.27  2075.1 1496.83
#Mann= 14 ,-1 , 0
       0      .1       0    4.64      .1       0   11.09      .1       0
  118.36      .1       0  346.92    .025       0  391.76    .045       0
  542.44    .025       0  576.01      .1       0  690.56     .05       0
 1048.65     .05       0 1407.69      .1       0 1473.19     .05       0
 1647.06      .1       0  2006.1     .06       0
Bank Sta=391.76,542.44
XS Rating Curve= 0 ,0
Exp/Cntr(USF)=0,0
Exp/Cntr=0.3,0.1

Type RM Length L Ch R = 1 ,42909   ,711.9,753.9,795.1
XS GIS Cut Line= 4
2489124.34845081629512.0957873312489760.30579783628920.214692084
2489854.75490878628561.3080704982490629.23761852627679.783035023
#Sta/Elev= 30
       0 1640.64    52.5 1628.68   107.3 1605.57   154.4 1577.66   210.9 1531.28
   240.3 1513.05   254.2 1498.21   318.8 1458.76   376.1 1430.61   413.1 1426.11
   440.4 1415.15   475.2 1411.61   540.3 1420.36   664.5 1422.57   857.3 1421.66
   903.2 1416.15   998.4 1421.92  1022.5 1417.47  1039.7 1411.18  1061.8 1410.47
  1105.9  1410.7 1117.171416.906  1134.9 1430.47 1214.981431.705 1812.83 1443.67
  1967.2 1456.34 2164.571481.857    2245  1491.8 2293.261503.989  2413.3 1525.22
#Mann= 7 ,-1 , 0
       0      .1       0  1022.5    .045       0 1117.17      .1       0
 1214.98     .05       0 1812.83      .1       0 2164.57     .06       0
 2293.26      .1       0
Bank Sta=1022.5,1117.17
XS Rating Curve= 0 ,0
Exp/Cntr(USF)=0,0
Exp/Cntr=0.3,0.1

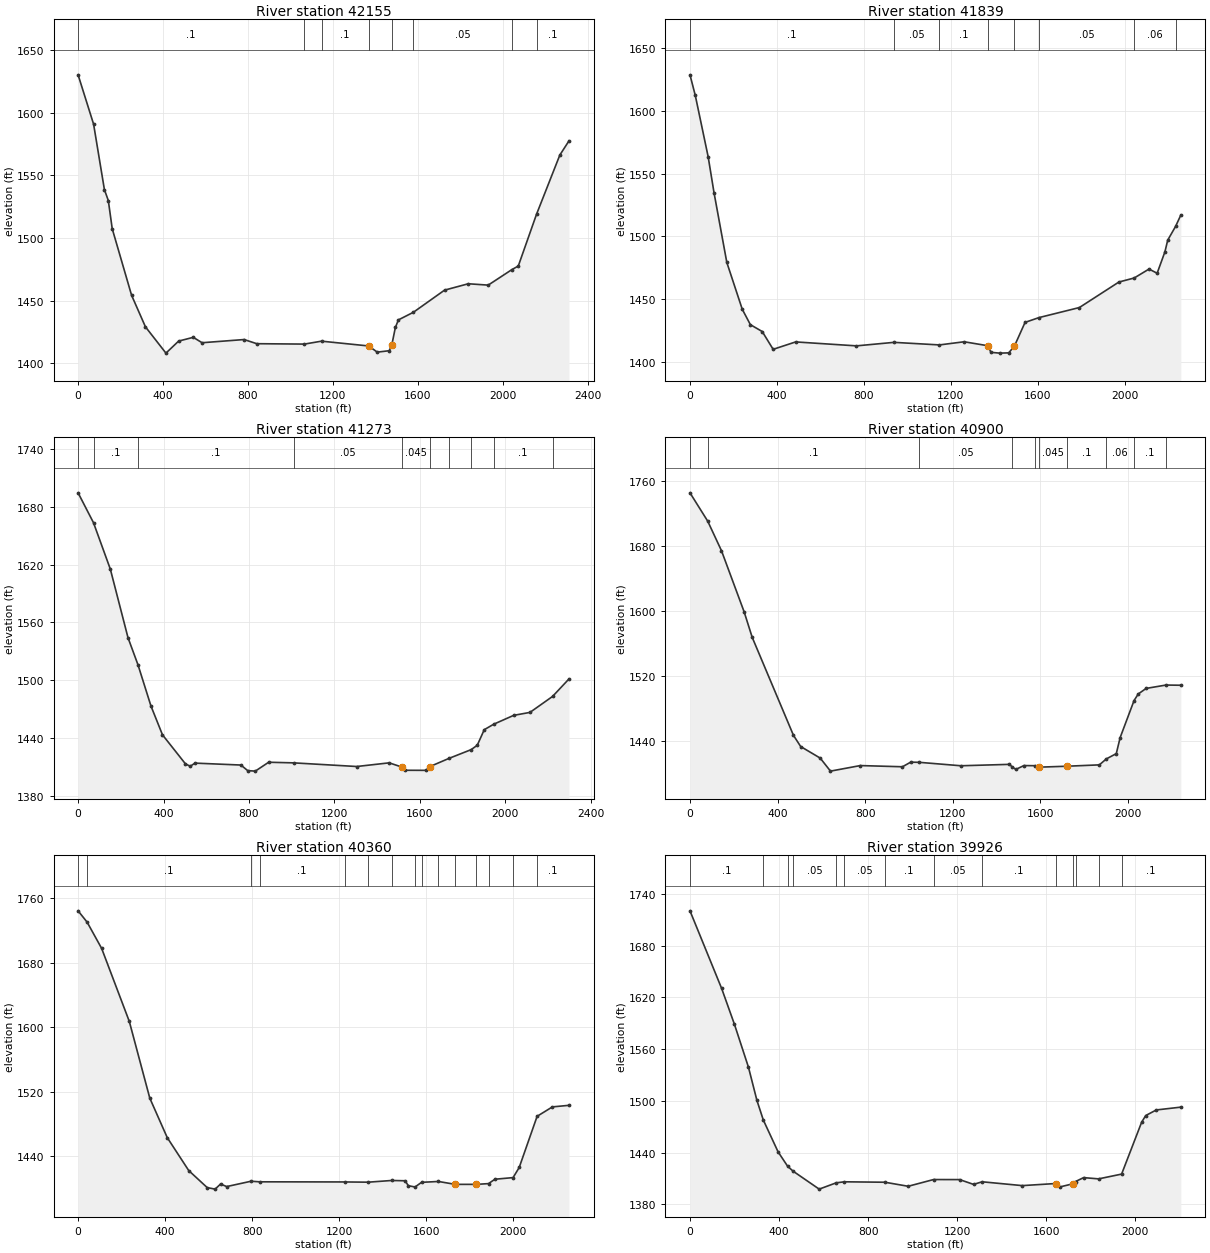
Type RM Length L Ch R = 1 ,42155   ,312.7,316.2,320
XS GIS Cut Line= 4
2489262.87381353629650.6211500482490383.66993006629014.663803027
2490648.12744071628838.3587959322491183.33906939628378.706456006
#Sta/Elev= 30
       0 1630.05    73.1 1590.65     124 1538.46   142.4 1529.77   160.8  1507.3
     252 1454.21   317.2 1429.07   413.8 1408.09   473.6 1417.69   542.5 1420.69
   583.9 1416.38   781.7 1418.92   841.8 1415.61 1065.881415.298 1146.57 1417.63
  1368.6  1413.8    1409 1408.88  1465.4 1410.01 1477.091414.223  1494.3 1428.53
  1508.7 1434.61  1578.81440.629  1725.9 1458.32  1837.7 1463.41  1931.6 1462.33
 2042.611474.651  2073.2 1477.54 2159.021518.784  2268.9 1566.06    2312 1577.38
#Mann= 8 ,-1 , 0
       0      .1       0 1065.88      .1       0 1146.57      .1       0
  1368.6    .045       0 1477.09      .1       0  1578.8     .05       0
 2042.61     .06       0 2159.02      .1       0
Bank Sta=1368.6,1477.09
XS Rating Curve= 0 ,0
Exp/Cntr(USF)=0,0
Exp/Cntr=0.3,0.1

Type RM Length L Ch R = 1 ,41839   ,560.7,565.7,571.3
XS GIS Cut Line= 4
2489388.80596146629889.8922311062490452.93261142 629329.49417284
 2490824.4324478629115.409521367 2491334.4576469628750.206292385
#Sta/Elev= 30
       0 1628.62    24.4 1612.25    83.7  1563.4   110.7 1534.76   169.5 1479.33
   240.6 1442.03     278 1429.77   332.4 1424.33   382.7 1410.16   486.3 1416.05
   766.2 1412.91  938.421415.702 1147.951413.662  1261.5 1416.17    1371    1413
  1384.8 1407.75  1425.6 1407.13  1466.6 1407.34 1493.081412.815  1541.8  1431.6
 1605.741435.404  1791.7 1443.41  1973.7 1463.73 2043.841466.919  2112.2 1474.04
  2149.5  1470.7  2185.3 1487.76  2198.2 1497.04 2234.641508.081  2258.7  1517.1
#Mann= 8 ,-1 , 0
       0      .1       0  938.42     .05       0 1147.95      .1       0
    1371    .045       0 1493.08      .1       0 1605.74     .05       0
 2043.84     .06       0 2234.64      .1       0
Bank Sta=1371,1493.08
XS Rating Curve= 0 ,0
Exp/Cntr(USF)=0,0
Exp/Cntr=0.3,0.1

Type RM Length L Ch R = 1 ,41273   ,376.8,373.6,370.5
XS GIS Cut Line= 4
2489502.14489459630425.1038597872490774.05958863 629782.84990537
2491145.55942501629606.5448982752491548.54229837 629379.86703201
#Sta/Elev= 30
       0 1694.47   72.221663.419     151 1615.31   233.7 1544.23  280.591516.008
   341.2 1473.36   395.1 1443.48   502.5 1413.39     525 1410.86   547.4 1414.12
   762.4 1412.12   794.1 1406.34   829.7 1405.81   892.3 1415.03 1009.861414.373
  1304.7  1410.6  1456.6  1414.4  1515.4 1410.07  1530.4  1406.7  1629.5 1406.62
 1646.66 1410.49 1736.811419.046 1840.311428.101    1869 1432.65  1901.7  1448.8
  1946.11454.478  2039.4 1463.66  2115.7 1466.72 2221.521483.286  2298.4 1501.44
#Mann= 10 ,-1 , 0
       0      .1       0   72.22      .1       0  280.59      .1       0
 1009.86     .05       0  1515.4    .045       0 1646.66      .1       0
 1736.81      .1       0 1840.31     .06       0  1946.1      .1       0
 2221.52      .1       0
Bank Sta=1515.4,1646.66
XS Rating Curve= 0 ,0
Exp/Cntr(USF)=0,0
Exp/Cntr=0.3,0.1

Type RM Length L Ch R = 1 ,40900   ,554.7,540.1,522.8
XS GIS Cut Line= 4
2489672.15329429630891.0528071092490767.76298123630217.315815711
2491265.19496554629952.8583050682491529.65247618629663.214364841
#Sta/Elev= 30
       0 1745.39   81.02 1710.51   143.9 1674.11   247.2 1598.98   284.1 1567.53
   472.6 1446.82   505.5 1433.05   594.7  1418.8   641.7 1402.75   777.8 1409.59
   970.4 1408.12  1007.9  1413.8 1047.661413.576  1237.4 1409.35  1458.8 1411.08
 1472.831407.642  1488.4  1404.9  1525.1 1409.59 1577.16 1409.43  1594.8 1407.63
    1722 1408.79  1869.6 1410.46 1901.38 1417.79  1946.8 1424.27  1964.6 1444.13
 2028.091489.683  2047.2 1497.74  2083.2 1504.59 2173.921508.729  2241.8 1508.49
#Mann= 10 ,-1 , 0
       0      .1       0   81.02      .1       0 1047.66     .05       0
 1472.83      .1       0 1577.16    .025       0  1594.8    .045       0
    1722      .1       0 1901.38     .06       0 2028.09      .1       0
 2173.92      .1       0
Bank Sta=1594.8,1722
XS Rating Curve= 0 ,0
Exp/Cntr(USF)=0,0
Exp/Cntr=0.3,0.1

Type RM Length L Ch R = 1 ,40360   ,419.9,433.9,445.4
XS GIS Cut Line= 4
 2489986.9836641631363.2983618282491410.01693565630475.476718957
2491611.50837233630305.4683192582491869.66927558630122.866704767
#Sta/Elev= 30
       0 1744.46   41.581730.382   108.2  1697.9   235.5 1607.25   329.7 1512.07
   409.9 1463.11   508.9 1422.16   593.8 1401.05   630.1 1399.17   655.1  1405.5
   683.3 1402.34  795.441408.971  834.59 1408.24 1226.221408.077 1333.911407.785
 1441.611409.893  1503.7 1409.54  1518.5  1403.4  1549.31401.831 1579.35 1407.61
 1656.991408.665    1734 1405.08  1831.5 1405.08 1887.071406.008  1916.6 1411.45
 2000.061413.461  2028.2 1426.01 2110.621489.547  2180.9  1501.2  2257.1 1503.14
#Mann= 15 ,-1 , 0
       0      .1       0   41.58      .1       0  795.44     .05       0
  834.59      .1       0 1226.22     .05       0 1333.91      .1       0
 1441.61      .1       0  1549.3      .1       0 1579.35      .1       0
 1656.99      .1       0    1734    .045       0  1831.5      .1       0
 1887.07     .06       0 2000.06      .1       0 2110.62      .1       0
Bank Sta=1734,1831.5
XS Rating Curve= 0 ,0
Exp/Cntr(USF)=0,0
Exp/Cntr=0.3,0.1

Type RM Length L Ch R = 1 ,39926   ,383,385.2,386.5
XS GIS Cut Line= 4
2490276.62760433 631678.128731642491441.49997263630897.349414505
2491844.48284599630702.154585222 2492165.6098232630551.036007712
#Sta/Elev= 30
       0 1720.35   142.3 1630.33   199.8 1588.76   262.6 1539.17   300.8 1500.53
  329.351477.903   395.9 1440.89   438.61424.302   463.11418.576   580.4 1397.75
   657.11405.073  693.831406.241   875.61405.738   980.1 1401.06  1094.11408.854
  1211.2  1408.8  1273.8 1403.25  1312.61406.264  1492.6 1401.82  1643.7 1404.26
  1661.5 1400.29 1722.221404.052 1731.811406.572  1768.2 1411.08 1835.461409.638
 1938.821415.172  2028.6  1475.2  2047.1 1483.04  2094.7 1489.53    2205  1492.8
#Mann= 14 ,-1 , 0
       0      .1       0  329.35     .05       0   438.6      .1       0
   463.1     .05       0   657.1      .1       0  693.83     .05       0
   875.6      .1       0  1094.1     .05       0  1312.6      .1       0
  1643.7    .045       0 1722.22      .1       0 1731.81     .06       0
 1835.46      .1       0 1938.82      .1       0
Bank Sta=1643.7,1722.22
XS Rating Curve= 0 ,0
Exp/Cntr(USF)=0,0
Exp/Cntr=0.3,0.1

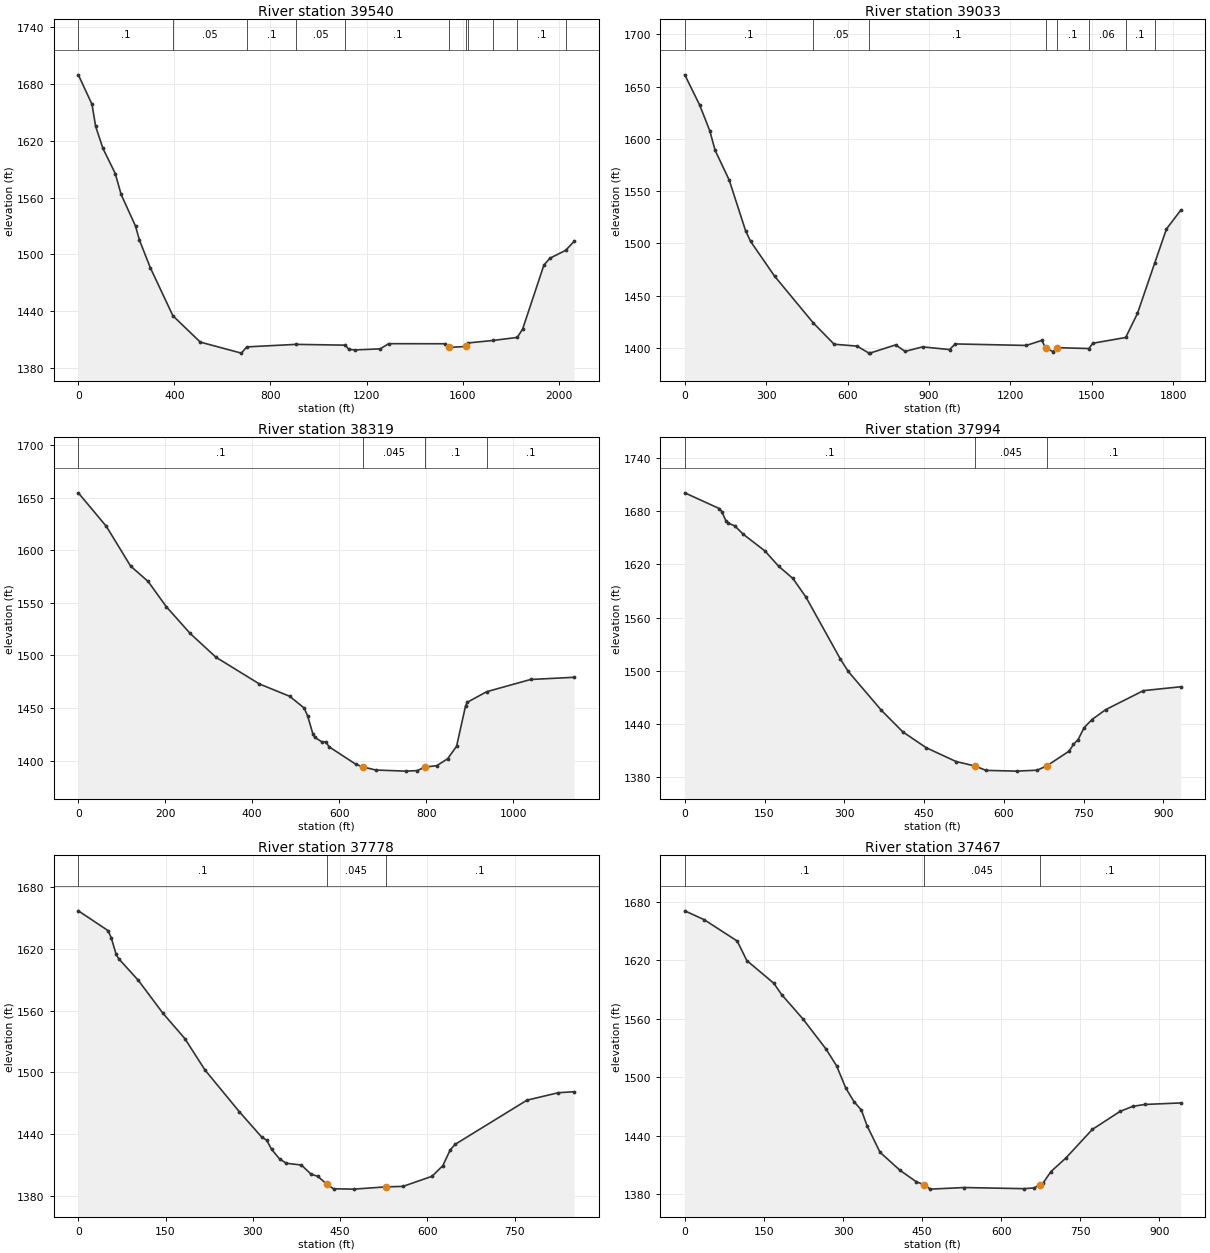
Type RM Length L Ch R = 1 ,39540   ,485.3,507.5,526.7
XS GIS Cut Line= 4
2490408.85635965631759.9846277912491592.61855014631237.366213903
 2492001.8980309631061.0612068082492310.43179331630960.315488468
#Sta/Elev= 30
       0 1689.68    56.9 1658.54      72 1635.29   102.6 1611.87   153.9 1585.31
   178.2 1563.25   238.2 1529.78     254 1515.34   299.4 1486.04  393.731435.095
   507.8 1407.26   678.7 1395.63  701.231402.221   906.51404.886 1111.771404.055
  1125.8 1399.59    1152 1399.04    1257 1400.14  1291.9 1405.61  1527.1 1405.53
  1544.6 1401.66 1615.37 1402.71 1624.181406.423 1726.581409.028 1827.341412.237
  1849.9 1421.17  1938.3 1488.73  1963.5 1495.94 2028.371504.151  2064.2 1513.77
#Mann= 11 ,-1 , 0
       0      .1       0  393.73     .05       0  701.23      .1       0
   906.5     .05       0 1111.77      .1       0  1544.6    .045       0
 1615.37      .1       0 1624.18     .06       0 1726.58      .1       0
 1827.34      .1       0 2028.37     .12       0
Bank Sta=1544.6,1615.37
XS Rating Curve= 0 ,0
Exp/Cntr(USF)=0,0
Exp/Cntr=0.3,0.1

Type RM Length L Ch R = 1 ,39033   ,764.5,714.1,694.8
XS GIS Cut Line= 4
2490547.38172237 631879.620168322491454.09318743631508.120331941
2492014.49124569 631627.755872472492278.94875633631703.315161225
#Sta/Elev= 30
       0 1661.34    55.3 1632.13    92.1 1607.75   111.7 1589.11   163.6 1560.63
   223.9 1512.25   242.3 1501.95   331.2 1468.49  473.921423.712   550.5 1403.37
   634.8  1401.6  677.831395.045   682.3 1394.86   777.4 1402.77     812 1396.52
   876.8 1400.84   976.2 1398.26   996.9 1403.67  1258.7 1402.22  1315.9 1407.01
  1329.9 1400.11  1356.9 1396.35  1373.7 1400.07 1489.781399.252  1504.1 1404.33
 1625.361409.826  1668.9 1432.95    17321480.877  1775.8 1513.78  1827.9 1531.57
#Mann= 8 ,-1 , 0
       0      .1       0  473.92     .05       0  677.83      .1       0
  1329.9    .045       0  1373.7      .1       0 1489.78     .06       0
 1625.36      .1       0    1732      .1       0
Bank Sta=1329.9,1373.7
XS Rating Curve= 0 ,0
Exp/Cntr(USF)=0,0
Exp/Cntr=0.3,0.1

Type RM Length L Ch R = 1 ,38319   ,355.6,324.5,308.2
XS GIS Cut Line= 4
2490610.34779633631955.1794570752491044.81370667631942.586242282
2491517.05926139632062.221782811 2491661.8812315632225.933575114
#Sta/Elev= 30
       0 1654.46    64.4 1622.63   120.4  1584.8   160.5  1570.3     202 1546.48
   257.3 1520.85   316.5 1498.32   416.3 1472.94   486.2 1461.18   519.2 1450.11
   527.4  1442.6   539.8 1424.96   543.9 1422.24   560.4 1417.79   568.7 1418.04
   576.9 1413.19   638.8 1396.48  655.351394.018   684.2 1391.16   752.6 1390.11
   779.1 1390.58  797.921394.018   824.5 1395.29   849.3 1401.85   869.9 1413.65
   890.5 1451.82   894.7 1455.53  939.21 1465.56  1040.2 1477.15  1140.4 1479.25
#Mann= 4 ,-1 , 0
       0      .1       0  655.35    .045       0  797.92      .1       0
  939.21      .1       0
Bank Sta=655.35,797.92
XS Rating Curve= 0 ,0
Exp/Cntr(USF)=0,0
Exp/Cntr=0.3,0.1

Type RM Length L Ch R = 1 ,37994   ,238.2,216.1,199.6
XS GIS Cut Line= 4
2490742.57655165632427.4250117942491095.18656584632364.458937831
2491510.76265399 632332.97590085 2491661.8812315632288.899649076
#Sta/Elev= 30
       0 1700.89    65.2 1683.02    69.6 1679.58    77.4 1669.21    81.4 1666.67
    93.6 1663.72   109.9 1654.14   150.5 1635.36   176.4 1618.05   203.3 1604.15
   227.7 1583.26   292.7 1513.02   307.4 1499.13   369.8 1455.21   409.9 1430.94
     454 1413.02   510.2 1397.39  545.751392.379   566.3 1387.43     624 1386.58
   662.6 1387.64  680.37 1392.38   722.8 1409.21   730.8 1416.76   739.6 1422.14
   750.9 1435.67   765.7 1444.85   791.6 1456.06   862.4 1477.48   932.4 1481.85
#Mann= 3 ,-1 , 0
       0      .1       0  545.75    .045       0  680.37      .1       0
Bank Sta=545.75,680.37
XS Rating Curve= 0 ,0
Exp/Cntr(USF)=0,0
Exp/Cntr=0.3,0.1

Type RM Length L Ch R = 1 ,37778   ,320,311.1,317.8
XS GIS Cut Line= 4
2490969.25441791632710.7723446252491240.00853595632616.323233681
2491617.80497973632477.7978709632491762.62694984632402.238582209
#Sta/Elev= 30
       0 1657.23    51.3 1637.91    56.7 1630.71    65.1 1614.74    69.4 1610.63
   103.3 1589.46   145.6 1557.45   183.2 1532.83   217.6 1502.42   276.9 1461.63
   315.2 1437.08   323.8 1433.98   332.3 1425.08   346.1 1415.68   357.8 1411.49
   383.5 1409.82   400.4 1400.76   411.6 1398.87  427.66 1390.99   438.8 1386.68
   473.9 1386.34   528.3 1388.52   558.2 1389.01     608 1398.81   626.7 1409.18
   639.1  1424.2   647.5 1429.82   771.4 1472.94   825.4 1480.19   852.5 1481.15
#Mann= 3 ,-1 , 0
       0      .1       0  427.66    .045       0   528.3      .1       0
Bank Sta=427.66,528.3
XS Rating Curve= 0 ,0
Exp/Cntr(USF)=0,0
Exp/Cntr=0.3,0.1

Type RM Length L Ch R = 1 ,37467   ,315,307.9,304.3
XS GIS Cut Line= 4
2491076.29674365633031.8993218332491403.72032826632912.263781304
2491800.40659422632698.1791298322491863.37266818632572.246981907
#Sta/Elev= 30
       0 1670.57    36.7 1661.51    99.4 1639.63   117.6 1619.61   168.7 1596.42
   183.6 1584.79   224.1 1559.75   267.8 1528.95   287.9 1511.72   305.2 1489.07
   320.8 1475.12   334.8 1466.48   345.8 1450.17   370.2 1423.25   407.9 1404.79
   438.4 1393.23   454.31389.766   465.7 1385.45   529.3 1387.08   642.9 1385.93
   661.8 1386.65  673.281389.766     680 1392.16   694.3 1403.44   722.1 1417.04
   772.6 1446.54   825.4 1465.09   849.3 1470.24   872.1 1472.18   940.2 1473.76
#Mann= 3 ,-1 , 0
       0      .1       0   454.3    .045       0  673.28      .1       0
Bank Sta=454.3,673.28
XS Rating Curve= 0 ,0
Exp/Cntr(USF)=0,0
Exp/Cntr=0.3,0.1

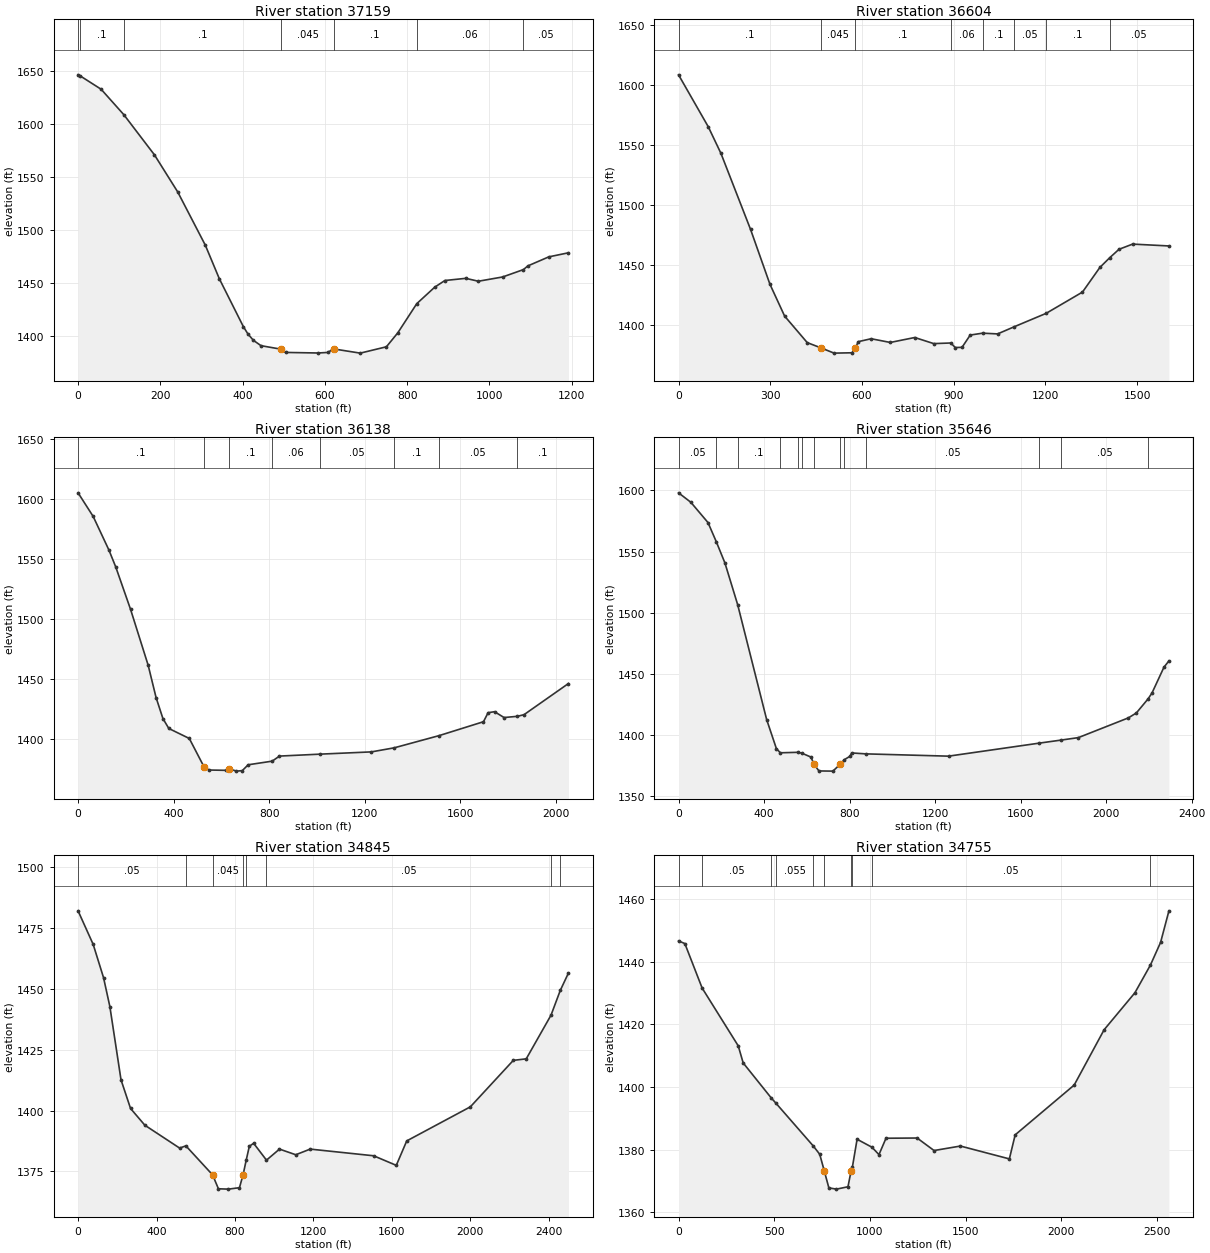
Type RM Length L Ch R = 1 ,37159   ,535.2,555.3,576
XS GIS Cut Line= 4
2491252.60175075633378.2127286272491523.35586878633227.094151117
2491857.07606079632994.1196774562492108.94035664632591.136804096
#Sta/Elev= 30
       0 1646.37    5.681645.245    56.1 1632.77  111.341608.775   185.7 1570.96
   242.2 1536.06   309.4 1485.82   343.5 1454.15     402 1408.96   413.2 1402.02
   426.4 1396.11   444.8 1391.09  494.421387.719   504.5 1384.73     583  1384.2
   606.9  1384.7   621.5 1388.02   686.1 1384.07   749.7 1390.04   777.5 1403.26
  823.551430.699   867.1 1446.21   891.9 1452.52   942.6 1454.56   973.2 1451.83
  1032.2 1455.84 1082.871462.806  1093.5 1466.26  1144.4 1474.79  1192.3 1478.64
#Mann= 7 ,-1 , 0
       0     .12       0    5.68      .1       0  111.34      .1       0
  494.42    .045       0   621.5      .1       0  823.55     .06       0
 1082.87     .05       0
Bank Sta=494.42,621.5
XS Rating Curve= 0 ,0
Exp/Cntr(USF)=0,0
Exp/Cntr=0.3,0.1

Type RM Length L Ch R = 1 ,36604   ,461.6,465.8,470.8
XS GIS Cut Line= 4
2491435.20336524633762.3057797982491812.99980901633636.373631873
2492247.46571935633504.1448765522492921.20271075633170.424684551
#Sta/Elev= 30
       0 1608.28    97.2    1565   138.7  1542.8   235.6 1479.41   298.9 1433.76
     347 1407.17     421 1385.06  465.481380.707   508.8  1376.3   567.3 1376.59
   578.31380.708   588.2 1385.87     630  1388.3   692.7  1385.2   772.7 1389.32
   834.9 1384.23  890.671384.756   905.1 1380.99   927.3 1381.11   954.2 1391.37
  994.611392.939  1043.8 1392.32 1098.541398.332 1202.471409.451  1321.4 1427.19
  1378.3 1447.73 1410.331455.795  1440.9 1462.85  1485.4 1467.18  1604.2 1465.64
#Mann= 8 ,-1 , 0
       0      .1       0  465.48    .045       0   578.3      .1       0
  890.67     .06       0  994.61      .1       0 1098.54     .05       0
 1202.47      .1       0 1410.33     .05       0
Bank Sta=465.48,578.3
XS Rating Curve= 0 ,0
Exp/Cntr(USF)=0,0
Exp/Cntr=0.3,0.1

Type RM Length L Ch R = 1 ,36138   ,494.3,492.3,489
XS GIS Cut Line= 4
2491472.98300961634184.1784753472491875.96588297634089.729364403
2492385.99108207 633976.390431272493399.74487287633510.441483948
#Sta/Elev= 30
       0 1604.91    63.4 1585.22   129.2 1557.28   157.9 1543.15   219.6 1508.02
   293.5 1461.39   326.4 1434.64   355.1 1417.14   379.8 1408.88   465.5 1400.57
   527.4 1376.85   547.9 1374.32   617.5 1374.06   629.8 1375.56   662.6  1373.4
   687.2 1373.81   711.8 1378.68  812.28 1381.69   842.9 1385.92 1013.931387.536
  1227.6 1389.41 1323.091392.791 1510.931402.944  1696.6  1414.5  1715.8    1422
  1742.8 1422.84  1782.6 1417.98 1838.341418.993  1866.1 1420.35  2052.1 1446.28
#Mann= 8 ,-1 , 0
       0      .1       0   527.4    .045       0   629.8      .1       0
  812.28     .06       0 1013.93     .05       0 1323.09      .1       0
 1510.93     .05       0 1838.34      .1       0
Bank Sta=527.4,629.8
XS Rating Curve= 0 ,0
Exp/Cntr(USF)=0,0
Exp/Cntr=0.3,0.1

Type RM Length L Ch R = 1 ,35646   ,814.4,801.1,789.5
XS GIS Cut Line= 4
 2491498.1694392634713.0934966312491945.22856433634587.161348706
2492480.44019301634442.3393785932493664.20238351633970.093823874
#Sta/Elev= 30
       0    1598    57.4  1590.3   137.7 1573.71  176.331558.136   216.7  1540.8
  276.291506.749     412 1412.78   457.7 1388.96  476.211385.605  557.031385.987
  576.061385.338   619.4 1382.08  633.741376.111   656.6 1370.78   721.9 1370.62
  755.131376.112  775.761380.021   801.7 1382.77     810 1385.47  875.611384.722
  1262.6 1382.85 1686.831393.492 1788.581395.969  1869.8    1398  2103.9 1414.14
  2141.1 1418.16 2195.551429.583  2214.3 1434.49  2270.1 1455.53  2293.4  1460.7
#Mann= 13 ,-1 , 0
       0     .05       0  176.33      .1       0  276.29      .1       0
  476.21     .05       0  557.03      .1       0  576.06     .05       0
  633.74    .045       0  755.13      .1       0  775.76     .06       0
  875.61     .05       0 1686.83      .1       0 1788.58     .05       0
 2195.55      .1       0
Bank Sta=633.74,755.13
XS Rating Curve= 0 ,0
Exp/Cntr(USF)=0,0
Exp/Cntr=0.5,0.3

Type RM Length L Ch R = 1 ,34845   ,88.4,90.3,92.6
XS GIS Cut Line= 4
2491650.58369079635494.0545768742492112.19618666635419.286385462
2492595.07480028635204.4106366192493948.84539044634549.563467413
#Sta/Elev= 30
       0 1482.12    77.2  1468.3   129.8 1454.67   162.2 1442.75     219 1412.65
   267.6 1400.88   340.5    1394   517.8  1384.6   549.71385.513   685.71373.604
   715.6 1367.87   766.8 1367.73   822.8 1368.32  841.261373.605  857.841379.876
   873.2 1385.35   895.1 1386.57  960.551379.639  1026.9 1384.18  1109.9 1381.86
  1183.4 1384.18  1506.8 1381.44  1622.3  1377.5  1675.6 1387.55    2000 1401.56
  2218.9 1420.66  2284.8 1421.28 2411.151439.238 2458.341449.4052499.993 1456.56
#Mann= 8 ,-1 , 0
       0     .05       0   549.7     .06       0   685.7    .045       0
  841.26    .025       0  857.84    .055       0  960.55     .05       0
 2411.15      .1       0 2458.34      .1       0
Bank Sta=685.7,841.26
XS Rating Curve= 0 ,0
Exp/Cntr(USF)=0,0
Exp/Cntr=0.5,0.3

Type RM Length L Ch R = 1 ,34755   ,640.7,644.9,648.3
XS GIS Cut Line= 4
2491737.19618669635856.7863854622492212.89063111635467.897496581
2492667.75174224635276.9252743422493969.83507559634627.619718805
#Sta/Elev= 30
       0 1446.61      33 1445.75  123.231431.577     312 1413.13   337.8 1407.69
  485.511396.439  508.251394.898  703.971381.206   737.9 1378.55  761.371373.294
   785.6 1367.83   825.4 1367.44   885.4 1368.19  901.891373.292   908.31374.389
   933.1 1383.35 1010.471380.811  1047.4 1378.45  1084.1 1383.67  1246.8 1383.74
  1335.2 1379.75  1473.1 1381.18  1728.9 1377.08  1759.2 1384.75  2067.6 1400.63
    2224 1418.27    2385 1430.07 2466.08 1438.91  2519.1 1446.132562.749  1456.2
#Mann= 10 ,-1 , 0
       0      .1       0  123.23     .05       0  485.51     .06       0
  508.25    .055       0  703.97     .05       0  761.37    .045       0
  901.89     .06       0   908.3    .055       0 1010.47     .05       0
 2466.08      .1       0
Bank Sta=761.37,901.89
XS Rating Curve= 0 ,0
Exp/Cntr(USF)=0,0
Exp/Cntr=0.5,0.3

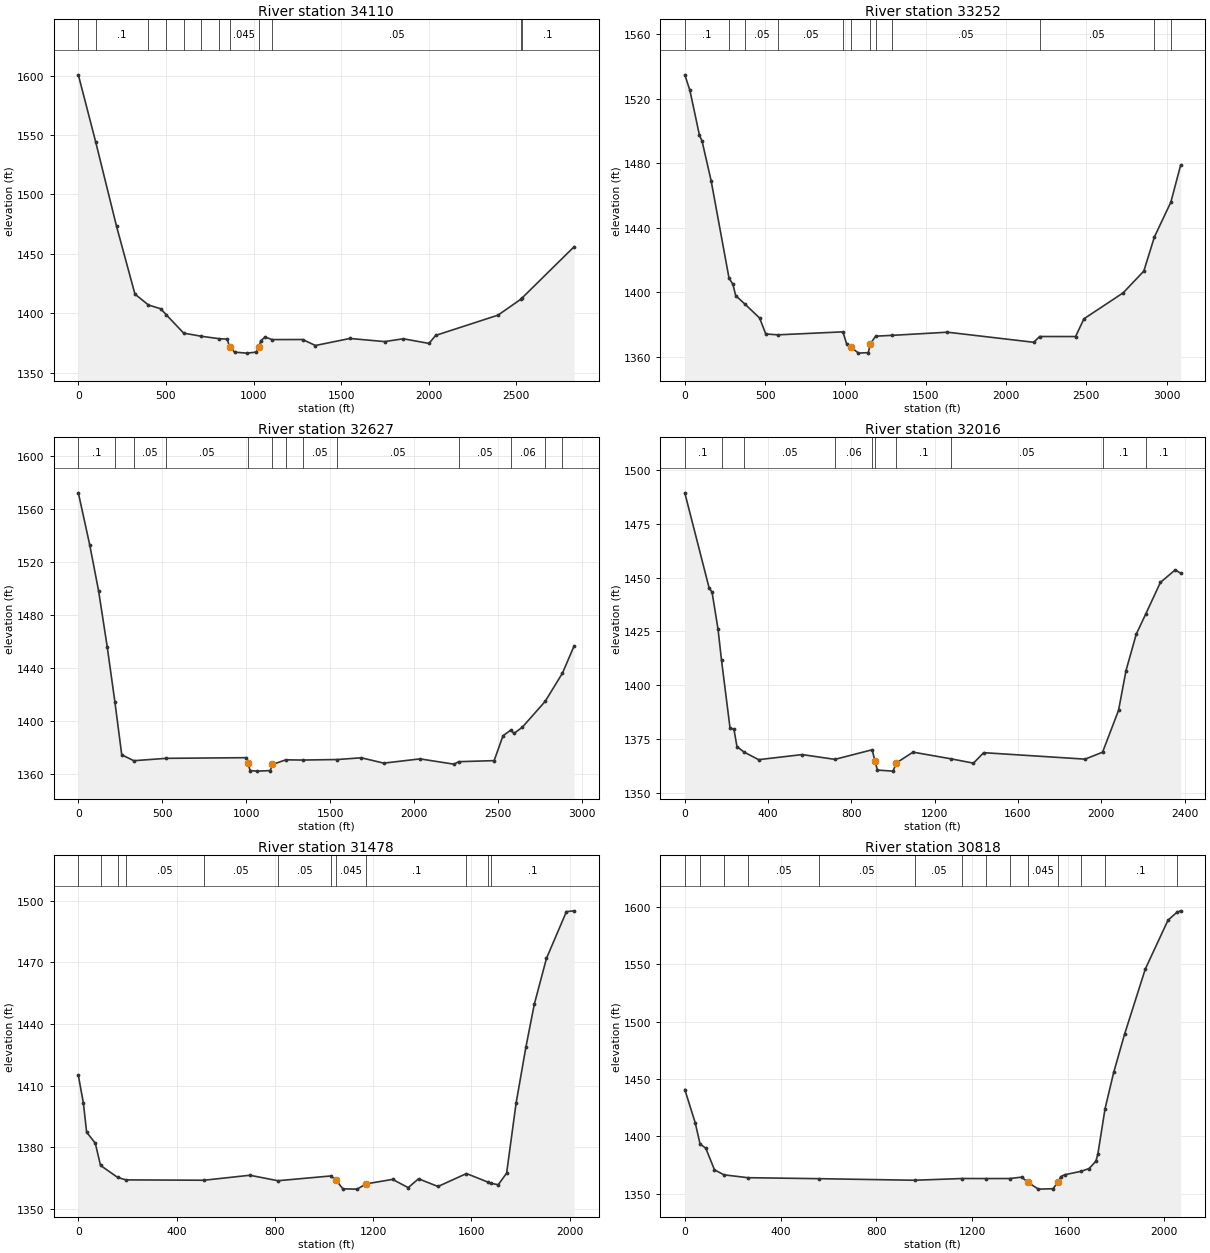
Type RM Length L Ch R = 1 ,34110   ,860.8,857.5,854.6
XS GIS Cut Line= 4
2491731.14391286636287.2453456932492417.47411905636066.864086824
2492870.82985158635903.1522945222494388.31223408635317.567806671
#Sta/Elev= 30
       0 1600.78   98.931544.335     218 1473.24   323.1 1416.11  400.261406.928
   470.1 1403.76   500.7 1398.88  601.141383.252  701.581380.619  802.521378.573
   849.9 1378.18  863.211371.451   892.3 1367.23   960.4  1366.4  1015.6 1367.22
  1030.11371.452  1041.2 1376.86  1065.5 1379.95 1105.681377.813  1279.9 1377.86
  1352.8 1372.82  1549.5 1378.74    1748 1376.12  1854.5 1378.49  2001.2 1374.56
  2038.8 1381.31  2394.7 1398.38 2526.161411.892 2530.031412.547  2829.4 1456.05
#Mann= 12 ,-1 , 0
       0      .1       0   98.93      .1       0  400.26     .05       0
   500.7     .06       0  601.14     .05       0  701.58    .025       0
  802.52     .05       0  863.21    .045       0  1030.1     .06       0
 1105.68     .05       0 2526.16      .1       0 2530.03      .1       0
Bank Sta=863.21,1030.1
XS Rating Curve= 0 ,0
Exp/Cntr(USF)=0,0
Exp/Cntr=0.3,0.1

Type RM Length L Ch R = 1 ,33252   ,624.2,625.3,626.4
XS GIS Cut Line= 4
2491901.15231256637175.0669885642492732.30448886636872.829833544
2493393.44826547636602.0757155052494766.10867785636029.084442447
#Sta/Elev= 30
       0 1534.67    31.5 1525.16    91.1 1497.31   107.5 1493.63   163.7  1469.2
  275.571408.626   299.6 1405.03   316.6 1397.98  376.671392.488   465.6 1384.11
   503.9 1374.22  578.861373.678  984.091375.526  1007.4 1368.06    1035    1366
    1081 1362.35  1142.1 1362.68    1155 1368.17 1187.991372.847 1289.951373.354
  1634.9 1375.31  2172.4 1369.06 2208.491372.645  2432.5 1372.62  2484.5 1383.61
  2728.6 1399.67  2857.2 1413.16 2923.291434.347  3025.41455.807  3086.3 1478.71
#Mann= 12 ,-1 , 0
       0      .1       0  275.57     .06       0  376.67     .05       0
  578.86     .05       0  984.09    .025       0    1035    .045       0
    1155      .1       0 1187.99     .06       0 1289.95     .05       0
 2208.49     .05       0 2923.29      .1       0  3025.4      .1       0
Bank Sta=1035,1155
XS Rating Curve= 0 ,0
Exp/Cntr(USF)=0,0
Exp/Cntr=0.3,0.1

Type RM Length L Ch R = 1 ,32627   ,631.3,610.8,581.9
XS GIS Cut Line= 4
 2492159.3132158637779.5412986042493053.43146607637414.338069621
2493487.89737641637244.3296699232494866.85439619636602.075715505
#Sta/Elev= 30
       0 1571.92    67.6 1532.85   120.4 1498.22   172.2 1455.77  217.511414.574
   258.6 1374.46  330.231369.997  523.311371.786  1001.6 1372.28 1010.571368.616
  1023.1 1362.59  1063.1 1362.14  1143.3 1362.54  1156.2 1367.17 1235.931370.653
 1337.521370.493 1542.421370.883  1685.5  1372.2  1819.4 1368.17  2035.6 1371.37
  2238.6 1367.36  2264.81369.255  2476.9 1370.06  2529.8 1388.81 2574.391392.931
    2596 1390.64  2644.6 1395.21 2780.781414.689 2883.981436.053  2953.6  1456.6
#Mann= 13 ,-1 , 0
       0      .1       0  217.51     .06       0  330.23     .05       0
  523.31     .05       0 1010.57    .045       0  1156.2      .1       0
 1235.93     .06       0 1337.52     .05       0 1542.42     .05       0
  2264.8     .05       0 2574.39     .06       0 2780.78      .1       0
 2883.98      .1       0
Bank Sta=1010.57,1156.2
XS Rating Curve= 0 ,0
Exp/Cntr(USF)=0,0
Exp/Cntr=0.3,0.1

Type RM Length L Ch R = 1 ,32016   ,543,538.4,536
XS GIS Cut Line= 4
2492713.41466667638396.6088234362493412.33808766 637936.95648351
2493626.42273913637748.0582616222494753.51546306637187.660203356
#Sta/Elev= 30
       0 1489.51   116.5 1445.35   130.9 1443.27   159.6 1426.05  176.391411.508
     217 1380.22   236.2 1379.37   250.6 1371.36   285.2 1368.83   354.6 1365.33
   563.7 1367.69  720.471365.464   899.9 1369.94   912.2 1364.92   925.1 1360.47
   999.8 1359.99  1015.8  1363.8  1095.8 1368.83 1278.141365.719    1386  1363.7
  1435.1 1368.58    1922 1365.57 2005.99  1368.8  2082.8 1388.31  2118.6  1406.8
  2167.7 1423.73 2213.951433.247  2283.7 1447.81  2355.3 1453.68  2380.8 1452.05
#Mann= 10 ,-1 , 0
       0      .1       0  176.39     .06       0   285.2     .05       0
  720.47     .06       0   899.9     .05       0   912.2    .045       0
  1015.8      .1       0 1278.14     .05       0 2005.99      .1       0
 2213.95      .1       0
Bank Sta=912.2,1015.8
XS Rating Curve= 0 ,0
Exp/Cntr(USF)=0,0
Exp/Cntr=0.3,0.1

Type RM Length L Ch R = 1 ,31478   ,622.8,659.7,704.5
XS GIS Cut Line= 4
2492940.09253294638711.4391932482493821.61756841638302.159712492
2494035.70221989638081.7784536242494728.32903347637823.617550377
#Sta/Elev= 30
       0 1414.95    20.6 1401.54    33.8 1387.34    69.1 1382.01   90.291371.206
  159.781365.392  193.451364.167  511.931363.996   698.1 1366.42  812.42 1363.76
 1028.091366.079  1048.6 1364.09  1076.8 1359.81  1134.3 1359.67    1173 1362.26
  1279.1  1364.4  1342.8 1360.41  1384.8 1364.69  1464.1 1360.95 1579.991367.251
 1665.611363.163 1681.251362.476  1709.3  1361.8  1743.4 1367.46  1781.8 1401.37
  1821.7 1428.64    1856 1449.54  1905.6  1471.9  1986.8 1494.63  2018.3 1495.02
#Mann= 12 ,-1 , 0
       0     .06       0   90.29     .05       0  159.78     .06       0
  193.45     .05       0  511.93     .05       0  812.42     .05       0
 1028.09    .025       0  1048.6    .045       0    1173      .1       0
 1579.99      .1       0 1665.61     .05       0 1681.25      .1       0
Bank Sta=1048.6,1173
XS Rating Curve= 0 ,0
Exp/Cntr(USF)=0,0
Exp/Cntr=0.3,0.1

Type RM Length L Ch R = 1 ,30818   ,492.1,496.9,499.7
XS GIS Cut Line= 4
2492883.42306637638837.3713411732494123.85472343638717.735800645
2494526.83759679638648.4731192862494929.82047015638547.727400946
#Sta/Elev= 30
       0 1440.84    43.5 1411.86   63.841393.295    87.7 1389.66   123.9 1370.82
  163.361366.458  262.881363.948  561.45 1363.08  959.531361.712 1158.581363.224
 1258.071363.196 1357.391363.216    1407 1364.44 1432.44 1359.98  1476.3 1353.97
  1537.3 1354.31 1558.541359.978  1569.8 1364.81    1586 1366.48 1655.351369.544
    1688 1371.89  1716.8 1378.29  1725.1 1384.85 1755.021424.216    1791  1455.8
  1836.4 1489.06    1923 1545.93  2017.8 1588.52 2054.021595.249  2070.5 1596.68
#Mann= 14 ,-1 , 0
       0      .1       0   63.84     .06       0  163.36     .05       0
  262.88     .05       0  561.45     .05       0  959.53     .05       0
 1158.58      .1       0 1258.07    .025       0 1357.39      .1       0
 1432.44    .045       0 1558.54      .1       0 1655.35      .1       0
 1755.02      .1       0 2054.02     .12       0
Bank Sta=1432.44,1558.54
XS Rating Curve= 0 ,0
Exp/Cntr(USF)=0,0
Exp/Cntr=0.3,0.1