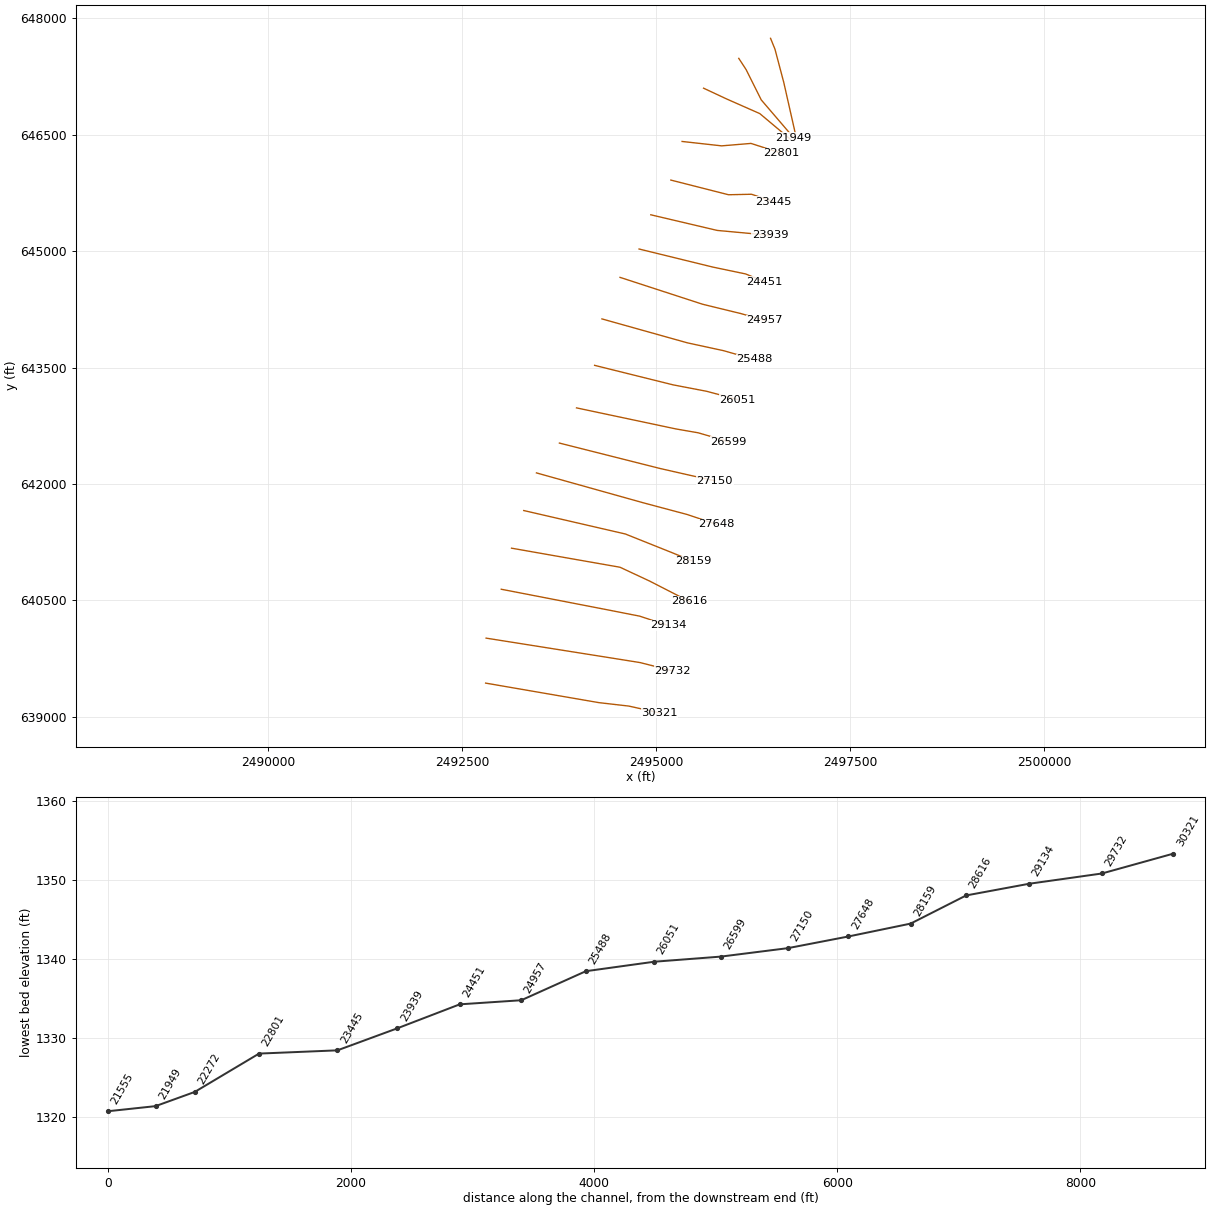
HEC-RAS study SFSBPOTOMC.prj: SFSBPOTOMC

--- SFSBPOTOMC.g01 (geometry) --- (continued)

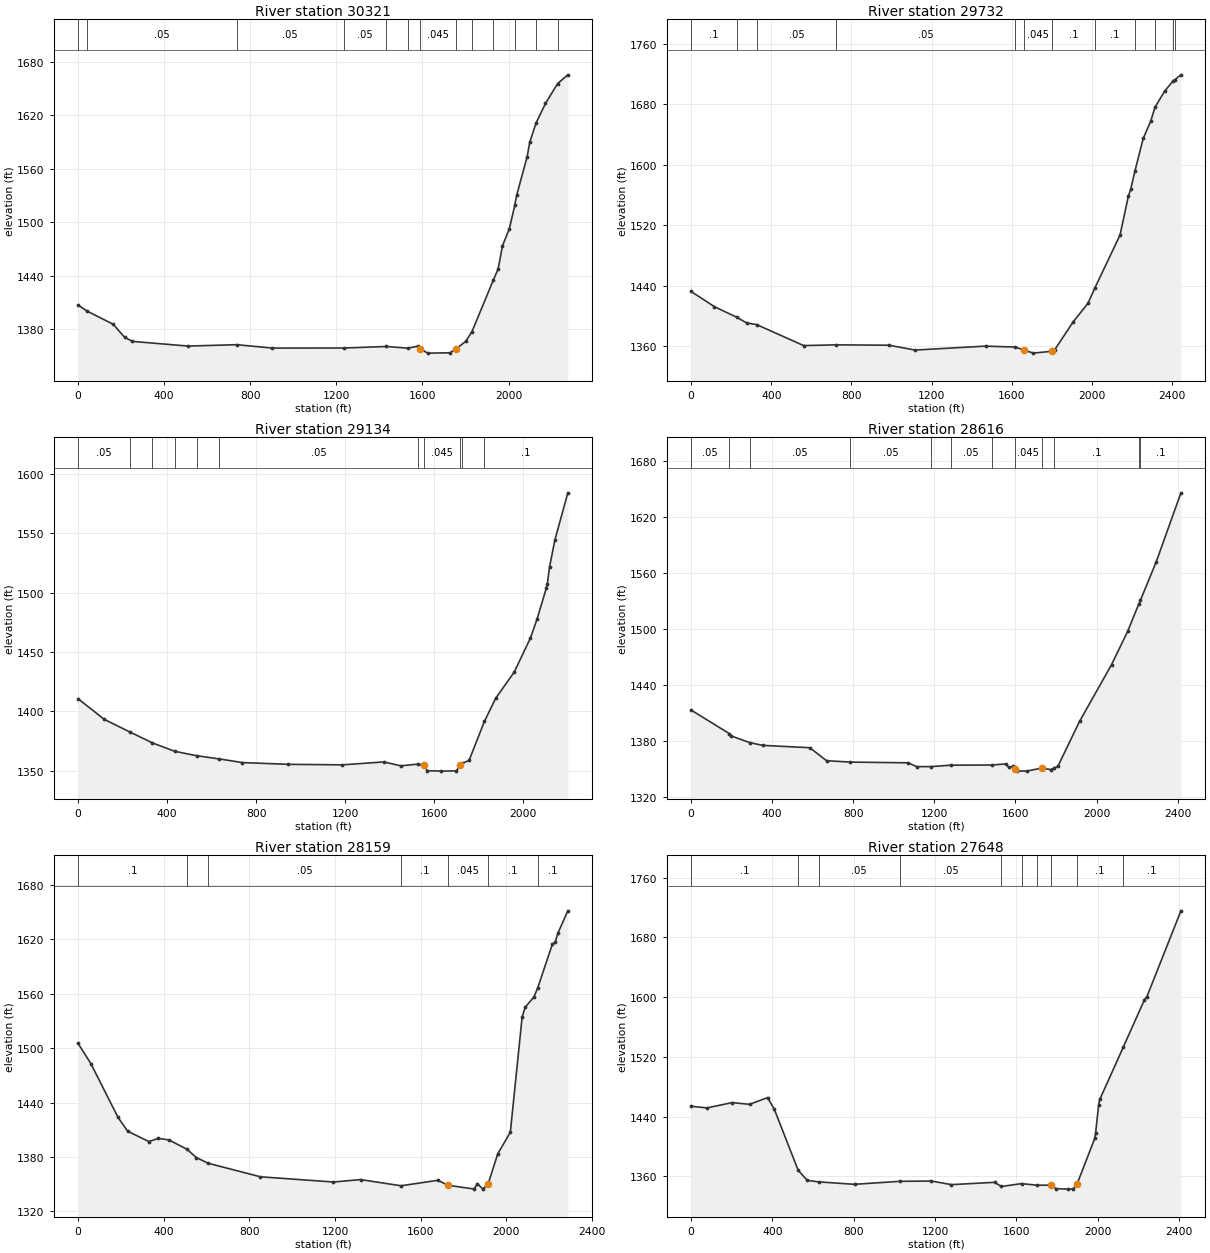
Type RM Length L Ch R = 1 ,30321   ,591.2,588.6,584.7
XS GIS Cut Line= 4
2492801.56717022639435.5490438172494262.38008615639183.684747967
2494646.47313732639139.6084961932495043.15940329639051.455992646
#Sta/Elev= 30
       0 1407.25    41.61400.512   163.6 1385.67   216.3 1371.11   252.9 1366.51
   510.7 1361.26  736.841362.812   903.1 1359.04 1233.441359.082 1432.081360.796
 1531.451358.946  1579.4 1361.14 1590.341358.404  1623.7 1353.36  1728.3 1353.75
 1757.361358.402  1800.8  1366.5 1829.72 1377.34 1929.181435.213  1951.2 1447.38
  1971.7 1473.59  2003.9 1492.95 2028.661518.823  2037.4 1530.08  2086.4 1573.56
  2098.7 1590.07 2128.141611.458  2171.5 1633.16 2227.621655.315  2275.3 1665.18
#Mann= 13 ,-1 , 0
       0    .055       0    41.6     .05       0  736.84     .05       0
 1233.44     .05       0 1432.08    .025       0 1531.45     .05       0
 1590.34    .045       0 1757.36      .1       0 1829.72      .1       0
 1929.18      .1       0 2028.66     .12       0 2128.14      .1       0
 2227.62     .12       0
Bank Sta=1590.34,1757.36
XS Rating Curve= 0 ,0
Exp/Cntr(USF)=0,0
Exp/Cntr=0.3,0.1

Type RM Length L Ch R = 1 ,29732   ,600.1,598.4,594
XS GIS Cut Line= 4
2492807.86377762640014.8369242722494356.82919709639769.269235818
2494791.29510744639700.0065544592495213.16780298639592.964228723
#Sta/Elev= 30
       0 1432.42   116.3 1412.31  227.41 1398.35   278.3 1390.64  326.721388.616
   561.8 1360.81  723.981361.822   987.1  1361.3  1116.7 1354.91    1469 1360.11
 1617.821358.875  1662.9 1354.61  1707.5 1350.84  1799.1 1353.32  1799.1 1353.33
  1813.3 1355.05  1906.4 1392.42  1979.4  1416.6 2015.111437.596  2139.8 1507.24
    2181 1558.25  2193.4 1568.17 2214.511592.311  2255.3 1634.98  2292.4 1657.58
 2314.21  1676.3  2362.6 1697.77 2402.391710.387  2413.91712.933  2443.5  1719.2
#Mann= 12 ,-1 , 0
       0      .1       0  227.41     .06       0  326.72     .05       0
  723.98     .05       0 1617.82    .025       0  1662.9    .045       0
  1799.1      .1       0 2015.11      .1       0 2214.51      .1       0
 2314.21     .12       0 2402.39      .1       0  2413.9     .12       0
Bank Sta=1662.9,1799.1
XS Rating Curve= 0 ,0
Exp/Cntr(USF)=0,0
Exp/Cntr=0.3,0.1

Type RM Length L Ch R = 1 ,29134   ,532.2,517.8,495.6
XS GIS Cut Line= 4
 2493003.0586069640644.4976638962494400.90544887640373.743545858
2494784.99850004640298.1842571032495150.20172902640178.548716574
#Sta/Elev= 30
       0 1410.61   117.8 1393.19  234.921382.352  334.281373.343  433.641366.286
     5331362.536  632.361359.874   738.4 1356.75   944.9 1355.27  1186.4 1354.84
  1373.2 1357.29  1450.2 1354.01 1526.631355.462  1553.9 1354.44  1568.4 1349.92
  1632.2 1349.54  1698.8 1349.79  1717.4 1354.61 1725.371356.131  1755.9 1358.53
 1824.851391.398    1876 1411.12  1958.8 1433.03  2031.8 1461.87  2061.3 1477.73
  2103.3 1504.01  2107.8 1507.56  2117.3 1521.56  2141.2  1544.3  2199.6 1584.23
#Mann= 11 ,-1 , 0
       0     .05       0  234.92     .06       0  334.28     .05       0
  433.64     .05       0     533     .05       0  632.36     .05       0
 1526.63    .025       0  1553.9    .045       0  1717.4    .025       0
 1725.37      .1       0 1824.85      .1       0
Bank Sta=1553.9,1717.4
XS Rating Curve= 0 ,0
Exp/Cntr(USF)=0,0
Exp/Cntr=0.3,0.1

Type RM Length L Ch R = 1 ,28616   ,447.7,456.9,471.8
XS GIS Cut Line= 4
2493135.28736222641173.4126851812494533.13420419640927.844996728
2494910.93064797640751.5399896332495427.25245446 640487.08247899
#Sta/Elev= 30
       0 1413.36  188.941388.138   198.6 1385.66  288.271378.633   352.8 1375.62
   585.5  1373.1   668.4 1359.19  784.891357.733  1071.6 1356.95  1112.2 1352.84
 1182.181352.893  1281.51354.397 1482.541354.599  1553.5 1355.75  1566.7 1352.16
  1588.8 1353.12  1595.7  1350.8  1606.4 1348.32    1655 1348.06    1730 1351.35
  1774.2 1349.69  1792.21351.508  1809.6 1353.35  1916.6  1401.4  2074.3 1462.05
  2153.5 1497.55  2209.21527.232 2216.051530.562  2294.4 1571.86  2416.3 1645.71
#Mann= 12 ,-1 , 0
       0     .05       0  188.94     .06       0  288.27     .05       0
  784.89     .05       0 1182.18     .05       0  1281.5     .05       0
 1482.54    .025       0  1595.7    .045       0    1730      .1       0
  1792.2      .1       0  2209.2      .1       0 2216.05      .1       0
Bank Sta=1595.7,1730
XS Rating Curve= 0 ,0
Exp/Cntr(USF)=0,0
Exp/Cntr=0.3,0.1

Type RM Length L Ch R = 1 ,28159   ,503.2,511.4,520.1
XS GIS Cut Line= 4
2493292.70254713641658.2514546922494602.39688555641356.014299672
2495200.57458819641116.7432186152495477.62531363641003.404285482
#Sta/Elev= 30
       0 1505.43    59.6 1483.12   186.8 1423.66     232 1408.37   330.5 1397.02
   375.7 1400.48   424.9 1398.78   509.51388.391   552.2 1379.35  609.03 1372.96
   852.1 1358.09  1192.6 1352.34  1319.8 1355.01 1508.421348.192  1680.7 1354.22
  1727.9 1348.75  1849.9 1344.63  1865.3 1350.41  1891.6 1344.49 1915.52 1350.39
  1960.7 1383.63  2019.1 1407.22  2074.3 1534.54  2088.3 1545.17  2129.5 1556.67
 2147.291566.777  2215.4 1614.74  2228.4 1616.85  2241.4 1627.11  2287.7 1651.64
#Mann= 7 ,-1 , 0
       0      .1       0   509.5     .06       0  609.03     .05       0
 1508.42      .1       0  1727.9    .045       0 1915.52      .1       0
 2147.29      .1       0
Bank Sta=1727.9,1915.52
XS Rating Curve= 0 ,0
Exp/Cntr(USF)=0,0
Exp/Cntr=0.3,0.1

Type RM Length L Ch R = 1 ,27648   ,496,498,498.7
XS GIS Cut Line= 4
2493456.41433943642143.0902242032494829.07475181641758.997173032
2495395.76941748641607.8785955222495773.56586125641481.946447597
#Sta/Elev= 30
       0 1453.93    77.2 1451.66   201.8 1458.77   287.7 1456.45   376.2 1465.53
   409.5 1449.78     5271367.977   571.5 1354.58  626.941352.583   804.1 1349.31
 1026.711353.308  1182.1 1353.71  1280.8 1348.89  1493.4 1351.98 1526.291346.391
 1626.111350.237 1701.141348.148  1771.9 1348.13  1795.6  1343.5  1853.5 1342.86
  1878.4    1343 1898.221349.117    1986 1410.75  1990.1 1417.52  2005.3 1455.85
  2010.8 1463.02 2126.08 1532.85    2230 1596.21  2242.7 1600.72  2410.1 1715.72
#Mann= 10 ,-1 , 0
       0      .1       0     527     .06       0  626.94     .05       0
 1026.71     .05       0 1526.29      .1       0 1626.11    .025       0
 1701.14      .1       0  1771.9    .045       0 1898.22      .1       0
 2126.08      .1       0
Bank Sta=1771.9,1898.22
XS Rating Curve= 0 ,0
Exp/Cntr(USF)=0,0
Exp/Cntr=0.3,0.1

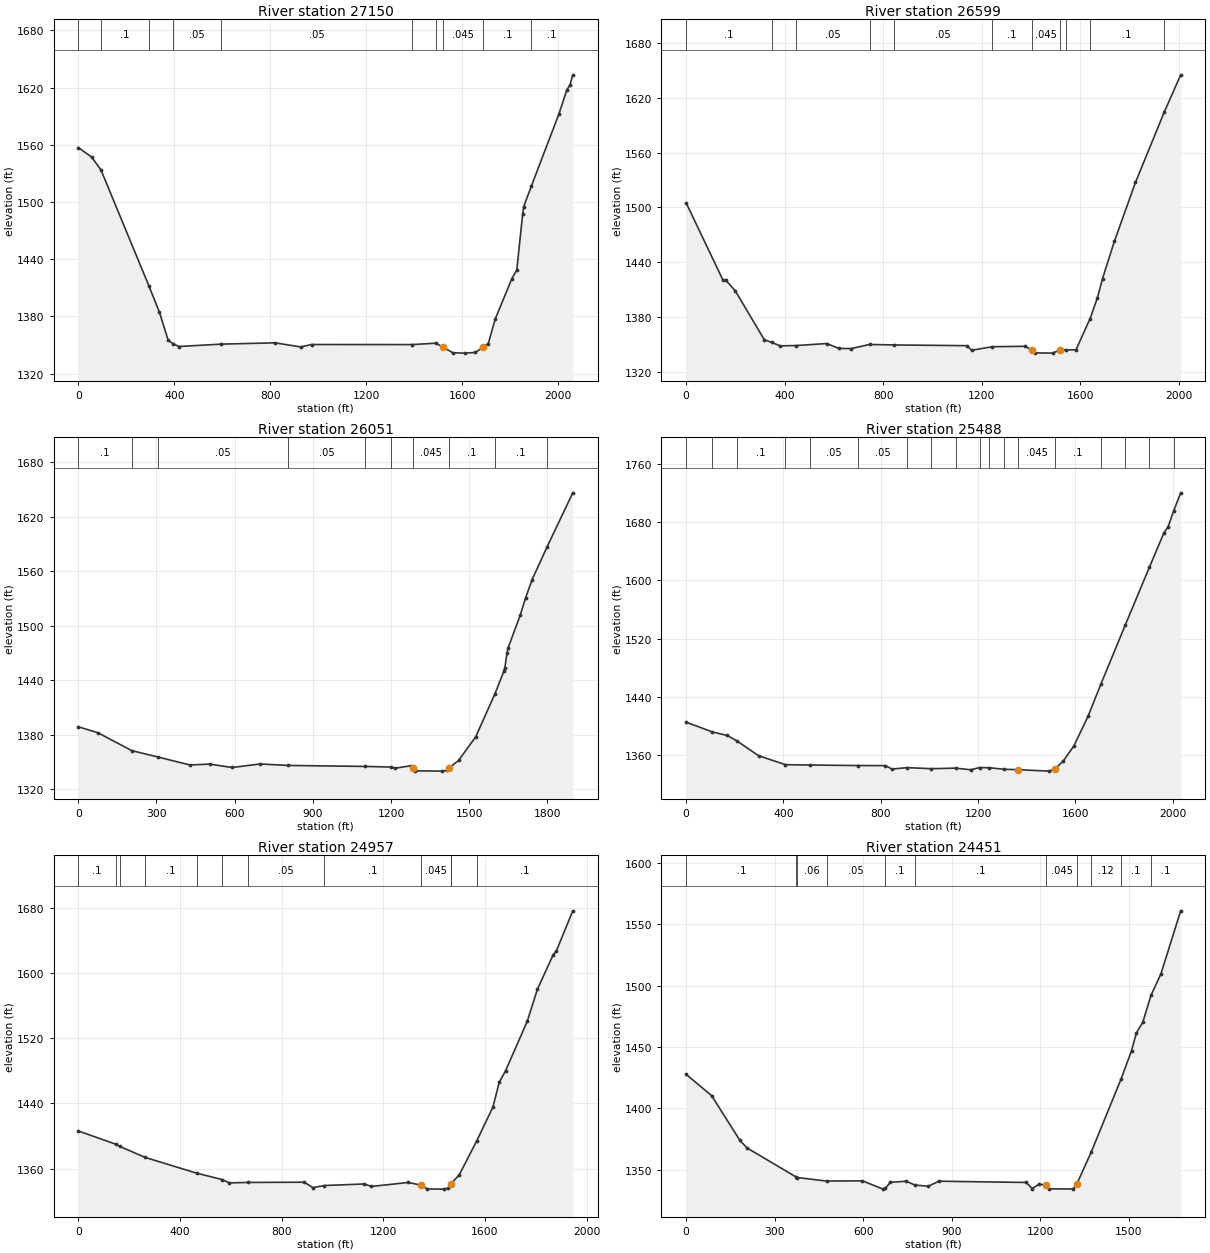
Type RM Length L Ch R = 1 ,27150   ,547.2,551,556.2
XS GIS Cut Line= 4
2493752.35488706642527.1832753742495049.45601068642199.759690769
2495465.03209883642105.3105798262495754.67603906642042.344505863
#Sta/Elev= 30
       0 1557.09    56.1    1547   94.76 1533.46  294.131412.033   338.2 1384.24
   374.4  1355.1  393.821351.437   419.1 1348.33   593.21350.798   819.3 1352.19
   926.6 1347.89     972 1350.41 1390.611350.344 1490.12 1351.82 1518.641347.821
  1560.6 1341.74  1609.8 1341.38    1655 1342.08  1687.41347.821  1708.3 1351.43
  1737.3 1377.17  1806.6 1419.54  1827.1 1428.54  1851.5 1487.26  1855.8 1495.14
 1888.091516.802  2003.1 1592.64  2035.9 1617.72  2048.2 1622.45  2060.4 1633.36
#Mann= 10 ,-1 , 0
       0      .1       0   94.76      .1       0  294.13     .06       0
  393.82     .05       0   593.2     .05       0 1390.61    .025       0
 1490.12      .1       0 1518.64    .045       0  1687.4      .1       0
 1888.09      .1       0
Bank Sta=1518.64,1687.4
XS Rating Curve= 0 ,0
Exp/Cntr(USF)=0,0
Exp/Cntr=0.3,0.1

Type RM Length L Ch R = 1 ,26599   ,549.2,548.1,548.1
XS GIS Cut Line= 4
2493972.73614592642980.5390079042495250.94744736642709.784889866
2495540.59138759642659.4120306962495930.98104616642546.073097563
#Sta/Elev= 30
       0  1504.9   149.2 1420.43   161.7 1419.94   198.8 1408.81   316.9 1355.12
  347.071351.994   382.3 1348.26   446.51348.613   570.4 1350.81   619.5 1345.48
   668.5 1345.26  744.791349.793  844.221349.273  1138.7 1348.48  1159.2 1343.44
 1241.94 1347.33  1374.6 1347.81  1402.3 1344.06  1416.1 1340.56  1486.9 1340.31
  1517.5 1343.78 1539.971343.947  1582.1 1343.91 1639.581378.248  1669.4 1401.16
  1689.9 1422.05  1737.9 1462.82  1823.6 1527.39 1939.751604.044  2007.1 1645.27
#Mann= 11 ,-1 , 0
       0      .1       0  347.07     .06       0   446.5     .05       0
  744.79     .05       0  844.22     .05       0 1241.94      .1       0
  1402.3    .045       0  1517.5      .1       0 1539.97      .1       0
 1639.58      .1       0 1939.75     .12       0
Bank Sta=1402.3,1517.5
XS Rating Curve= 0 ,0
Exp/Cntr(USF)=0,0
Exp/Cntr=0.3,0.1

Type RM Length L Ch R = 1 ,26051   ,565.3,562.5,562.8
XS GIS Cut Line= 4
2494205.71061958643528.3438513782495219.46441038643276.479555528
2495647.63371333643194.6236593772496050.61658669 643087.58133364
#Sta/Elev= 30
       0 1388.52    75.3 1381.97  205.071362.258  304.731355.298   427.9 1346.45
   503.9 1347.38   590.5 1343.66   697.6 1347.55  803.011345.952  1101.81344.837
 1201.151344.163  1214.9 1342.81    1276  1345.6  1284.1  1343.6  1293.4    1340
  1394.1 1339.66  1414.3 1340.51  1424.3 1343.54  1459.2 1351.39  1525.1 1377.49
  1599.11425.044  1632.7 1449.51  1636.8 1453.59  1645.1 1469.68  1649.3 1475.38
  1695.4 1511.12  1716.3 1530.45  1741.2 1550.42 1798.711586.644  1897.5 1646.22
#Mann= 10 ,-1 , 0
       0      .1       0  205.07     .06       0  304.73     .05       0
  803.01     .05       0  1101.8     .12       0 1201.15      .1       0
  1284.1    .045       0  1424.3      .1       0  1599.1      .1       0
 1798.71      .1       0
Bank Sta=1284.1,1424.3
XS Rating Curve= 0 ,0
Exp/Cntr(USF)=0,0
Exp/Cntr=0.3,0.1

Type RM Length L Ch R = 1 ,25488   ,530.9,531.2,522.6
XS GIS Cut Line= 4
2494300.15973053644126.5215540212495402.06602487643817.987791605
2495868.01497219643717.2420732652496264.70123816643603.903140133
#Sta/Elev= 30
       0 1405.58  108.231392.173   168.8 1387.35  208.171379.998   297.6 1359.66
  408.061347.315  508.011346.871   707.91346.109   819.6 1346.02   845.9 1341.31
  907.791343.246 1007.731341.808 1107.681342.563  1169.5 1340.32 1207.311343.364
  1247.3 1343.08 1306.761341.037    1366 1340.41  1492.8 1338.46  1517.4 1341.51
  1550.1 1352.13  1594.3 1373.01    1653 1413.99 1705.03  1457.5 1805.031538.396
 1905.041618.225    1965 1665.64  1981.6 1673.44 2005.041695.852  2033.6 1720.23
#Mann= 18 ,-1 , 0
       0      .1       0  108.23      .1       0  208.17      .1       0
  408.06     .06       0  508.01     .05       0   707.9     .05       0
  907.79     .05       0 1007.73     .05       0 1107.68     .05       0
 1207.31      .1       0  1247.3    .025       0 1306.76      .1       0
    1366    .045       0  1517.4      .1       0 1705.03     .12       0
 1805.03      .1       0 1905.04      .1       0 2005.04      .1       0
Bank Sta=1366,1517.4
XS Rating Curve= 0 ,0
Exp/Cntr(USF)=0,0
Exp/Cntr=0.3,0.1

Type RM Length L Ch R = 1 ,24957   ,504.8,506.1,508
XS GIS Cut Line= 4
2494533.13420419644661.7331827022495597.26085416644315.419775909
2496088.39623106 644195.784235382496396.92999348644107.631731833
#Sta/Elev= 30
       0 1406.23  148.541389.806  163.79 1387.12   264.31373.606   465.31354.407
   565.81346.537   594.8 1342.44  666.31 1342.99     889 1343.27   922.9 1336.61
  967.81 1339.19    1124 1341.12  1153.5 1338.09  1297.6 1342.94    1347 1339.82
  1372.3 1335.02  1438.5 1334.78  1454.1 1335.68 1465.551340.719 1467.241341.519
  1499.3 1352.65 1566.861393.577  1631.2 1435.56  1656.1 1465.94  1681.1 1480.19
  1766.5 1541.02  1805.9 1579.85  1868.3 1622.51  1880.8 1627.19  1945.4  1676.4
#Mann= 12 ,-1 , 0
       0      .1       0  148.54      .1       0  163.79      .1       0
   264.3      .1       0   465.3      .1       0   565.8     .06       0
  666.31     .05       0  967.81      .1       0    1347    .045       0
 1465.55      .1       0 1467.24      .1       0 1566.86      .1       0
Bank Sta=1347,1465.55
XS Rating Curve= 0 ,0
Exp/Cntr(USF)=0,0
Exp/Cntr=0.3,0.1

Type RM Length L Ch R = 1 ,24451   ,506.5,512.2,518.5
XS GIS Cut Line= 4
2494778.70189264645026.9364116852495729.48960948644793.961938024
2496151.36230503644705.8094344762496396.92999348644605.063716136
#Sta/Elev= 30
       0  1427.7    86.1 1410.44     182 1373.99     206 1367.83   373.31344.037
  376.351343.717  475.981340.838   597.2    1341   667.2 1334.26  675.24 1335.13
   691.9  1339.8   745.5  1340.7  774.871337.586   819.6 1336.62   856.7 1340.72
  1151.8 1339.69  1172.3 1334.72  1195.5 1338.27  1219.2 1337.55  1229.7 1334.49
  1311.2 1334.38    1324 1338.79  1371.81364.174 1472.791423.607  1508.7 1446.96
  1525.1 1461.39  1546.6    1470 1574.761492.084  1608.1 1509.43  1675.3 1560.92
#Mann= 11 ,-1 , 0
       0      .1       0   373.3      .1       0  376.35     .06       0
  475.98     .05       0  675.24      .1       0  774.87      .1       0
  1219.2    .045       0    1324      .1       0  1371.8     .12       0
 1472.79      .1       0 1574.76      .1       0
Bank Sta=1219.2,1324
XS Rating Curve= 0 ,0
Exp/Cntr(USF)=0,0
Exp/Cntr=0.3,0.1

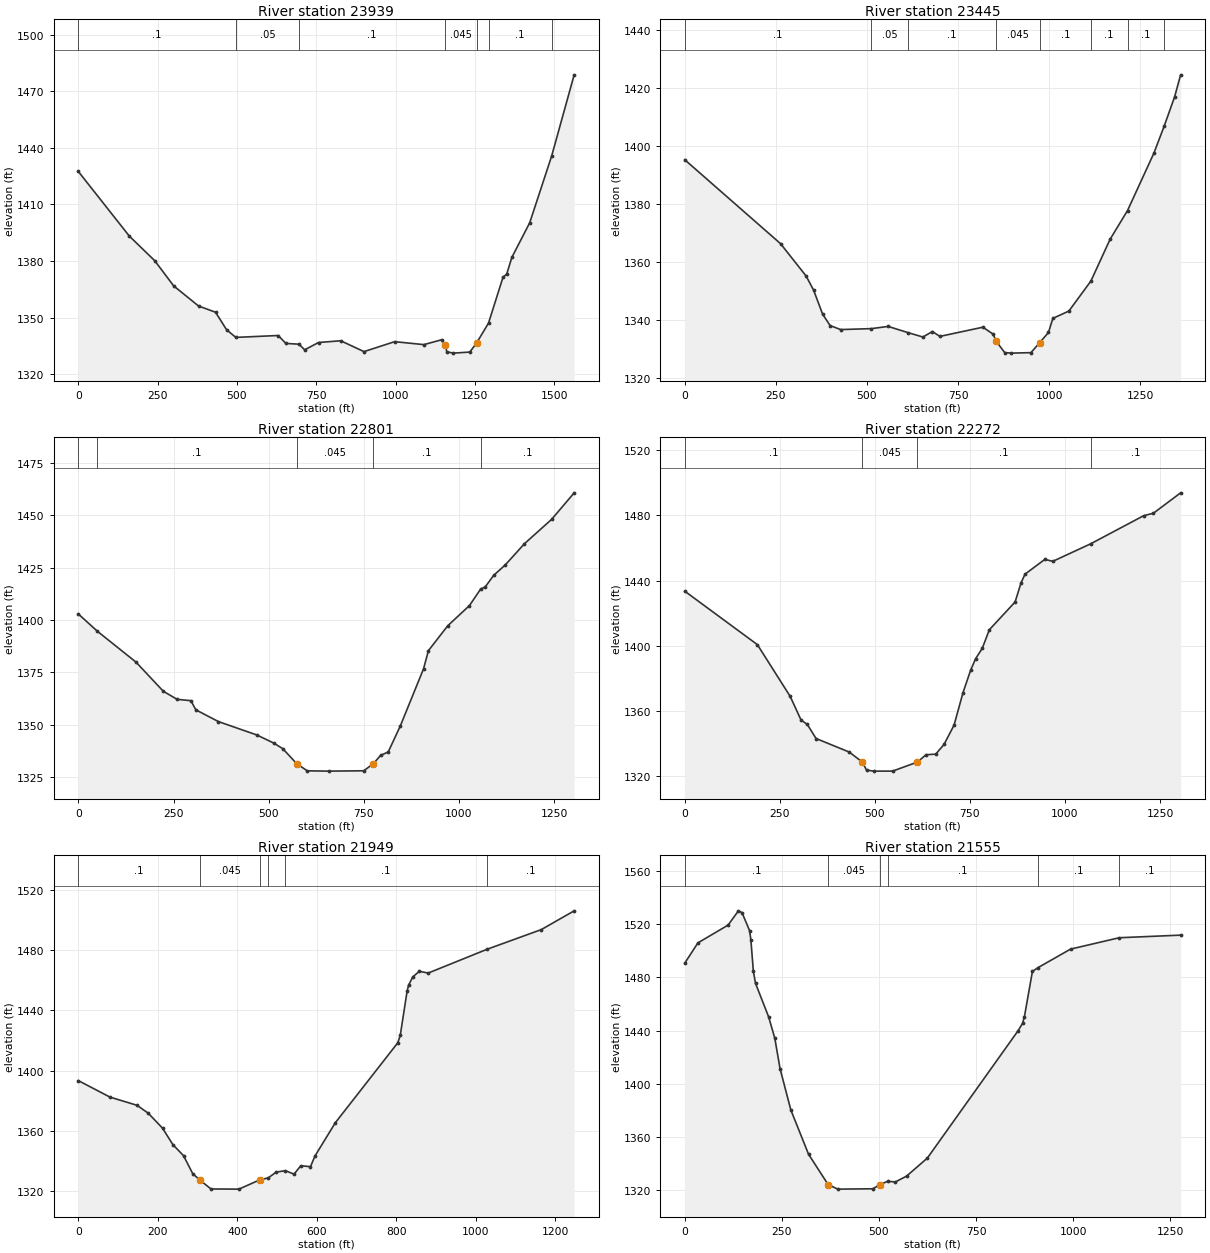
Type RM Length L Ch R = 1 ,23939   ,489.1,494,500.2
XS GIS Cut Line= 4
2494929.82047015645467.6989294222495786.15907604645266.207492742
2496264.70123816645222.1312409682496466.19267484 645203.24141878
#Sta/Elev= 30
       0 1427.49   160.7 1393.25     241 1380.17   300.4 1366.87     379 1356.19
   432.4 1352.91   467.2 1343.64  496.381339.568   629.7 1340.57   654.3 1336.37
   695.51335.965   713.3 1332.98     757 1336.86   826.9 1337.78   900.4 1332.03
   996.8  1337.3  1089.2 1335.74  1145.4 1338.34  1155.4 1335.79  1161.5 1331.93
  1181.6 1331.23  1233.8 1331.79 1255.411336.667 1292.831347.162  1338.2 1371.31
  1350.3  1373.2  1366.4 1381.99  1422.6  1400.3 1491.911435.744  1562.7  1478.7
#Mann= 7 ,-1 , 0
       0      .1       0  496.38     .05       0   695.5      .1       0
  1155.4    .045       0 1255.41      .1       0 1292.83      .1       0
 1491.91      .1       0
Bank Sta=1155.4,1255.41
XS Rating Curve= 0 ,0
Exp/Cntr(USF)=0,0
Exp/Cntr=0.3,0.1

Type RM Length L Ch R = 1 ,23445   ,643.6,644.3,648.5
XS GIS Cut Line= 4
 2495187.9813734645914.7580545562495930.98104616645725.859832668
2496226.92159378645732.1564400642496510.26892661645637.707329121
#Sta/Elev= 30
       0 1395.17   262.9 1366.21     333 1355.06   353.7 1350.15   378.4 1341.87
   399.1 1337.93     428 1336.56  512.481336.888   558.3 1337.65  612.191335.532
   653.7 1333.99   679.7 1335.88   700.4 1334.21   818.4 1337.38   846.4 1334.99
   855.3 1332.45   878.4 1328.61   896.7 1328.43   950.4  1328.6   974.4 1332.06
   998.5 1335.56  1010.5 1340.42  1054.5 1342.95 1114.931353.298  1167.8 1367.77
 1215.541377.645    1288 1397.48 1316.161406.786    1345 1416.97  1361.3 1424.49
#Mann= 8 ,-1 , 0
       0      .1       0  512.48     .05       0  612.19      .1       0
   855.3    .045       0   974.4      .1       0 1114.93      .1       0
 1215.54      .1       0 1316.16      .1       0
Bank Sta=855.3,974.4
XS Rating Curve= 0 ,0
Exp/Cntr(USF)=0,0
Exp/Cntr=0.3,0.1

Type RM Length L Ch R = 1 ,22801   ,575.5,529.1,484.1
XS GIS Cut Line= 4
2495332.80334351646412.1900388592495842.82854261646355.520572293
2496220.62498638646387.0036092742496611.01464495646261.071461349
#Sta/Elev= 30
       0 1402.87   49.941394.654   151.4 1379.95   223.3 1366.05   259.5 1362.21
   295.8 1361.57   308.6 1357.22   368.2  1351.6   468.8 1345.25   513.8 1341.34
   537.2 1338.69  573.521331.599   601.4 1328.16   657.6 1328.02   749.9 1328.19
  775.131331.599   794.1 1335.51   814.1 1337.16     846 1349.61   906.8 1376.73
   919.7 1385.41   970.3 1397.23  1027.5 1406.89 1056.761414.721  1068.8 1415.73
  1091.1 1421.27  1121.5 1426.22  1171.9 1436.33  1243.6 1447.99  1302.5 1460.57
#Mann= 5 ,-1 , 0
       0      .1       0   49.94      .1       0  573.52    .045       0
  775.13      .1       0 1056.76      .1       0
Bank Sta=573.52,775.13
XS Rating Curve= 0 ,0
Exp/Cntr(USF)=0,0
Exp/Cntr=0.3,0.1

Type RM Length L Ch R = 1 ,22272   ,372.7,322.6,266.7
XS GIS Cut Line= 4
2495609.85406895 647098.520245052495905.79461657646959.994882333
2496333.96391952646771.0966604452496724.35357808 646443.67307584
#Sta/Elev= 30
       0 1433.52   190.9 1400.75   277.2 1369.01   305.7 1354.55   322.3  1351.8
   345.3 1343.16   432.7 1334.85  467.041328.705   478.1 1323.75   498.2 1323.16
   546.7 1323.17  611.751328.706   634.7 1333.21   660.1 1333.58   681.9 1339.53
   708.2  1351.3   731.8 1371.26   751.9 1385.05     765 1392.12   782.5 1398.47
   801.1 1409.87   868.9 1426.92   884.5 1438.65     895 1443.99   947.2 1453.05
     968 1451.84 1067.421462.558  1207.1 1479.84  1232.7 1481.34  1304.3 1493.86
#Mann= 4 ,-1 , 0
       0      .1       0  467.04    .045       0  611.75      .1       0
 1067.42      .1       0
Bank Sta=467.04,611.75
XS Rating Curve= 0 ,0
Exp/Cntr(USF)=0,0
Exp/Cntr=0.3,0.1

Type RM Length L Ch R = 1 ,21949   ,406.9,393.7,378.3
XS GIS Cut Line= 4
2496063.20980148647482.6132962212496157.65891242647337.791326108
2496352.85374171 646947.401667542496768.42982986646462.562898029
#Sta/Elev= 30
       0 1393.32    79.7 1382.37   147.7 1376.95   176.1 1371.68   211.9 1361.77
   237.9  1350.9   264.8 1343.53   287.9 1331.62   305.21327.529   333.9 1321.46
   404.2 1321.36  456.711327.529   477.91328.804   498.1 1332.66  521.131333.595
   542.9 1331.29   559.9 1336.87   584.3 1336.25   595.7 1343.39   646.9 1365.42
     804  1418.4   810.2 1423.29   827.4 1452.52   831.3 1456.72   841.8 1462.09
   858.1  1465.8   880.6 1464.64 1028.791480.414  1165.4 1493.48  1247.9  1505.9
#Mann= 6 ,-1 , 0
       0      .1       0   305.2    .045       0  456.71      .1       0
   477.9      .1       0  521.13      .1       0 1028.79      .1       0
Bank Sta=305.2,456.71
XS Rating Curve= 0 ,0
Exp/Cntr(USF)=0,0
Exp/Cntr=0.3,0.1

Type RM Length L Ch R = 1 ,21555   ,367.9,368.3,372.7
XS GIS Cut Line= 4
2496472.48928223647740.774199467 2496529.1587488 647602.24883675
2496642.49768193647174.0795338052496793.61625944646506.639149803
#Sta/Elev= 30
       0  1490.8    33.8 1506.02   111.6 1519.42   138.1 1530.13   147.3  1528.8
   166.8 1515.24   170.1 1508.54   176.6 1484.61   182.1 1475.59   215.9 1450.34
   231.8 1434.24   245.3 1411.37   273.1 1380.26   318.7 1346.96  369.09 1324.15
   394.1 1320.71   484.2 1320.97  502.88 1324.15  522.491326.596   542.1  1326.1
   571.1 1330.49   624.6 1344.05   858.3  1439.9   869.7 1445.38   874.7 1450.61
   895.2 1484.49  908.791487.243   993.4 1501.31 1118.571509.876  1276.9 1511.84
#Mann= 6 ,-1 , 0
       0      .1       0  369.09    .045       0  502.88    .025       0
  522.49      .1       0  908.79      .1       0 1118.57      .1       0
Bank Sta=369.09,502.88
XS Rating Curve= 0 ,0
Exp/Cntr(USF)=0,0
Exp/Cntr=0.3,0.1