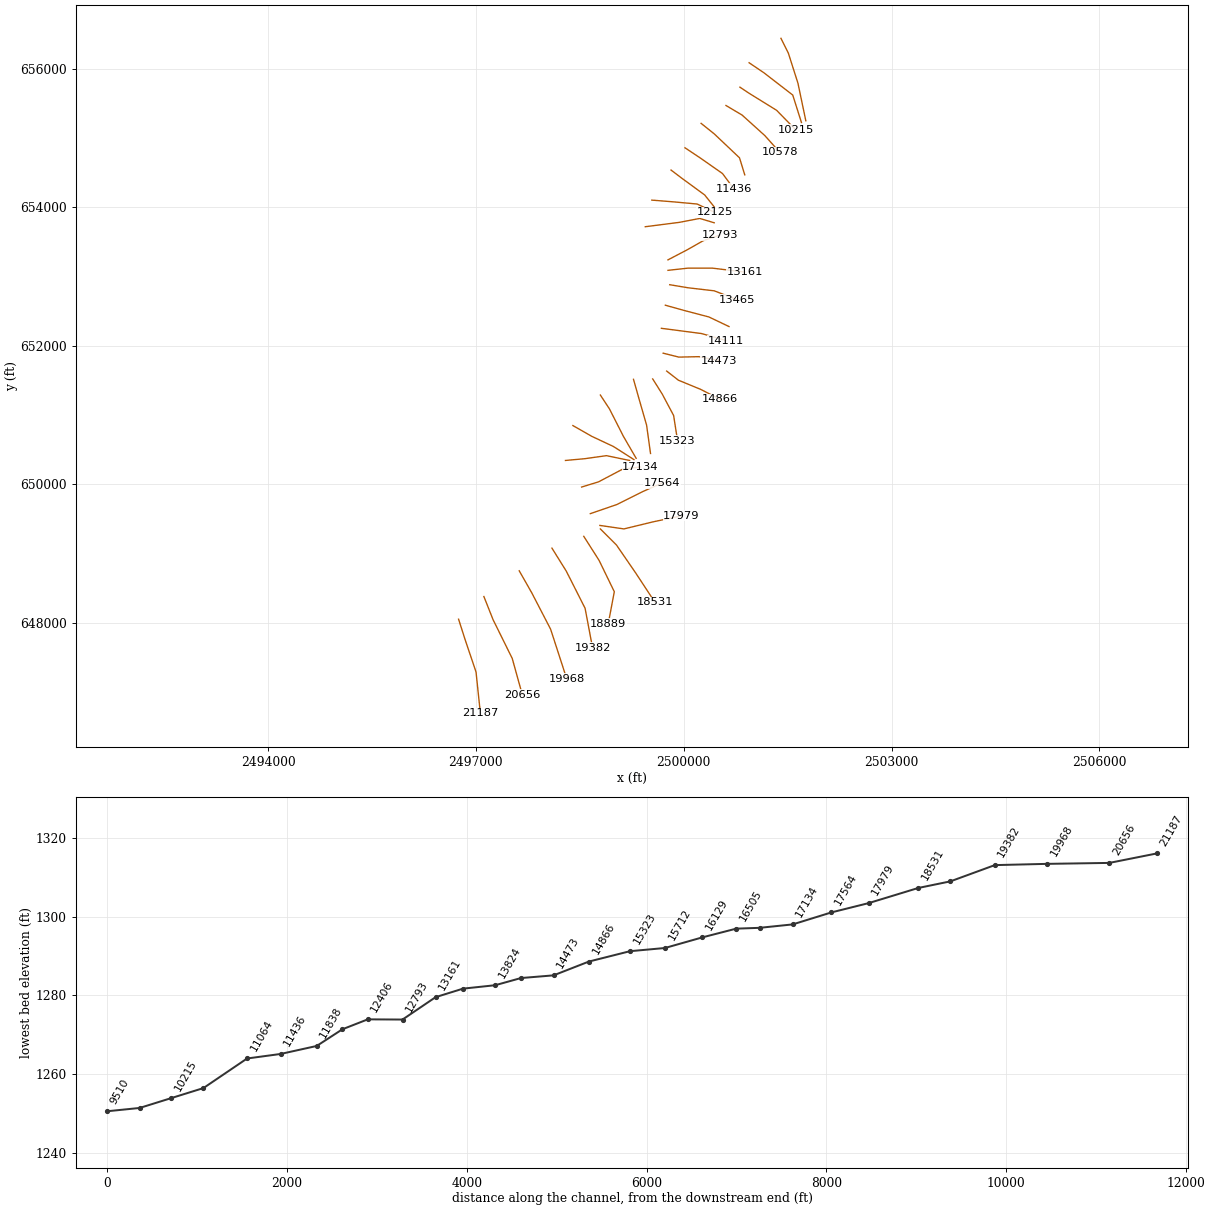
HEC-RAS study SFSBPOTOMC.prj: SFSBPOTOMC

--- SFSBPOTOMC.g01 (geometry) --- (continued)

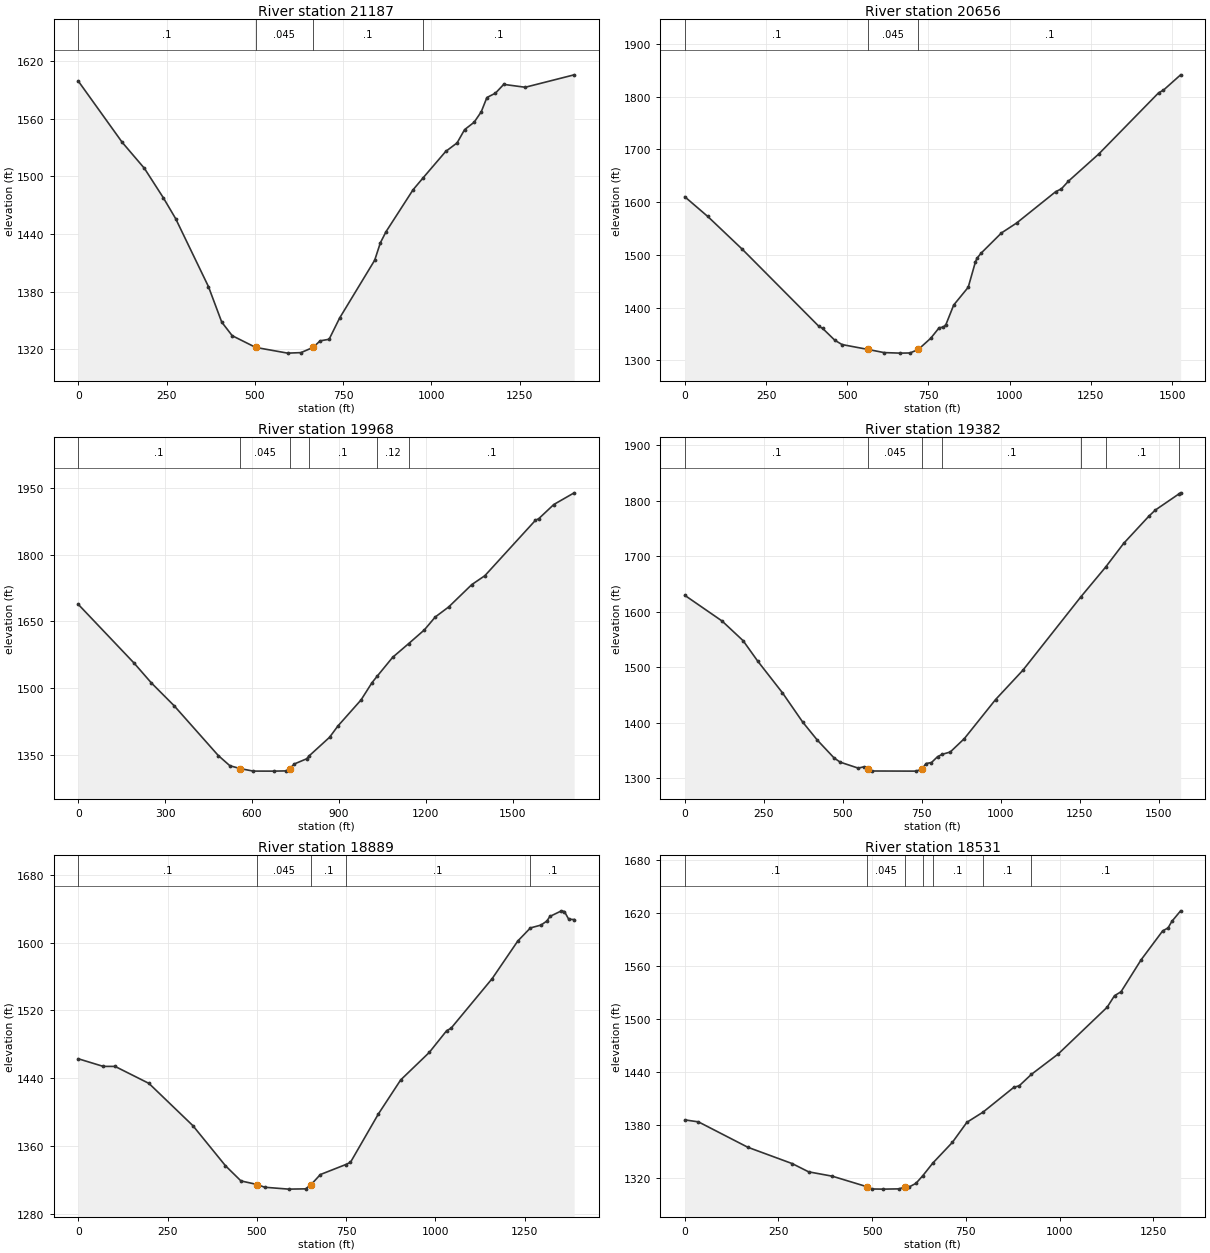
Type RM Length L Ch R = 1 ,21187   ,520,530.6,543.1
XS GIS Cut Line= 4
2496749.54000767648049.3079618832496843.98911861 647753.36741426
2497001.40430352647287.4184669382497064.37037748646689.240764294
#Sta/Elev= 30
       0 1599.22   124.3 1535.48   187.3 1508.34   240.8 1477.72   275.5 1456.11
   368.4 1385.35   406.1  1348.3   435.7  1334.2  502.111321.988   592.5 1316.03
   630.4 1316.55  664.65 1321.99   684.8 1328.84   710.1 1330.44   739.7 1352.46
   839.2  1412.8   855.3 1430.95   871.4 1442.54   947.8  1486.1  976.761498.749
  1040.3 1526.04  1072.5 1534.92  1093.7 1548.71  1120.8 1556.44  1140.9 1567.31
  1156.9 1582.16  1181.1  1586.7  1204.5 1595.85  1265.5 1592.86    1404  1605.8
#Mann= 4 ,-1 , 0
       0      .1       0  502.11    .045       0  664.65      .1       0
  976.76      .1       0
Bank Sta=502.11,664.65
XS Rating Curve= 0 ,0
Exp/Cntr(USF)=0,0
Exp/Cntr=0.3,0.1

Type RM Length L Ch R = 1 ,20656   ,686.1,688.2,687.4
XS GIS Cut Line= 4
2497114.74323665648376.7315464882497246.97199197648043.011354487
2497524.02271741647482.6132962212497668.84468752646959.994882333
#Sta/Elev= 30
       0 1610.27    70.8 1572.85   177.1 1510.63   412.6 1364.59   424.6 1360.39
   461.7 1338.15     484 1329.88  564.211320.589   613.4 1314.65   662.5 1313.62
   693.3 1313.92  718.871320.586   756.9 1341.73     783 1361.73   796.4 1363.07
   803.8 1367.71   827.8 1404.86   872.5 1438.58   894.6 1486.54   899.3 1493.49
   912.4 1503.42   974.9 1541.68  1021.2 1560.34  1142.1 1620.08  1159.1 1625.13
  1181.1 1639.91  1274.4 1691.44  1458.6 1807.49  1473.6 1812.62  1526.4 1841.63
#Mann= 3 ,-1 , 0
       0      .1       0  564.21    .045       0  718.87      .1       0
Bank Sta=564.21,718.87
XS Rating Curve= 0 ,0
Exp/Cntr(USF)=0,0
Exp/Cntr=0.3,0.1

Type RM Length L Ch R = 1 ,19968   ,587.8,585.9,586.3
XS GIS Cut Line= 4
2497624.76843575648748.2313828672497807.37005024648427.104405658
2498078.12416828 647904.485991772498311.09864194647186.672748598
#Sta/Elev= 30
       0 1688.24   193.1 1555.94   251.8 1512.07     331 1460.36   483.5 1348.41
   523.4 1325.55  558.661319.144   603.9 1313.46   674.8 1313.38   716.3 1313.87
  730.991319.148     746 1329.44   788.6 1341.12  797.551347.823   867.7 1389.44
   896.7 1414.91   976.5 1473.41  1014.3 1512.16 1031.511526.205  1085.8 1569.34
  1140.81599.969  1195.2  1630.9  1232.8  1659.9  1279.3 1682.55  1359.2 1732.87
  1404.3 1752.83  1578.9 1877.35  1590.5 1881.13  1642.4 1912.89  1712.7 1939.15
#Mann= 6 ,-1 , 0
       0      .1       0  558.66    .045       0  730.99    .025       0
  797.55      .1       0 1031.51     .12       0  1140.8      .1       0
Bank Sta=558.66,730.99
XS Rating Curve= 0 ,0
Exp/Cntr(USF)=0,0
Exp/Cntr=0.3,0.1

Type RM Length L Ch R = 1 ,19382   ,491.8,493.7,490.8
XS GIS Cut Line= 4
2498097.01399047649075.6549674722498304.80203454648741.934775471
2498575.55615258 648206.723146792498682.59847832647640.028481127
#Sta/Elev= 30
       0  1629.8     118 1583.49   184.7 1548.02   230.3 1511.68   309.2 1454.13
   373.1 1401.56   418.9 1369.33   472.7 1336.75   492.1 1329.18   548.9 1318.49
   566.9 1320.88  579.441316.927   593.3  1313.3   732.7 1313.06  750.371316.926
   764.1  1326.8   780.8 1328.48     800 1338.99  814.911343.381   840.2 1347.45
   884.8 1371.58   983.8    1442  1070.1 1494.73 1253.41  1626.8 1332.281680.712
  1389.3 1723.37    1469 1772.31  1489.4 1783.35 1563.871812.338  1569.6 1814.44
#Mann= 7 ,-1 , 0
       0      .1       0  579.44    .045       0  750.37    .025       0
  814.91      .1       0 1253.41     .12       0 1332.28      .1       0
 1563.87     .12       0
Bank Sta=579.44,750.37
XS Rating Curve= 0 ,0
Exp/Cntr(USF)=0,0
Exp/Cntr=0.3,0.1

Type RM Length L Ch R = 1 ,18889   ,346.7,357.8,369.7
XS GIS Cut Line= 4
2498556.66633039 649245.663367172498777.04758926648899.349960377
2498997.42884813648445.9942278472498909.27634458647980.045280525
#Sta/Elev= 30
       0  1462.9    69.7 1453.93   102.9  1453.9   197.7 1433.85   320.9  1383.9
   412.1 1336.58   455.5 1318.63   500.81314.391   522.2 1311.15   588.9 1308.94
   636.6 1309.26  652.161314.392   677.9 1326.16  748.951337.955   762.3 1340.63
   840.5 1397.79   902.9 1437.94   982.9 1470.38  1031.7 1496.12  1043.9 1498.95
  1159.2 1557.64    1231 1602.08 1266.361617.498  1296.1 1620.88  1312.6 1625.72
  1320.8 1631.06  1353.3 1637.68  1361.5 1636.86  1373.7 1627.65  1388.8 1627.43
#Mann= 5 ,-1 , 0
       0      .1       0   500.8    .045       0  652.16      .1       0
  748.95      .1       0 1266.36      .1       0
Bank Sta=500.8,652.16
XS Rating Curve= 0 ,0
Exp/Cntr(USF)=0,0
Exp/Cntr=0.3,0.1

Type RM Length L Ch R = 1 ,18531   ,469.5,551.8,607.3
XS GIS Cut Line= 4
2498795.93741145649352.7056929072499028.91188511649119.731219246
2499305.96261055648716.7483458862499583.01333598648294.875650337
#Sta/Elev= 30
       0 1385.67    36.5 1383.41     168  1354.7   286.8 1336.14   330.5 1326.84
   393.6 1321.91   485.8 1310.04   500.4 1307.42   529.5 1307.26   572.8 1307.56
   586.9 1310.07   598.9 1309.77   616.9 1313.81  635.361322.585  662.04 1336.85
     714 1360.17   752.8 1382.92  796.141394.518     878 1422.51   892.5  1424.3
  925.161437.292   996.6 1460.32    1127 1513.17  1146.8 1526.31  1164.1 1530.71
  1217.9 1567.01  1275.3 1599.68  1289.7 1603.05  1299.9 1610.52  1323.2 1622.39
#Mann= 7 ,-1 , 0
       0      .1       0   485.8    .045       0   586.9      .1       0
  635.36      .1       0  662.04      .1       0  796.14      .1       0
  925.16      .1       0
Bank Sta=485.8,586.9
XS Rating Curve= 0 ,0
Exp/Cntr(USF)=0,0
Exp/Cntr=0.3,0.1

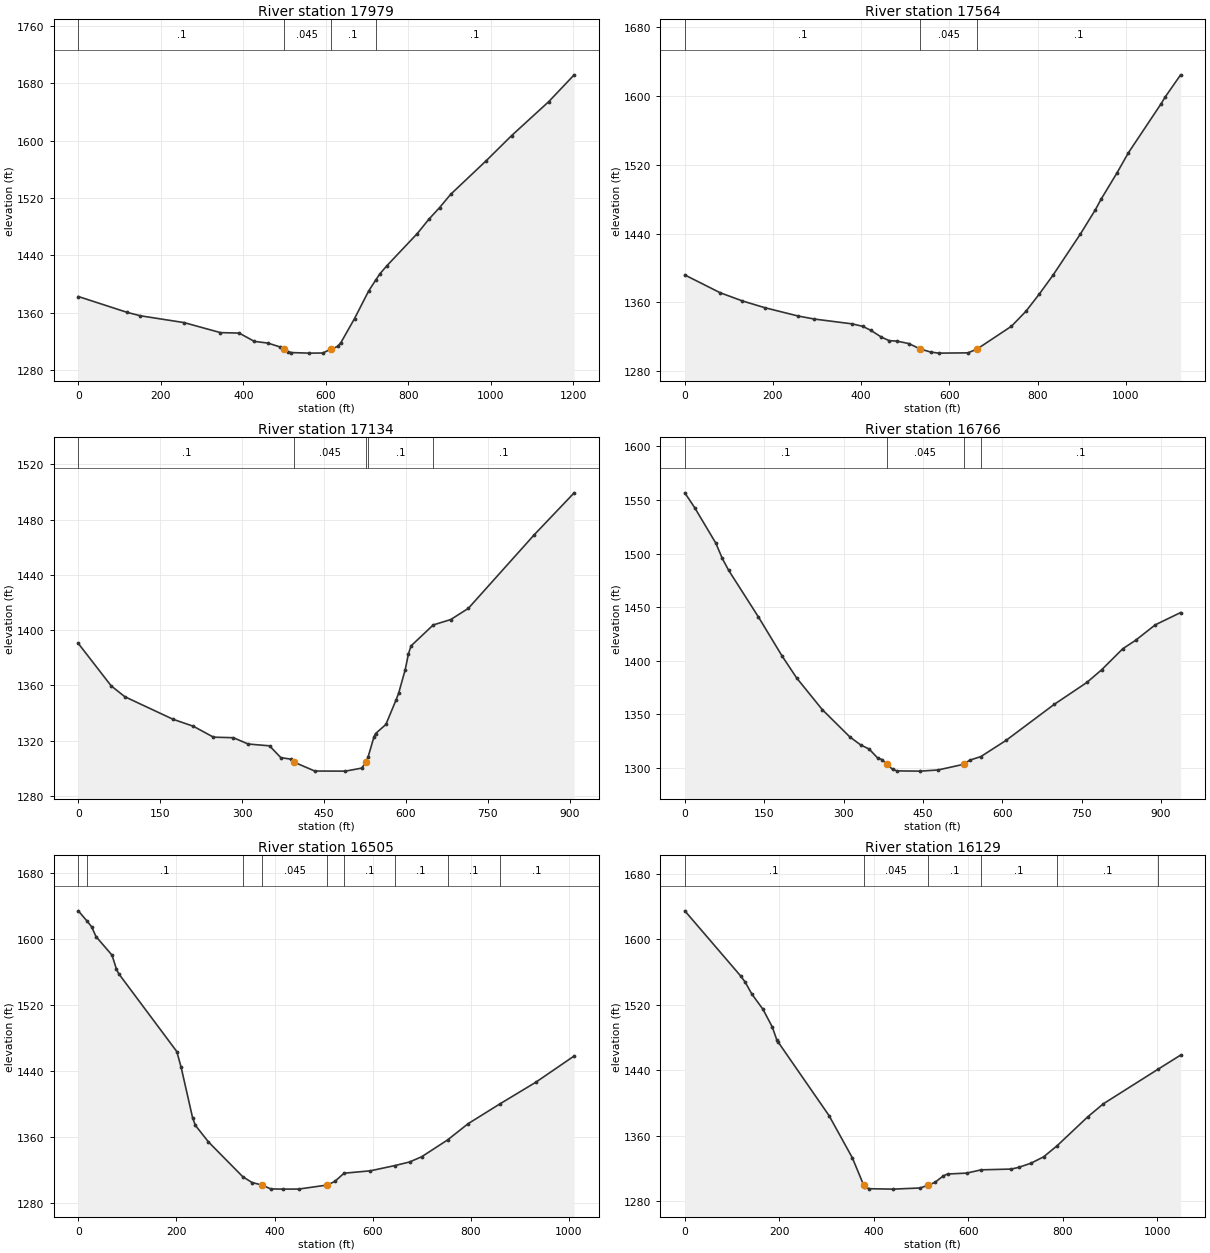
Type RM Length L Ch R = 1 ,17979   ,397,414.5,426.1
XS GIS Cut Line= 4
2498789.64080405649403.0785520772499135.95421085649352.705692907
  2499551.530299649453.4514112472499967.10638715649541.603914794
#Sta/Elev= 30
       0 1382.39   118.3  1360.3   150.7 1355.51   256.5    1346   344.7 1332.02
   389.9  1331.4   426.9 1319.81   459.8 1317.43   488.7 1312.11  499.441308.666
   509.2 1305.32   516.4  1304.2   559.5 1303.42   592.6 1303.59  611.681308.667
   628.6 1312.74   636.8 1318.15   669.8 1351.64   703.9 1389.95  720.651404.907
   731.7 1414.37   748.3 1425.39     822 1470.26   850.4 1490.44     876 1506.42
   902.9 1524.96   989.4 1571.99  1050.7 1606.87  1140.7 1654.22  1202.4 1691.66
#Mann= 4 ,-1 , 0
       0      .1       0  499.44    .045       0  611.68      .1       0
  720.65      .1       0
Bank Sta=499.44,611.68
XS Rating Curve= 0 ,0
Exp/Cntr(USF)=0,0
Exp/Cntr=0.3,0.1

Type RM Length L Ch R = 1 ,17564   ,428.9,430.6,432
XS GIS Cut Line= 4
2498651.11544134649573.0869517752499035.20849251649705.315707097
2499413.00493628649894.2139289842499683.75905432650013.849469513
#Sta/Elev= 30
       0 1391.94      80 1371.31   130.8 1361.71   181.5 1353.87   257.7 1344.12
   293.8 1340.68   380.3 1335.03   403.9 1332.14     422 1327.53   445.9 1319.69
   463.7 1315.55   481.7    1315   508.4 1312.14  533.591305.924   557.8  1302.3
   575.6 1301.06   642.3 1301.38  663.241305.923     741 1332.35   773.8 1349.75
   804.2 1369.85   834.9 1391.52   897.2 1439.48   931.1 1467.61   944.2 1480.01
   979.6 1510.01  1006.3 1534.09  1079.8 1590.56  1089.2 1598.54  1124.6 1624.58
#Mann= 3 ,-1 , 0
       0      .1       0  533.59    .045       0  663.24      .1       0
Bank Sta=533.59,663.24
XS Rating Curve= 0 ,0
Exp/Cntr(USF)=0,0
Exp/Cntr=0.3,0.1

Type RM Length L Ch R = 1 ,17134   ,375.2,367.9,320.7
XS GIS Cut Line= 4
2498525.18329341649957.1800029472498770.75098186650032.739291701
2499117.06438866650215.340906193 2499375.2252919650246.823943174
#Sta/Elev= 30
       0 1390.37    60.2 1359.69    85.3 1351.82   173.2 1335.59   210.9 1330.46
   247.6 1322.59   284.1 1322.19   311.2 1317.63   350.3 1316.33     371 1307.79
   388.8 1306.72  395.531304.482   433.2 1298.09   489.5 1298.02   519.1 1300.21
  527.051304.484  530.961308.307   541.8  1322.9   544.6 1325.19   563.5 1331.76
   582.5 1349.83     587 1354.51     599 1371.51   604.9 1382.87   609.6  1388.6
  650.271403.765   682.4 1407.68   714.6 1415.77   835.5 1469.06   908.5 1499.34
#Mann= 5 ,-1 , 0
       0      .1       0  395.53    .045       0  527.05      .1       0
  530.96      .1       0  650.27      .1       0
Bank Sta=395.53,527.05
XS Rating Curve= 0 ,0
Exp/Cntr(USF)=0,0
Exp/Cntr=0.3,0.1

Type RM Length L Ch R = 1 ,16766   ,294.6,260.7,209.6
XS GIS Cut Line= 4
2498292.20881975650341.2730541182498569.25954518650366.459483703
  2498884.089915650410.535735476  2499217.810107650341.273054118
#Sta/Elev= 30
       0 1556.62    18.6 1542.84    58.8 1509.56    70.8 1495.49    82.9 1484.35
   139.1 1440.92   184.2 1404.19   211.4    1384   259.6 1354.59     312 1328.99
   332.2 1321.63   348.4 1317.71   364.5 1309.37   372.6 1307.96  382.081303.511
   392.8 1298.75   400.9 1297.38   445.3 1297.15   478.3 1298.21  526.921303.514
   538.5 1307.37  559.491310.729     607 1325.79   697.9 1359.34   759.8 1379.85
   787.5 1391.56   827.6 1411.26   851.8 1419.12     889 1433.55   936.9 1444.99
#Mann= 4 ,-1 , 0
       0      .1       0  382.08    .045       0  526.92      .1       0
  559.49      .1       0
Bank Sta=382.08,526.92
XS Rating Curve= 0 ,0
Exp/Cntr(USF)=0,0
Exp/Cntr=0.3,0.1

Type RM Length L Ch R = 1 ,16505   ,412,376.2,317.6
XS GIS Cut Line= 4
2498399.25114549650845.0016458172498676.30187092650687.586460911
2498984.83563334650542.7644907982499280.77618096 650353.86626891
#Sta/Elev= 30
       0 1634.23   17.681621.858      27 1614.95    36.2  1602.9    68.7 1580.51
    77.6 1563.74    82.2 1558.14   200.7 1463.67   209.5  1444.7   232.9  1383.4
   238.6 1374.21   265.2 1354.18  335.121312.016   354.1 1304.91  374.481301.913
     392 1297.22   417.2 1296.94   449.5 1297.05  507.441301.913   522.5 1306.19
  541.691316.233   595.3 1319.15  644.981325.465   675.3 1329.88   699.7 1336.16
  752.461356.505   794.6 1376.31  860.141400.557   932.2  1426.4  1010.6 1458.31
#Mann= 9 ,-1 , 0
       0      .1       0   17.68      .1       0  335.12    .025       0
  374.48    .045       0  507.44    .025       0  541.69      .1       0
  644.98      .1       0  752.46      .1       0  860.14      .1       0
Bank Sta=374.48,507.44
XS Rating Curve= 0 ,0
Exp/Cntr(USF)=0,0
Exp/Cntr=0.3,0.1

Type RM Length L Ch R = 1 ,16129   ,427.5,417.2,400.8
XS GIS Cut Line= 4
2498795.93741145651285.7641635552498928.16616677651084.272726875
2499129.65760345650687.5864609112499312.25921794650372.756091099
#Sta/Elev= 30
       0 1635.04   118.3 1555.39   127.8 1547.92   142.2 1533.05   165.5 1514.69
   185.2 1493.06   194.8 1477.28   197.6 1474.62   305.4 1384.67   354.7  1333.1
  378.761299.639   381.6 1297.52   390.6 1295.23   440.3 1294.73   498.3 1296.11
  515.461299.635   529.7 1302.99   547.6 1311.01   556.3  1313.2     597 1314.33
  627.58 1318.33   691.4 1319.27   706.9 1321.34     733 1326.42   759.9 1334.26
  788.351347.782   853.2 1383.11   886.2 1399.05 1002.281441.426  1049.9 1458.63
#Mann= 6 ,-1 , 0
       0      .1       0  378.76    .045       0  515.46      .1       0
  627.58      .1       0  788.35      .1       0 1002.28      .1       0
Bank Sta=378.76,515.46
XS Rating Curve= 0 ,0
Exp/Cntr(USF)=0,0
Exp/Cntr=0.3,0.1

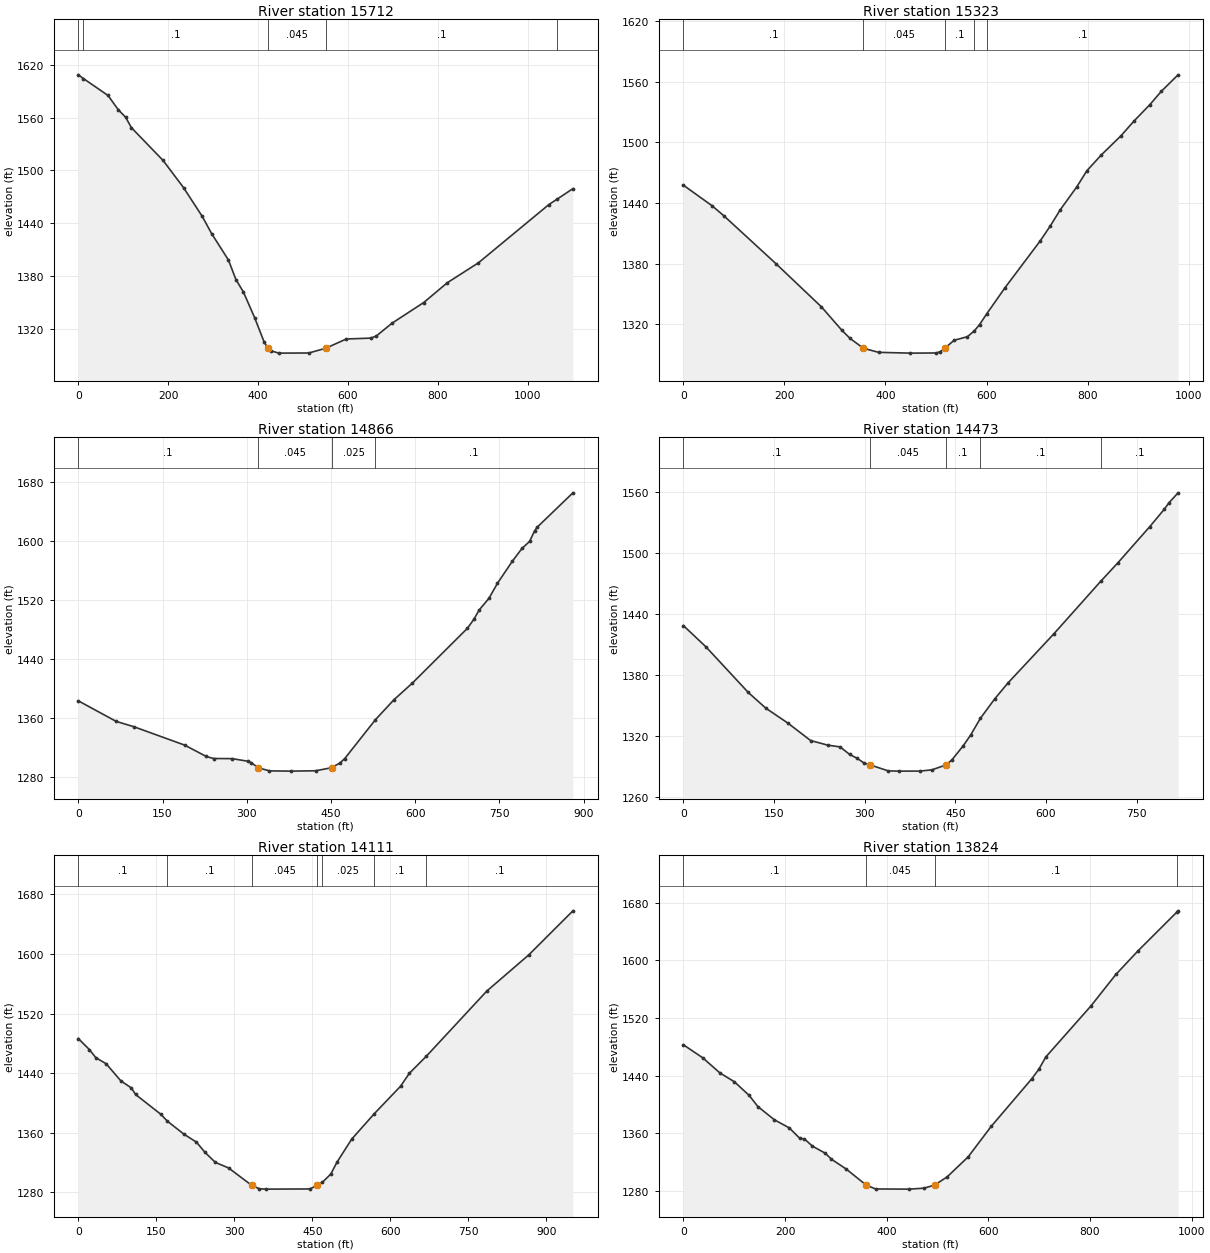
Type RM Length L Ch R = 1 ,15712   ,362.5,388.9,398.1
XS GIS Cut Line= 4
2499274.47957356 651512.442029822499356.33546972651222.798089592
2499463.37779545650851.2982532142499520.04726202650442.018772457
#Sta/Elev= 30
       0 1608.61   11.511604.347    66.3  1585.1      89 1568.92   105.5  1560.3
   118.1 1548.57   188.7 1511.23   234.4 1480.21     276  1447.5   296.7 1428.05
   334.2 1397.97   350.8 1375.78   367.5 1361.58   392.5 1332.37   413.3 1305.11
  421.831297.615   429.9 1294.47   446.6 1292.03   513.2 1292.19  550.881297.615
   596.4 1308.11   650.6 1309.09     663 1311.38     698 1325.99   768.8  1349.6
   821.3 1372.12   890.4 1394.72  1047.4 1461.06 1065.031466.965  1100.8 1479.15
#Mann= 5 ,-1 , 0
       0      .1       0   11.51      .1       0  421.83    .045       0
  550.88      .1       0 1065.03      .1       0
Bank Sta=421.83,550.88
XS Rating Curve= 0 ,0
Exp/Cntr(USF)=0,0
Exp/Cntr=0.3,0.1

Type RM Length L Ch R = 1 ,15323   ,403.2,457.1,504.8
XS GIS Cut Line= 4
  2499551.530299651518.7386372162499690.05566172651298.357378347
2499853.76745402650989.8236159312499910.43692059650624.620386949
#Sta/Elev= 30
       0  1457.6    56.5 1437.31    80.1 1427.28   184.1 1379.42   273.3 1337.01
     314 1313.67     330 1305.74  356.221296.045   386.5    1292   449.5 1291.22
   500.7 1291.38   508.8 1292.72  517.231296.048   535.9 1303.95   562.2 1307.52
  575.931313.317   586.1 1319.39  600.271330.055   636.8 1356.19   705.6 1401.96
   725.9 1416.97   746.1 1433.39   778.5 1455.82   798.7 1471.96   827.5 1487.74
   865.9 1506.44   891.9 1521.17   923.4 1537.46   945.9 1550.57   979.2 1566.98
#Mann= 5 ,-1 , 0
       0      .1       0  356.22    .045       0  517.23      .1       0
  575.93      .1       0  600.27      .1       0
Bank Sta=356.22,517.23
XS Rating Curve= 0 ,0
Exp/Cntr(USF)=0,0
Exp/Cntr=0.3,0.1

Type RM Length L Ch R = 1 ,14866   ,377.2,392.8,432.4
XS GIS Cut Line= 4
2499753.02173568651632.0775703482499923.03013538651499.848815027
2500244.15711259651367.6200597062500527.50444542651222.798089592
#Sta/Elev= 30
       0  1383.9    67.6 1355.99      99 1348.78   189.7 1323.79     228 1308.43
     241 1305.69   274.1 1305.53   301.6 1302.04   307.8 1300.23  320.26  1293.2
   340.5 1288.92   378.3 1288.59   422.7 1289.08  451.02  1293.2     466 1299.65
   474.6 1305.67   529.21358.285   562.1 1385.31   594.9 1407.88     693 1482.19
   704.8 1494.73   713.9 1506.98   731.3 1522.76   746.5 1543.18   773.2 1573.35
   790.2 1590.43   803.7 1599.96   812.6 1614.18   817.1 1619.13   880.9 1665.85
#Mann= 4 ,-1 , 0
       0      .1       0  320.26    .045       0  451.02    .025       0
   529.2      .1       0
Bank Sta=320.26,451.02
XS Rating Curve= 0 ,0
Exp/Cntr(USF)=0,0
Exp/Cntr=0.3,0.1

Type RM Length L Ch R = 1 ,14473   ,371.5,362.4,351.6
XS GIS Cut Line= 4
2499702.64887651651890.2384735942499929.32674277651833.569007028
  2500218.970683651839.8656144242500508.61462323651783.196147858
#Sta/Elev= 30
       0  1428.3    37.2 1407.44   107.3 1362.51   136.2 1347.11   173.3 1332.17
   210.4  1315.2   239.1 1310.62   259.1 1308.97   275.1  1301.5   287.1 1297.85
   299.1 1292.97  309.471291.089   339.1 1285.31   356.4 1285.09   391.1 1285.14
   411.1 1286.32  433.97 1291.09   443.9 1295.89   462.8 1309.91   475.1 1320.43
  491.381337.061   515.1 1356.19     537 1371.83   612.8 1420.11  690.621471.992
   718.8 1490.04   771.8 1525.78   795.5 1542.69   803.5 1549.26   818.5 1558.98
#Mann= 5 ,-1 , 0
       0      .1       0  309.47    .045       0  433.97      .1       0
  491.38      .1       0  690.62      .1       0
Bank Sta=309.47,433.97
XS Rating Curve= 0 ,0
Exp/Cntr(USF)=0,0
Exp/Cntr=0.3,0.1

Type RM Length L Ch R = 1 ,14111   ,292.8,286.7,276.4
XS GIS Cut Line= 4
2499677.46244692 652249.145095182499872.65727621652223.958665596
2500256.75032738652173.5858064262500609.36034157652072.840088086
#Sta/Elev= 30
       0 1486.51    21.5 1471.56    33.6 1460.87    53.7 1452.58      82 1429.56
   102.1 1420.18   110.2 1411.39   158.6 1384.91   171.41375.532   203.2 1358.12
   227.2 1347.45   243.3 1333.98   263.5 1320.31   288.8 1312.88  333.811289.319
   348.2 1284.87   360.3 1284.41     445 1284.65  459.341289.321  469.48  1293.7
   485.4 1304.58   497.5 1320.72   525.7 1351.56  568.841385.458   619.6  1422.5
   636.5 1439.84  668.751462.472   785.4 1550.21   866.3 1598.87   950.9 1657.84
#Mann= 7 ,-1 , 0
       0      .1       0   171.4      .1       0  333.81    .045       0
  459.34      .1       0  469.48    .025       0  568.84      .1       0
  668.75      .1       0
Bank Sta=333.81,459.34
XS Rating Curve= 0 ,0
Exp/Cntr(USF)=0,0
Exp/Cntr=0.3,0.1

Type RM Length L Ch R = 1 ,13824   ,348.4,358.6,372
XS GIS Cut Line= 4
2499734.13191349652582.8652871822500004.88603153652507.305998427
2500363.79265312652412.8568874832500653.43659334652274.331524765
#Sta/Elev= 30
       0 1482.89      38 1464.88    71.9 1443.82   100.3 1431.59   129.4 1412.64
   146.6 1397.12     179 1378.83   208.3 1367.56     229 1353.05     238 1352.29
   253.7 1342.32   278.9 1332.51   291.3 1324.09   320.2  1310.5   359.61288.209
   378.2 1282.81   444.3 1282.59   473.3 1283.89  494.171288.206   518.8 1299.55
   560.1 1327.24   605.6  1369.7   685.9 1436.11   699.8 1449.48   713.1  1466.1
   801.8  1536.8   850.9 1580.59   894.9 1613.64  971.611667.647   973.3  1668.9
#Mann= 4 ,-1 , 0
       0      .1       0   359.6    .045       0  494.17      .1       0
  971.61      .1       0
Bank Sta=359.6,494.17
XS Rating Curve= 0 ,0
Exp/Cntr(USF)=0,0
Exp/Cntr=0.3,0.1

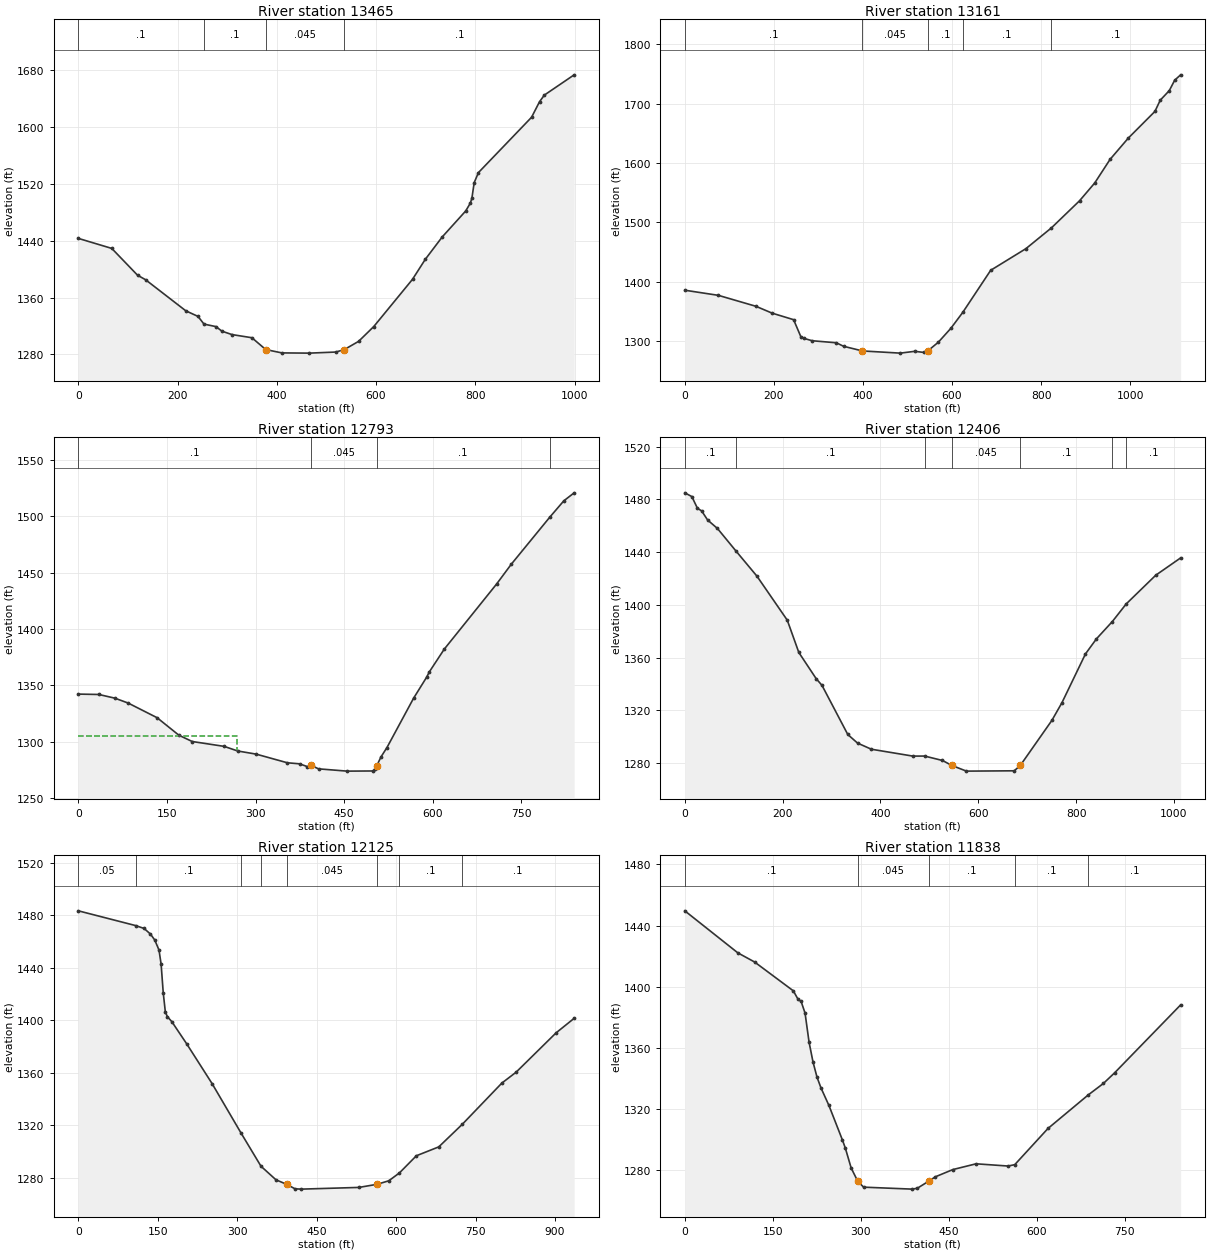
Type RM Length L Ch R = 1 ,13465   ,296.1,304.6,315.7
XS GIS Cut Line= 4
2499797.09798745652878.805834805 2500061.5554981652834.729583032
2500439.35194187652790.6533312582500766.77552648652664.721183333
#Sta/Elev= 30
       0  1443.4    67.4 1429.27   119.3 1391.55   135.5 1385.16   216.6 1341.35
   241.2 1333.46   253.31322.607   277.4 1319.09   289.4 1312.65   309.6 1307.87
   349.8 1303.42  377.731286.746   410.3 1282.03   465.7 1281.72     519 1283.25
  536.141286.746   564.8 1298.28   595.5 1319.22   673.5 1385.73   699.2 1413.84
   733.5 1445.54   780.7 1482.03   790.2 1493.24   793.3 1500.47   797.8 1521.94
   806.4 1536.13   913.5 1614.11   929.5 1635.96   939.2 1645.32   999.3 1673.89
#Mann= 4 ,-1 , 0
       0      .1       0   253.3      .1       0  377.73    .045       0
  536.14      .1       0
Bank Sta=377.73,536.14
XS Rating Curve= 0 ,0
Exp/Cntr(USF)=0,0
Exp/Cntr=0.3,0.1

Type RM Length L Ch R = 1 ,13161   ,324.1,367.7,392.3
XS GIS Cut Line= 4
2499771.91155787653086.593878881 2500061.5554981653118.076915863
2500414.16551229653118.0769158632500880.11445961653061.407449296
#Sta/Elev= 30
       0 1385.64    75.3 1377.01   159.8 1358.51     196 1347.01   244.3 1335.95
   260.4 1307.57   268.4 1304.25   285.9 1300.46   340.5 1296.98   356.5 1291.09
  398.991283.223   483.7 1279.56   516.5 1282.61   536.5 1280.74  545.521283.226
   569.4 1298.06   597.4  1321.4  624.111348.235   686.8 1419.21   765.9 1455.71
  823.141490.713   886.3 1536.41   920.4 1566.42   954.8 1606.18   995.8 1642.12
  1055.6 1687.15  1067.6 1706.14  1087.8 1722.15    1100 1739.79  1113.3 1748.83
#Mann= 5 ,-1 , 0
       0      .1       0  398.99    .045       0  545.52      .1       0
  624.11      .1       0  823.14      .1       0
Bank Sta=398.99,545.52
XS Rating Curve= 0 ,0
Exp/Cntr(USF)=0,0
Exp/Cntr=0.3,0.1

Type RM Length L Ch R = 1 ,12793   ,396.9,386.8,353.6
XS GIS Cut Line= 4
2499771.91155787653237.712456391 2500048.9622833653382.534426505
2500281.93675696653514.7631818262500527.50444542653596.619077977
#Sta/Elev= 30
       0 1342.28    34.8 1341.93    61.9 1338.66    84.4 1334.31   133.4  1321.3
   170.2 1305.78   192.8 1300.18   246.9 1295.86   269.7 1291.77   301.1 1288.97
   353.9 1281.29   374.5 1280.37   387.5 1277.93   394.4 1278.88   406.7  1275.9
     455 1273.88   498.6 1274.02     502 1275.59   504.9 1278.33   512.4 1286.51
   522.5 1294.83   567.6 1338.65   589.8 1357.41   594.2    1362   619.5  1382.2
   708.1 1440.02   733.1 1457.69  798.211499.421   821.9 1513.89   839.4 1520.99
#Mann= 4 ,-1 , 0
       0      .1       0   394.4    .045       0   504.9      .1       0
  798.21      .1       0
#XS Ineff= 2 , 0
          268.86  1304.8
Permanent Ineff=
       F       F
Bank Sta=394.4,504.9
XS Rating Curve= 0 ,0
Exp/Cntr(USF)=0,0
Exp/Cntr=0.3,0.1

Type RM Length L Ch R = 1 ,12406   ,300.3,281.6,238.7
XS GIS Cut Line= 4
2499444.48797326653716.2546185062499935.62335017653779.220692469
2500231.56389779653835.8901590352500439.35194187653772.924085072
#Sta/Elev= 30
       0 1484.89    14.4 1482.05    25.8 1473.18    34.5 1471.17    46.6 1464.31
    66.8 1457.85   104.71440.746   147.5 1421.72   209.5 1388.34   233.1 1363.87
   268.4 1344.12   280.5 1338.91   333.2  1301.7   353.1 1295.19   381.4 1290.53
     466 1285.33   490.2 1285.35   526.8    1282  545.521278.287   575.7 1273.93
   673.5 1274.18  685.951278.286   750.5 1312.43     771  1325.8   819.1  1362.8
   841.5  1374.2  874.06 1387.34  902.431400.709   962.8 1422.45  1013.6 1435.56
#Mann= 7 ,-1 , 0
       0      .1       0   104.7      .1       0   490.2     .05       0
  545.52    .045       0  685.95      .1       0  874.06      .1       0
  902.43      .1       0
Bank Sta=545.52,685.95
XS Rating Curve= 0 ,0
Exp/Cntr(USF)=0,0
Exp/Cntr=0.3,0.1

Type RM Length L Ch R = 1 ,12125   ,321.1,286.5,240.7
XS GIS Cut Line= 4
2499538.93708421654100.3476696772499853.76745402654075.161240092
2500193.78425342654043.6782031112500445.64854927653924.042662582
#Sta/Elev= 30
       0 1483.55  108.071472.318   124.2  1470.1   136.2 1465.81   144.3  1461.3
   152.3 1453.65   156.3 1442.87   160.3 1421.08   164.3 1406.35   168.3 1402.79
   176.4 1399.13   204.5 1382.22   252.6 1351.81  307.351314.069  344.861288.864
   373.1 1278.54  393.031275.117   409.2 1271.65   421.3 1271.42   529.7 1272.72
  564.261275.118     586 1277.76     606 1283.69   638.2 1296.85   680.5 1303.62
  724.811320.796   799.7 1352.29   826.4 1360.51   901.9 1390.51   936.1 1401.62
#Mann= 8 ,-1 , 0
       0     .05       0  108.07      .1       0  307.35      .1       0
  344.86    .025       0  393.03    .045       0  564.26      .1       0
     606      .1       0  724.81      .1       0
Bank Sta=393.03,564.26
XS Rating Curve= 0 ,0
Exp/Cntr(USF)=0,0
Exp/Cntr=0.3,0.1

Type RM Length L Ch R = 1 ,11838   ,398.2,401.9,402.6
XS GIS Cut Line= 4
2499815.98780964654534.8135800182499973.40299455 654415.17803949
2500300.82657915654175.9069584322500451.94515666653987.008736545
#Sta/Elev= 30
       0 1449.62    90.4 1422.07     119 1416.07     185 1397.17   193.2 1391.52
   198.2 1390.32     205 1382.58   211.8 1363.61   218.5  1350.6   225.3 1340.67
   232.1 1333.57   245.7 1322.02   268.7 1299.38   273.7 1294.03   283.6 1281.02
  294.761272.372   304.8 1268.47   387.6 1267.18   396.4 1267.76  415.71 1272.37
   427.3 1275.29     457 1280.01   496.6 1283.78     551 1282.32  562.451283.212
   619.1 1306.95  688.121329.055   713.5 1336.44   732.6 1343.39   845.2 1387.95
#Mann= 5 ,-1 , 0
       0      .1       0  294.76    .045       0  415.71      .1       0
  562.45      .1       0  688.12      .1       0
Bank Sta=294.76,415.71
XS Rating Curve= 0 ,0
Exp/Cntr(USF)=0,0
Exp/Cntr=0.3,0.1

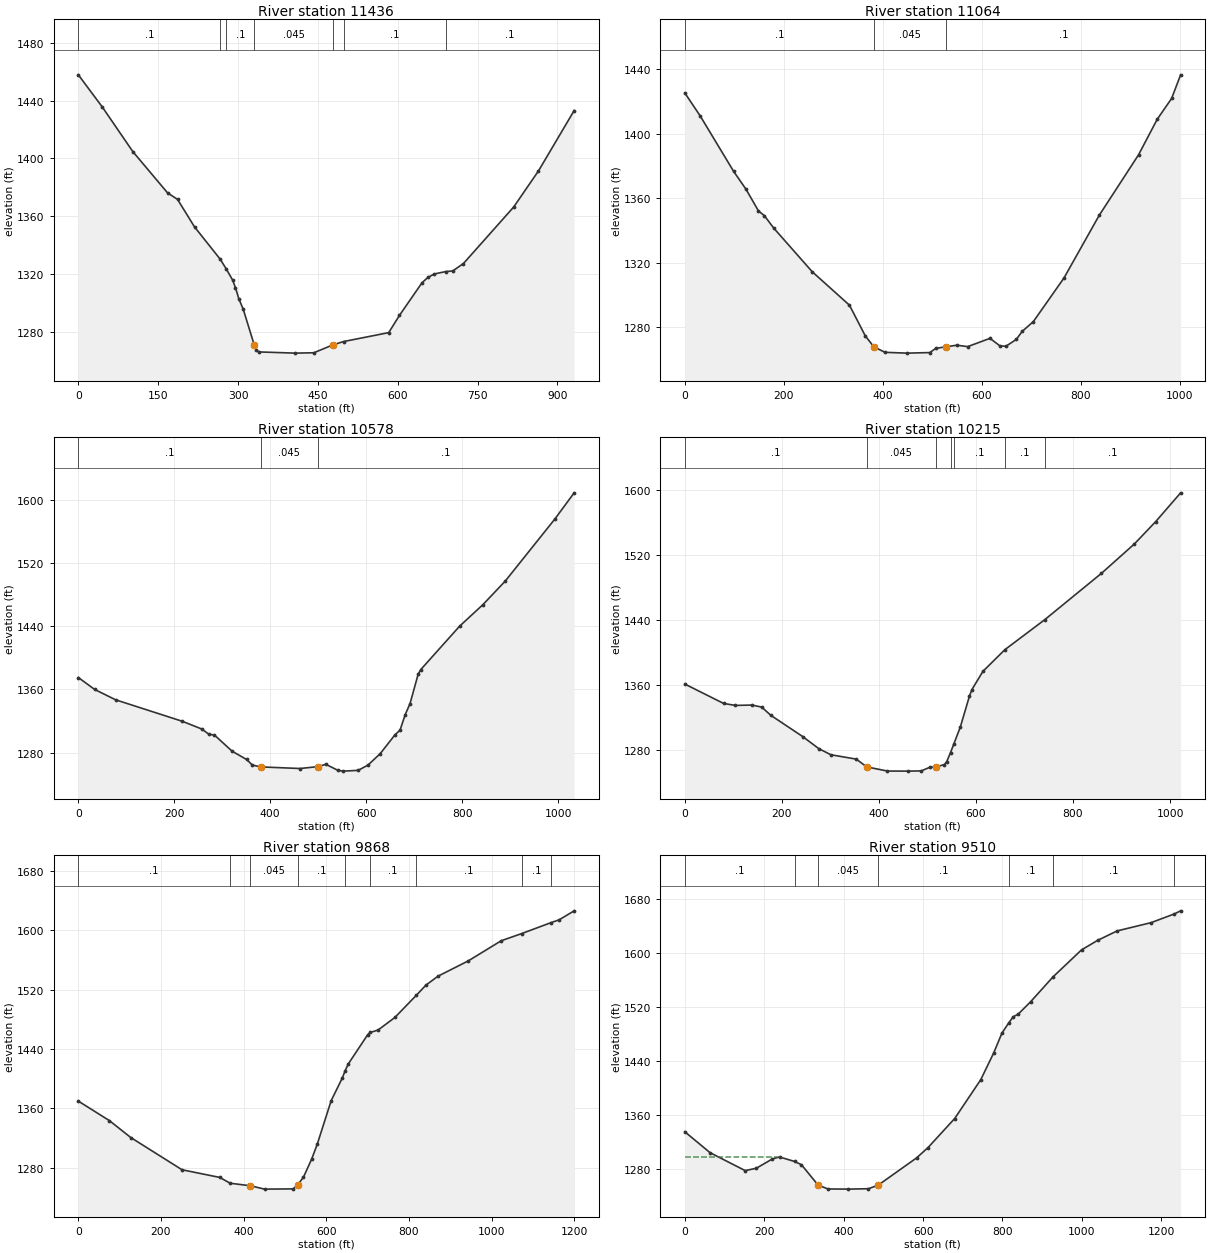
Type RM Length L Ch R = 1 ,11436   ,384.3,372.8,361.8
XS GIS Cut Line= 4
2500017.47924632654855.9405572272500244.15711259654704.821979717
 2500558.9874824654484.440720848 2500722.6992747 654264.05946198
#Sta/Elev= 30
       0 1457.86    44.9 1435.64   102.5 1404.63   167.7 1376.09   186.3 1371.63
   218.2 1352.57   266.61330.142  277.871323.419   289.8 1315.73   295.1 1310.51
   301.5 1302.74   309.8 1295.46   330.41270.806   334.2 1267.51   338.6 1265.99
   407.4 1265.15   442.3  1265.4  477.781270.807  498.461273.189     583 1279.35
   603.1 1291.24   645.5 1313.86   656.4 1317.53   668.6 1319.95  689.721321.601
   703.3 1322.08   723.4 1327.21   817.8 1366.37   864.3 1391.33   931.3 1433.12
#Mann= 7 ,-1 , 0
       0      .1       0   266.6    .025       0  277.87      .1       0
   330.4    .045       0  477.78      .1       0  498.46      .1       0
  689.72      .1       0
Bank Sta=330.4,477.78
XS Rating Curve= 0 ,0
Exp/Cntr(USF)=0,0
Exp/Cntr=0.3,0.1

Type RM Length L Ch R = 1 ,11064   ,484.8,485.9,484
XS GIS Cut Line= 4
2500250.45371998655208.5505714172500439.35194187655057.431993907
2500804.55517085654711.1185871132500880.11445961 654465.55089866
#Sta/Elev= 30
       0 1425.29    31.1 1411.02    98.7 1376.66   123.8 1365.52   148.9 1352.13
   160.8 1349.21   179.7 1341.51   257.6 1314.42   332.8 1293.71   364.9 1274.63
  382.021267.936   404.6 1264.49   449.1    1264   495.1 1264.34   507.2 1266.94
  527.851267.936   549.8  1268.9   571.8 1268.04   616.8 1273.16   636.6 1268.55
     649 1268.25     670 1272.51   681.8 1277.45   704.5 1283.56   766.3 1310.55
   837.5 1349.38     917 1386.89   954.7 1408.89   983.9 1421.86  1002.1 1436.49
#Mann= 3 ,-1 , 0
       0      .1       0  382.02    .045       0  527.85      .1       0
Bank Sta=382.02,527.85
XS Rating Curve= 0 ,0
Exp/Cntr(USF)=0,0
Exp/Cntr=0.3,0.1

Type RM Length L Ch R = 1 ,10578   ,348.2,362.5,373
XS GIS Cut Line= 4
2500609.36034157655466.7114746632500842.33481523655328.186111946
2501169.75839983655032.2455643222501383.84305131654792.974483264
#Sta/Elev= 30
       01375.104  34.1871359.925  77.9151346.821 216.8411319.625 257.5631309.793
 272.2541303.144 283.5821302.271 320.7011281.662 350.5281271.294 362.8791264.172
 380.3551261.842 462.0011259.811 499.6621262.189 515.8091265.129 541.1871257.448
 551.9711256.493 583.1761257.448 603.6021264.092  629.091278.545 659.8061302.365
  670.591308.471 681.3731328.177 691.3951342.062 708.3321379.393 713.8731385.255
 794.7221440.164 843.0291467.299 889.6851497.185 993.3161575.9981033.4591609.118
#Mann= 3 , 0 , 0
       0      .1       0 380.355    .045       0 499.662      .1       0
Bank Sta=380.355,499.662
XS Rating Curve= 0 ,0
Exp/Cntr(USF)=0,0
Exp/Cntr=0.3,0.1

Type RM Length L Ch R = 1 ,10215   ,349.9,347.3,341.3
XS GIS Cut Line= 4
2500810.85177825655731.1689853052500943.08053357655643.016481758
2501339.76679953655397.4487933042501616.81752497655114.101460473
#Sta/Elev= 30
       0 1360.97    79.8 1337.17     104  1334.7   138.6 1335.13   158.5  1332.6
   177.3 1322.52   242.8 1296.47   276.1 1281.57   301.1 1274.04   353.4 1268.66
  374.821259.125   417.4 1254.03   459.6 1253.92   487.1 1254.21   504.5 1258.54
  517.671259.125   534.9 1261.99   539.6  1265.4  547.581276.748  554.181286.962
   567.8 1308.23   586.6 1346.23   591.7 1354.25   614.4 1376.63   659.51403.185
  741.871440.168   858.6 1497.08   926.4 1533.19   970.3  1560.6  1021.7 1596.02
#Mann= 7 ,-1 , 0
       0      .1       0  374.82    .045       0  517.67      .1       0
  547.58     .12       0  554.18      .1       0   659.5      .1       0
  741.87      .1       0
Bank Sta=374.82,517.67
XS Rating Curve= 0 ,0
Exp/Cntr(USF)=0,0
Exp/Cntr=0.3,0.1

Type RM Length L Ch R = 1 ,9868    ,399.4,358.3,308.9
XS GIS Cut Line= 4
2500943.08053357656083.7789994952501157.16518504655938.957029382
2501572.74127319655617.8300521732501698.67342112655221.143786209
#Sta/Elev= 30
       0 1369.87    75.3 1343.57   127.1 1320.81     251 1277.49   342.3 1267.19
  367.311259.398   416.5 1255.96   450.7 1251.45   520.3 1251.79  531.58 1257.63
   544.8 1267.55   564.8 1292.03   578.3 1312.04   611.8 1370.39   638.9 1401.06
  645.151410.036   653.2  1419.8   700.3 1459.24  706.291462.171   725.5 1465.52
     766 1482.37   817.91512.197   841.3 1525.96   870.4 1537.92   943.7 1558.53
  1023.3 1585.58 1073.161595.319 1144.691610.136  1163.5 1613.73  1199.9 1625.86
#Mann= 9 ,-1 , 0
       0      .1       0  367.31      .1       0   416.5    .045       0
  531.58      .1       0  645.15     .12       0  706.29      .1       0
   817.9      .1       0 1073.16      .1       0 1144.69     .12       0
Bank Sta=416.5,531.58
XS Rating Curve= 0 ,0
Exp/Cntr(USF)=0,0
Exp/Cntr=0.3,0.1

Type RM Length L Ch R = 1 ,9510    ,474.7,448.1,414.5
XS GIS Cut Line= 4
 2501402.7328735656436.3890136852501509.77519923656222.304362213
2501648.30056195655787.8384518722501761.63949508655246.330215794
#Sta/Elev= 30
       0 1335.58    63.7 1304.55   152.1 1278.01     180 1281.53   220.8 1295.39
   238.7 1298.22  276.341291.584   293.8 1286.75  335.831256.511   360.6  1250.9
   410.9 1250.62   462.5 1251.23  487.03 1256.51   583.5 1296.77   612.4 1312.06
   679.6 1355.14   745.4 1412.74   778.1 1452.52   798.5 1481.46  815.821496.769
   827.1 1505.81   839.4 1509.58   870.6 1527.86  927.341564.891     999  1604.8
  1039.6 1618.91  1088.7 1632.89  1174.5 1645.18 1232.741658.038  1248.6 1662.63
#Mann= 7 ,-1 , 0
       0      .1       0  276.34      .1       0  335.83    .045       0
  487.03      .1       0  815.82      .1       0  927.34      .1       0
 1232.74     .12       0
#XS Ineff= 2 , 0
          243.56 1298.71
Permanent Ineff=
       F       F
Bank Sta=335.83,487.03
XS Rating Curve= 0 ,0
Exp/Cntr(USF)=0,0
Exp/Cntr=0.3,0.1