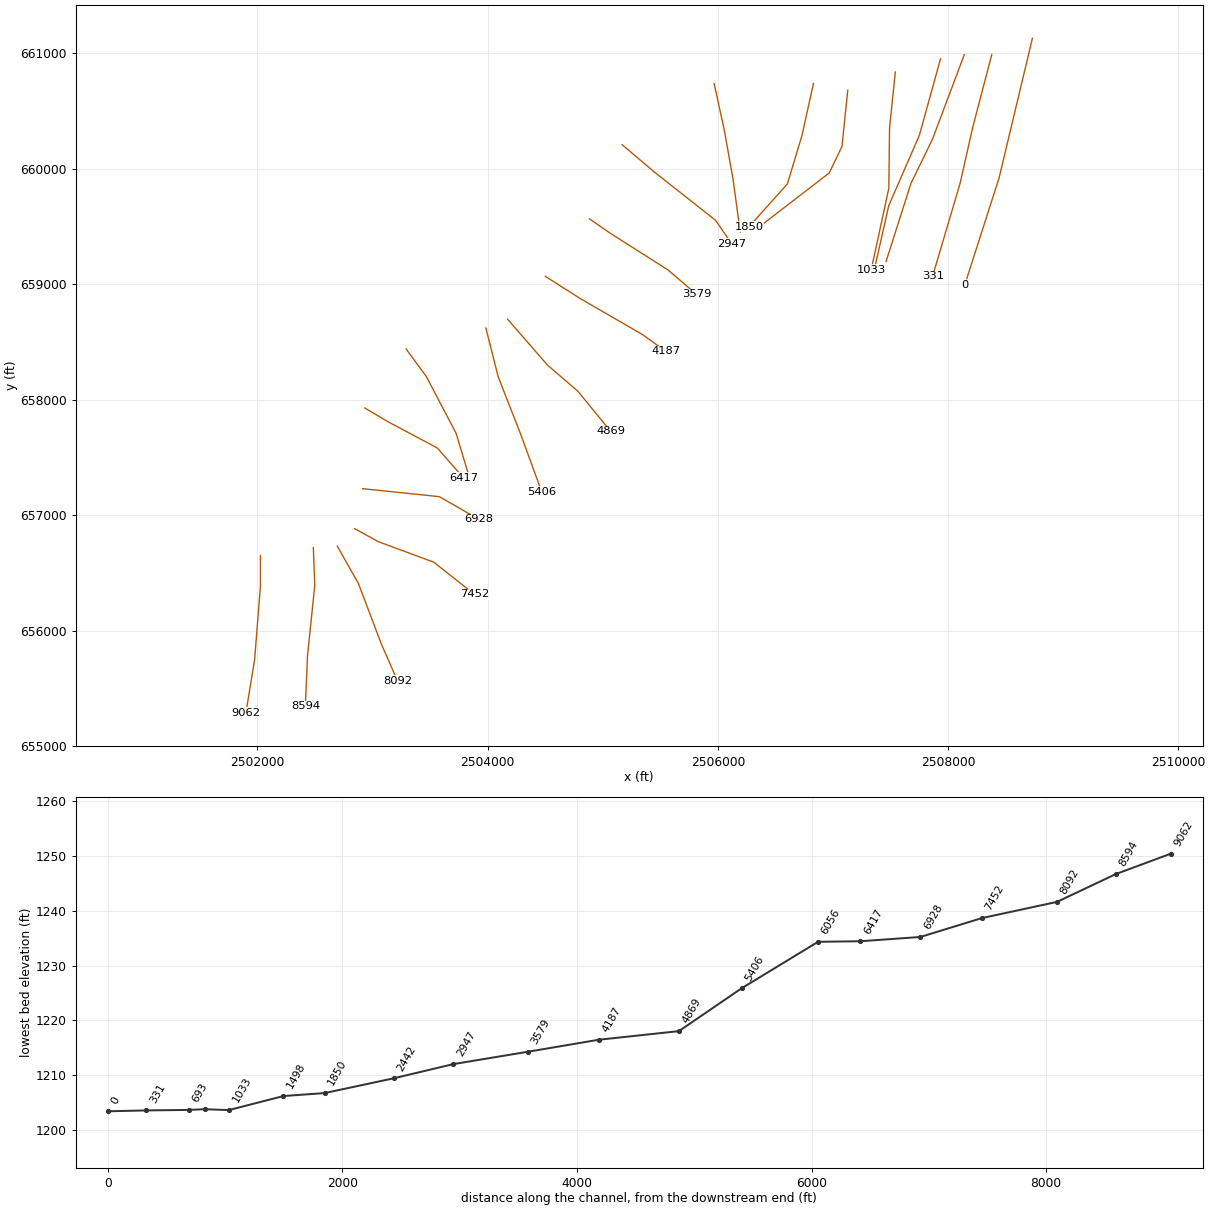
HEC-RAS study SFSBPOTOMC.prj: SFSBPOTOMC

--- SFSBPOTOMC.g01 (geometry) --- (continued)

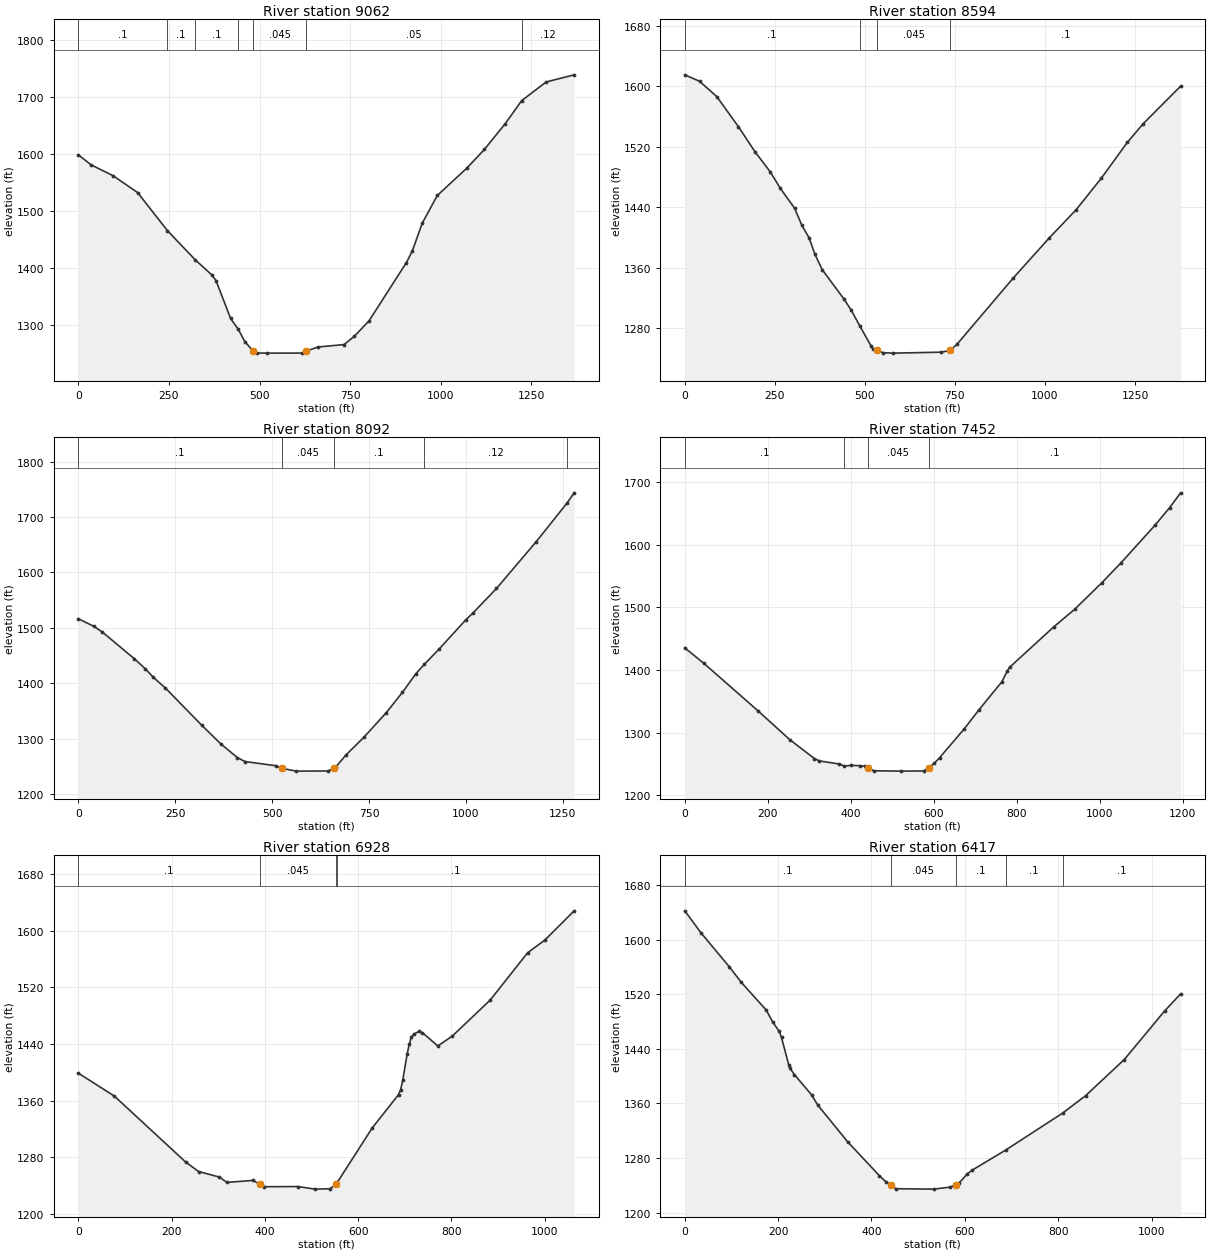
Type RM Length L Ch R = 1 ,9062    ,469.2,467.4,460.3
XS GIS Cut Line= 4
2502026.09700572656650.4736651572502026.09700572656386.016154515
2501975.72414655655750.058807494 2501900.1648578655290.406467568
#Sta/Elev= 30
       0 1598.88    35.6  1581.2    95.6 1562.37   163.6 1532.62   245.71465.834
   321.71414.953   367.9 1388.14   379.9 1377.95   420.1  1311.4   441.5 1291.99
   460.1 1269.98  482.771254.131   492.3 1250.53   519.6 1250.38   616.7 1250.48
  629.471254.129   660.8 1261.12     733 1265.41   761.3 1279.74   802.2 1307.17
   905.1 1409.34   921.8 1430.19   948.7 1478.48   990.7 1527.61  1071.8  1575.4
  1120.5 1608.46  1177.6 1653.38  1223.11694.047  1290.7 1726.98  1368.2 1739.59
#Mann= 7 ,-1 , 0
       0      .1       0   245.7      .1       0   321.7      .1       0
   441.5      .1       0  482.77    .045       0  629.47     .05       0
  1223.1     .12       0
Bank Sta=482.77,629.47
XS Rating Curve= 0 ,0
Exp/Cntr(USF)=0,0
Exp/Cntr=0.3,0.1

Type RM Length L Ch R = 1 ,8594    ,464.9,501.9,553.5
XS GIS Cut Line= 4
2502485.74934565656719.7363465162502498.34256044656392.312761911
2502435.37648648655787.8384518722502416.48666429655347.075934134
#Sta/Elev= 30
       0 1615.39    40.9 1606.85    88.9  1586.5     149  1546.6   194.5 1513.73
   236.9 1487.09     265 1465.15   305.1 1438.44   325.1 1415.89   345.2 1399.34
   361.3  1377.6   381.4 1357.31   441.7 1318.48   461.8 1303.82  485.541282.953
     518 1255.46   522.1 1252.78   533.41250.274   550.3 1247.24   578.4 1246.67
     711  1247.9  737.111250.273   755.4 1258.27   912.2 1346.35  1012.4 1399.57
  1086.7  1436.8  1156.6 1478.51  1228.6 1525.86  1272.7 1550.61  1376.6 1600.36
#Mann= 4 ,-1 , 0
       0      .1       0  485.54     .05       0   533.4    .045       0
  737.11      .1       0
Bank Sta=533.4,737.11
XS Rating Curve= 0 ,0
Exp/Cntr(USF)=0,0
Exp/Cntr=0.3,0.1

Type RM Length L Ch R = 1 ,8092    ,557.9,640,681.9
XS GIS Cut Line= 4
2502693.53738973656732.3295613092502876.13900422  656411.2025841
 2503077.6304409655882.2875628152503216.15580362655567.457193003
#Sta/Elev= 30
       0 1516.53    40.1 1502.83    61.5 1492.84   144.3 1444.49   172.1 1426.76
   192.6 1411.45   224.9  1391.4     318 1324.73   368.6 1290.14   410.4 1266.04
   429.7 1258.96     511 1251.16  525.411246.547   562.4  1241.6   644.4 1241.88
  658.671246.544   665.1  1249.8   690.9 1270.94   737.9 1303.51   793.5  1346.2
   836.3 1383.63   871.1 1417.49  892.561434.189   930.5 1461.59   999.5 1514.36
  1017.8 1526.55    1079 1571.15  1181.8 1655.83 1261.06 1725.34  1279.4 1743.74
#Mann= 5 ,-1 , 0
       0      .1       0  525.41    .045       0  658.67      .1       0
  892.56     .12       0 1261.06    .025       0
Bank Sta=525.41,658.67
XS Rating Curve= 0 ,0
Exp/Cntr(USF)=0,0
Exp/Cntr=0.3,0.1

Type RM Length L Ch R = 1 ,7452    ,495.3,524.1,534.1
XS GIS Cut Line= 4
2502844.65596724656883.4481388192503052.44401131656770.109205686
2503530.98617343656593.8041985912503883.59618762656316.753473156
#Sta/Elev= 30
       0  1435.2    46.2 1410.43   175.9 1335.14   253.4 1288.63   312.6 1258.65
   324.4 1254.91   371.3 1250.12  384.891246.741   401.1 1247.96   422.4 1247.26
   435.2 1246.29   441.41243.803   455.9 1239.21   520.5 1238.65   575.9 1238.95
  587.481243.803   601.5 1251.29   614.3  1260.2   673.9 1306.32   708.8  1336.3
   764.3  1381.2   777.3 1398.32   782.8  1404.2   888.8  1468.4   939.7 1496.78
    1005 1538.93  1051.6    1571  1133.2 1630.71  1168.6 1658.83  1195.1  1682.5
#Mann= 4 ,-1 , 0
       0      .1       0  384.89      .1       0   441.4    .045       0
  587.48      .1       0
Bank Sta=441.4,587.48
XS Rating Curve= 0 ,0
Exp/Cntr(USF)=0,0
Exp/Cntr=0.3,0.1

Type RM Length L Ch R = 1 ,6928    ,529.8,511.1,479
XS GIS Cut Line= 4
 2502913.9186486657229.7615456122503096.52026309657210.871723424
 2503581.3590326657160.4988642542503921.37583199 656965.30403497
#Sta/Elev= 30
       0 1398.94    77.2 1366.56     230  1273.5   257.9 1260.04   302.4 1252.25
   318.5 1244.73   374.8 1247.55  388.861242.021     399 1238.63   471.3 1238.83
   507.5 1235.21   539.7 1235.76  552.351242.021  555.311244.771     630 1321.44
   686.5 1368.57   691.1 1375.72   695.7 1389.47   704.9 1425.44   709.5 1439.79
   714.1 1449.43   718.7 1453.87   730.5 1457.81   737.7 1456.18   770.7 1437.24
   801.8 1451.24   883.1 1502.06   963.3 1568.83  1000.1 1586.62  1063.1 1628.01
#Mann= 4 ,-1 , 0
       0      .1       0  388.86    .045       0  552.35      .1       0
  555.31      .1       0
Bank Sta=388.86,552.35
XS Rating Curve= 0 ,0
Exp/Cntr(USF)=0,0
Exp/Cntr=0.3,0.1

Type RM Length L Ch R = 1 ,6417    ,401.5,360.8,313.6
XS GIS Cut Line= 4
2502932.80847078657928.6849665962503134.29990746657809.049426067
2503562.46921041657582.3715598022503789.14707667657324.210656556
#Sta/Elev= 30
       0 1642.39    34.8 1610.03    95.3 1560.42     121  1537.6   174.4 1496.94
   188.3 1479.53   202.3 1465.69   207.2 1456.82   222.9  1416.2   225.5 1411.43
   234.8 1402.34   271.8  1372.5   284.6 1357.92   348.7 1304.04   416.8 1254.21
   431.6 1244.76  441.261240.571   452.3    1235   533.5 1234.43   567.7 1237.32
  580.721240.573   588.4 1243.98   605.3 1256.67     615 1261.91   687.8 1291.81
  809.461345.818   858.7 1371.35   941.7 1424.42  1028.4 1495.82  1062.4 1520.65
#Mann= 5 ,-1 , 0
       0      .1       0  441.26    .045       0  580.72      .1       0
   687.8      .1       0  809.46      .1       0
Bank Sta=441.26,580.72
XS Rating Curve= 0 ,0
Exp/Cntr(USF)=0,0
Exp/Cntr=0.3,0.1

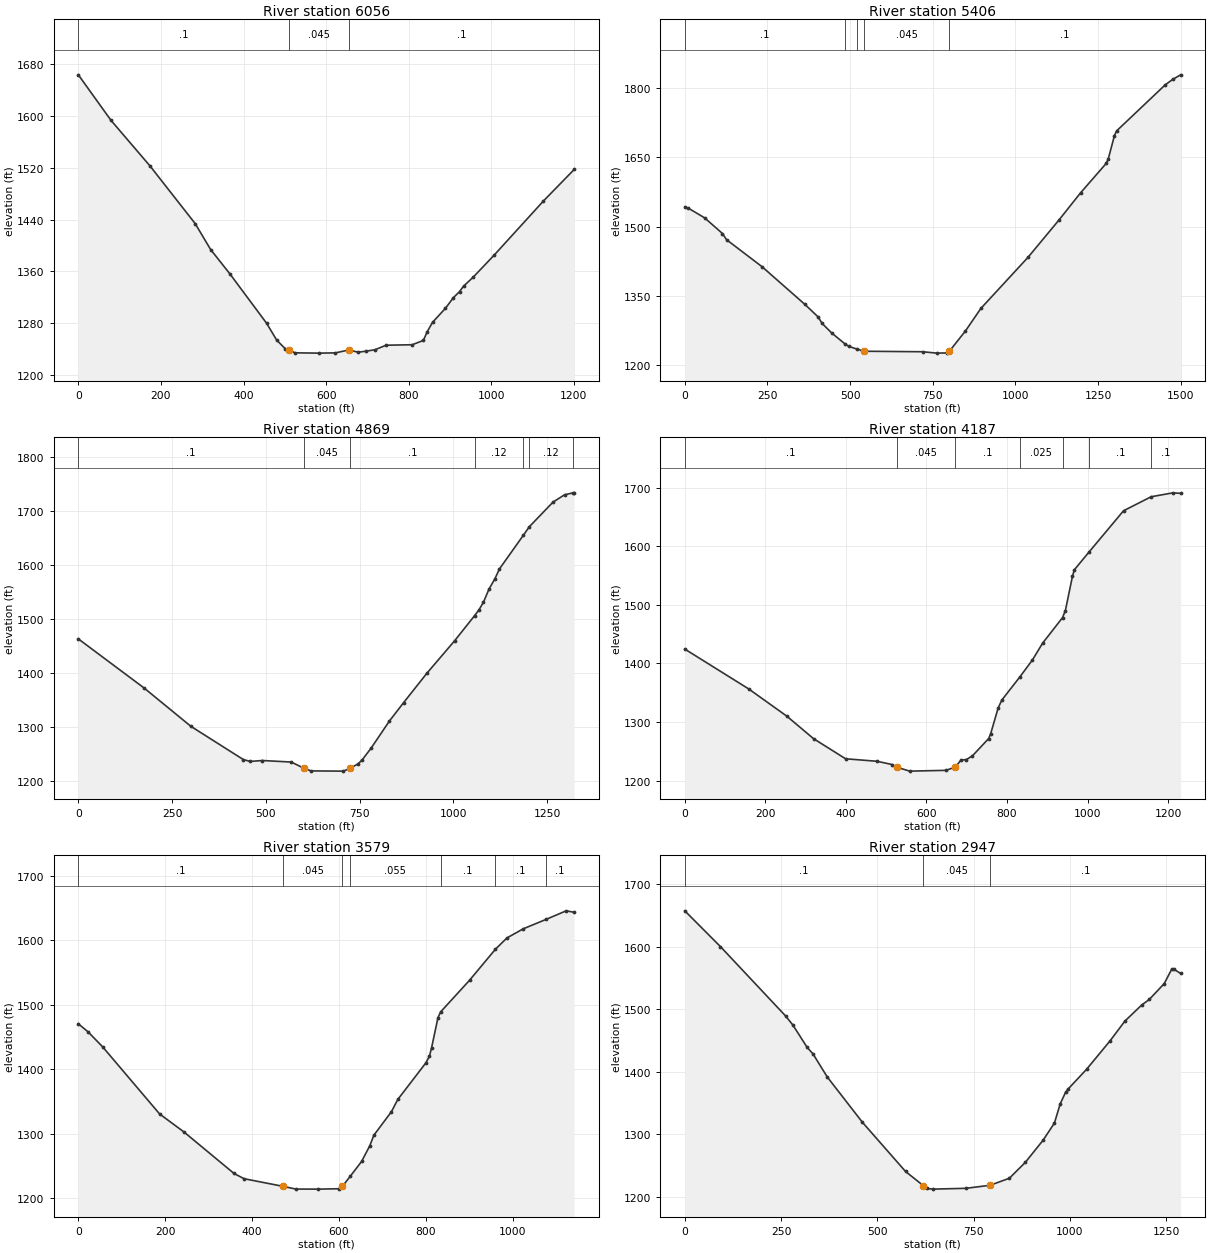
Type RM Length L Ch R = 1 ,6056    ,586.3,650.2,621.2
XS GIS Cut Line= 4
2503291.71509237658438.7101656922503468.02009946658199.439084634
2503726.18100271657708.3037077272503826.92672105657374.583515726
#Sta/Elev= 30
       0 1662.67    79.3 1592.44   173.7  1522.3     283 1433.66   320.4 1393.78
   367.8 1355.67     456 1280.23   480.3  1254.4     501 1241.15  510.931238.855
   524.7 1234.79   582.5 1234.33   622.5 1234.71   655.1  1239.2   677.4 1235.78
   695.5 1237.22   718.1 1239.49   745.2  1246.5   808.5 1247.24   835.6 1253.92
   844.6 1266.97   857.7 1281.71     889 1303.35   908.2 1319.63   923.2 1329.08
   932.9 1337.39   956.4 1351.36  1006.3  1384.7  1126.4 1468.54  1200.7 1516.97
#Mann= 3 ,-1 , 0
       0      .1       0  510.93    .045       0   655.1      .1       0
Bank Sta=510.93,655.1
XS Rating Curve= 0 ,0
Exp/Cntr(USF)=0,0
Exp/Cntr=0.3,0.1

Type RM Length L Ch R = 1 ,5406    ,474.5,536.7,555.4
XS GIS Cut Line= 4
2503984.34190596658621.3117801832504091.38423169658199.439084634
2504286.57906098657702.0071003312504469.18067547657204.575116027
#Sta/Elev= 30
       0  1542.8    10.8  1539.9    60.3 1518.76   113.9 1484.97   126.3 1471.57
   233.6 1413.13   362.8 1331.71   402.8 1304.61   415.4 1290.14   444.4 1269.49
  483.831246.204     496 1240.51   521.31234.493  542.011229.947   719.1 1228.88
   762.3 1225.88   792.5 1226.33   800.21229.945   848.7 1273.87   895.6 1322.91
  1037.6 1433.13  1130.6 1513.41  1196.7 1572.96  1274.5 1636.93  1280.7 1646.69
  1299.4  1697.3  1305.7 1707.15  1452.2 1806.61  1475.7 1819.03  1499.5 1828.79
#Mann= 5 ,-1 , 0
       0      .1       0  483.83      .1       0   521.3      .1       0
  542.01    .045       0   800.2      .1       0
Bank Sta=542.01,800.2
XS Rating Curve= 0 ,0
Exp/Cntr(USF)=0,0
Exp/Cntr=0.3,0.1

Type RM Length L Ch R = 1 ,4869    ,668.9,682.6,693.6
XS GIS Cut Line= 4
2504173.24012785658696.8710689382504519.55353464658300.184802974
2504784.01104528 658073.506936712505067.35837811657727.193529916
#Sta/Elev= 30
       0 1463.42   175.4 1372.28   300.1 1301.22   440.2 1239.46   458.5 1236.07
   491.1 1237.72   567.7  1234.9   602.3 1223.24   620.5 1218.47   706.8 1218.05
   725.5 1223.39   746.8 1231.94   756.7 1238.67   780.6 1260.44   829.7 1311.06
   867.3 1344.92   929.9  1399.9  1003.8  1460.1 1056.621506.323  1068.7  1517.5
  1080.5 1531.45  1095.3 1555.82  1110.8 1574.65  1123.2 1593.27 1187.121655.915
 1202.711671.419  1265.9 1717.11  1296.9 1730.83 1319.721734.414  1322.4 1734.36
#Mann= 7 ,-1 , 0
       0      .1       0   602.3    .045       0   725.5      .1       0
 1056.62     .12       0 1187.12      .1       0 1202.71     .12       0
 1319.72      .1       0
Bank Sta=602.3,725.5
XS Rating Curve= 0 ,0
Exp/Cntr(USF)=0,0
Exp/Cntr=0.3,0.1

Type RM Length L Ch R = 1 ,4187    ,610.4,607.5,604.2
XS GIS Cut Line= 4
2504500.66371245659068.3709053172504809.19747487658873.176076033
2505344.40910355658564.6423136172505545.90054023658419.820343503
#Sta/Elev= 30
       0 1424.57   158.7 1356.61   253.3 1310.19   319.6 1271.85   399.2 1237.54
   477.7 1233.25   514.6 1227.71   526.6 1223.12   558.3 1216.48   648.5 1217.81
   671.6  1223.4   685.5 1235.19   699.3 1236.29   714.1 1242.51   754.5  1272.1
   759.3 1280.02   777.9 1323.96     787 1337.56  831.621376.877   862.9  1405.8
   888.6 1434.89  937.821478.166   944.9 1490.26   962.4 1548.44   967.1 1559.73
 1004.661590.907  1089.2 1660.34 1157.751684.242    1212 1690.95    1231 1690.06
#Mann= 7 ,-1 , 0
       0      .1       0   526.6    .045       0   671.6      .1       0
  831.62    .025       0  937.82      .1       0 1004.66      .1       0
 1157.75      .1       0
Bank Sta=526.6,671.6
XS Rating Curve= 0 ,0
Exp/Cntr(USF)=0,0
Exp/Cntr=0.3,0.1

Type RM Length L Ch R = 1 ,3579    ,634.8,632.5,618.6
XS GIS Cut Line= 4
2504884.75676362 659565.802889622505067.35837811659439.870741695
2505564.79036242659125.0403718832505816.65465827 658910.95572041
#Sta/Elev= 30
       0 1470.45    21.9 1458.28    55.9 1434.77   187.1  1330.7   242.4 1303.22
   358.3 1238.56   381.5 1230.41     472 1218.49   500.4 1214.38   552.5 1214.28
     599 1214.88   607.7 1218.51  625.671234.109   651.9 1257.12   670.8 1281.48
   680.1 1297.76   720.7 1334.35   735.2  1353.2   799.6 1409.71   808.1 1420.34
   813.1 1433.64   827.6 1479.79  833.821488.901   900.3 1537.85  960.031586.082
   986.5 1603.49  1023.8 1617.55 1076.081632.105  1122.7 1645.47  1141.1 1643.27
#Mann= 7 ,-1 , 0
       0      .1       0     472    .045       0   607.7      .1       0
  625.67    .055       0  833.82      .1       0  960.03      .1       0
 1076.08      .1       0
Bank Sta=472,607.7
XS Rating Curve= 0 ,0
Exp/Cntr(USF)=0,0
Exp/Cntr=0.3,0.1

Type RM Length L Ch R = 1 ,2947    ,549.6,504.6,439.9
XS GIS Cut Line= 4
2505168.10409645660208.0568440372505451.45142928 659968.78576298
2505980.36645057659553.2096748282506118.89181329659351.718238148
#Sta/Elev= 30
       0 1657.82    92.5 1600.58   262.2 1489.19   280.9 1474.75   317.6 1439.29
   333.3 1428.41   369.9 1391.83   461.5 1319.02   573.4 1240.34   619.5 1217.69
   629.4 1213.06   644.7 1212.04   730.6 1213.35   793.3 1218.26   843.1 1229.46
   884.5 1254.86   930.7 1290.37   960.1  1317.8   975.3 1348.78     989 1366.93
   995.5 1372.27  1043.5 1403.86  1104.6 1449.46  1143.4 1481.33  1187.1 1507.03
  1206.5 1515.82  1245.4 1541.26  1264.8 1564.25  1269.6 1564.65    1288 1557.52
#Mann= 3 ,-1 , 0
       0      .1       0   619.5    .045       0   793.3      .1       0
Bank Sta=619.5,793.3
XS Rating Curve= 0 ,0
Exp/Cntr(USF)=0,0
Exp/Cntr=0.3,0.1

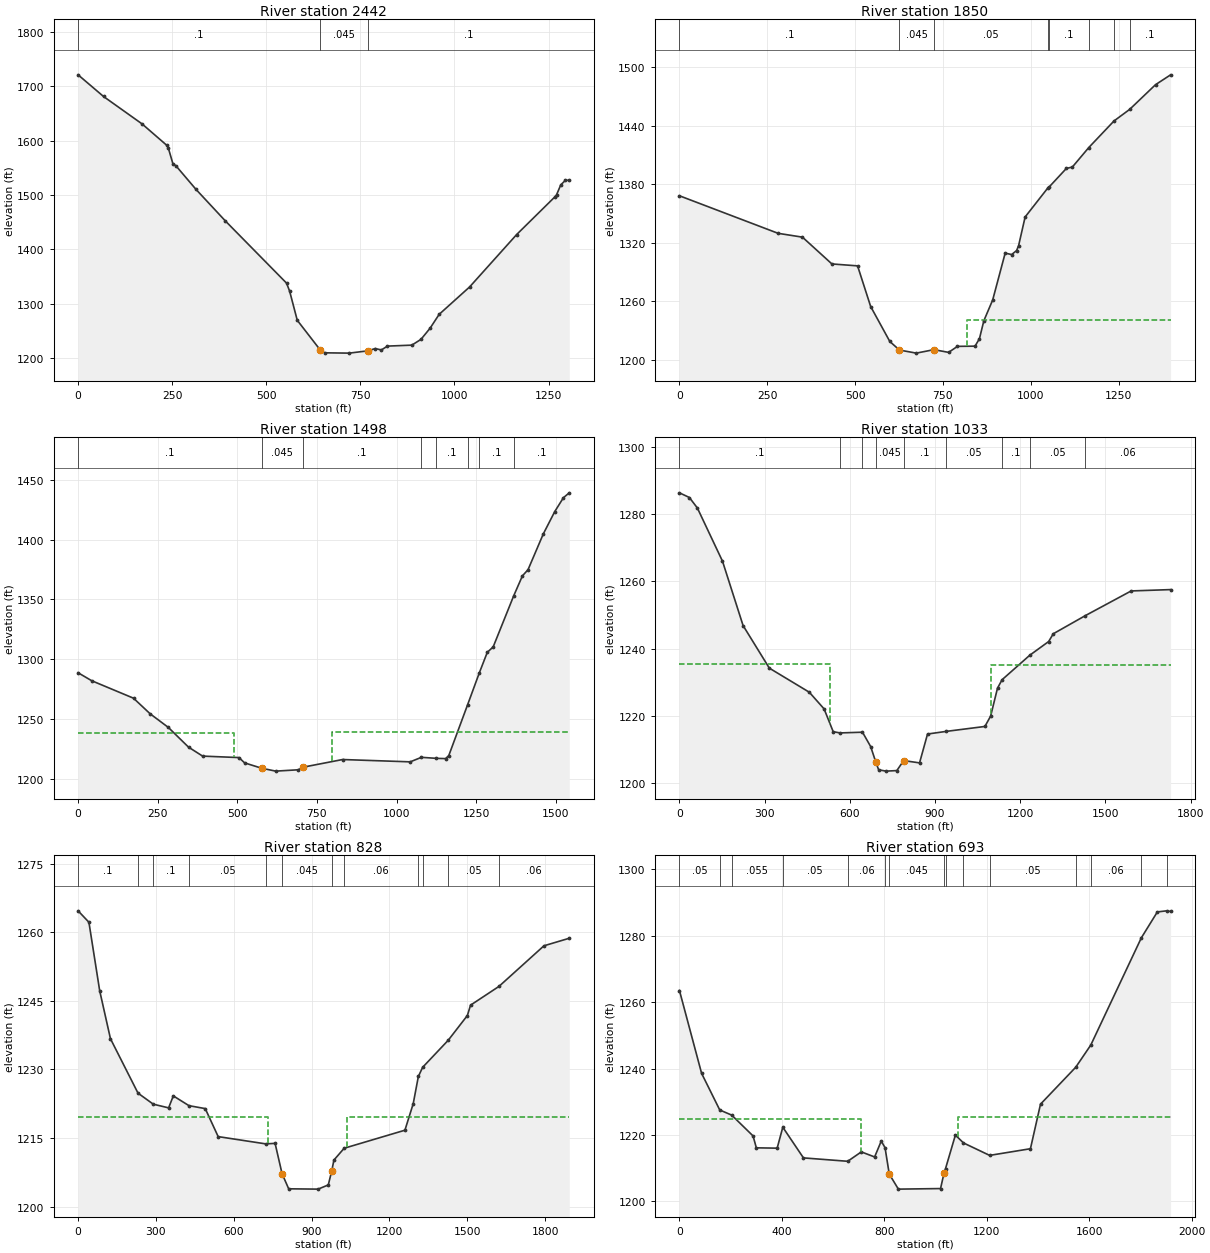
Type RM Length L Ch R = 1 ,2442    ,599.2,592.3,546.8
XS GIS Cut Line= 4
2505967.77323578660736.9718653222506055.92573932660333.988991962
2506131.48502808659912.1162964142506194.45110204659452.463956488
#Sta/Elev= 30
       0 1721.09    67.6 1681.25     170 1630.84   235.5 1591.57   239.6  1586.8
   251.9 1557.65   260.1 1553.73   313.3 1510.44   391.1  1452.6   553.8 1338.18
     562 1323.45   582.3 1269.84   643.2 1215.37   655.4 1210.03   720.4 1209.47
   769.1 1213.62   789.5 1217.86   805.8 1215.34     822 1222.38   886.7 1224.16
     911 1234.79   935.2 1255.27   959.4 1280.84  1040.2 1331.13  1165.3 1427.55
  1266.3 1496.41  1271.2 1500.51  1282.4 1518.78  1294.5 1527.01    1305 1527.41
#Mann= 3 ,-1 , 0
       0      .1       0   643.2    .045       0   769.1      .1       0
Bank Sta=643.2,769.1
XS Rating Curve= 0 ,0
Exp/Cntr(USF)=0,0
Exp/Cntr=0.3,0.1

Type RM Length L Ch R = 1 ,1850    ,359.9,351.5,332.1
XS GIS Cut Line= 4
2506830.40844906660736.9718653222506729.66273072660283.616132792
 2506603.7305828 659868.04004464 2506270.0103908659496.540208261
#Sta/Elev= 30
       0 1368.18   280.8 1329.67   350.1 1325.73   433.9 1298.26     507 1296.28
   544.3 1254.54   598.8  1218.7   626.2 1209.91   674.2 1206.76   724.3 1210.32
   766.1 1207.54   791.3  1213.7   841.3 1213.91   853.9  1221.6   866.4 1239.98
   891.5 1261.23   927.1 1309.36   945.5  1307.9   959.6 1311.97   965.3    1317
   983.9 1346.45 1048.451376.178 1053.111377.564  1101.3 1396.26  1118.3 1397.66
  1164.91417.596 1236.811444.924 1281.341456.785    1355 1482.15    1398 1492.27
#Mann= 8 ,-1 , 0
       0      .1       0   626.2    .045       0   724.3     .05       0
 1048.45      .1       0 1053.11      .1       0  1164.9      .1       0
 1236.81      .1       0 1281.34      .1       0
#XS Ineff= 2 , 0
                          818.11         1240.41
Permanent Ineff=
       F       F
Bank Sta=626.2,724.3
XS Rating Curve= 0 ,0
Exp/Cntr(USF)=0,0
Exp/Cntr=0.3,0.1

Type RM Length L Ch R = 1 ,1498    ,448.5,465.3,508.3
XS GIS Cut Line= 4
2507128.69133464 660679.930898922507078.19883993660193.366858982
2506968.03339692659963.8555193892506334.58209964659477.291479451
#Sta/Elev= 30
       0 1288.58    42.8 1281.89     174 1267.28   226.2 1254.22   283.3 1242.83
   346.9 1226.28   391.1 1218.79   505.2 1217.57     523 1213.11   576.2 1208.67
   620.6 1206.22   691.6 1207.34   706.5 1209.52   830.7 1215.93    1043 1213.99
 1078.111217.776 1125.251216.921  1153.9  1216.7    1164 1219.17 1223.021261.636
 1260.051288.515  1285.1 1305.72  1303.5  1310.2 1367.931352.955  1395.4 1369.72
  1412.9 1374.82  1461.1  1404.9  1496.9 1423.51  1524.1 1435.12  1542.5 1439.21
#Mann= 8 ,-1 , 0
       0      .1       0   576.2    .045       0   706.5      .1       0
 1078.11      .1       0 1125.25      .1       0 1223.02      .1       0
 1260.05      .1       0 1367.93      .1       0
#XS Ineff= 2 , 0
          489.44 1238.28   798.9         1238.75
Permanent Ineff=
       F       F
Bank Sta=576.2,706.5
XS Rating Curve= 0 ,0
Exp/Cntr(USF)=0,0
Exp/Cntr=0.3,0.1

Type RM Length L Ch R = 1 ,1033    ,228.9,204.5,148.1
XS GIS Cut Line= 4
2507541.92508484660837.7175836622507491.55222567660352.878814151
2507485.25561827659830.2604002622507332.60066856659127.156031968
#Sta/Elev= 30
       0 1286.34      35 1284.95    63.2 1281.82   151.6 1266.03   224.1  1246.9
   316.5 1234.26   457.3  1227.1   509.4 1222.14   541.4 1215.38  565.31 1215.01
  644.581215.223   673.4 1210.95   691.8 1206.25   701.5 1204.05   727.5 1203.66
   765.5 1203.82   789.5 1206.79   845.5 1206.11   873.6 1214.68  940.171215.474
  1075.6 1216.93  1095.8 1220.01    1120 1228.31 1136.181230.822 1233.891238.111
  1300.1 1242.16  1316.4 1244.47 1429.321249.861  1590.7 1257.19  1729.6 1257.59
#Mann= 9 ,-1 , 0
       0      .1       0  565.31     .05       0  644.58      .1       0
   691.8    .045       0   789.5      .1       0  940.17     .05       0
 1136.18      .1       0 1233.89     .05       0 1429.32     .06       0
#XS Ineff= 2 , 0
          530.86 1235.42 1097.26         1235.06
Permanent Ineff=
       F       F
Bank Sta=691.8,789.5
XS Rating Curve= 0 ,0
Exp/Cntr(USF)=0,0
Exp/Cntr=0.5,0.3

Type RM Length L Ch R = 1 ,828     ,139.9,135.8,120.3
XS GIS Cut Line= 4
2507934.34854759660951.0817032242507750.73947592660290.089045196
2507484.50632199659679.588881878 2507365.1604254659151.712800813
#Sta/Elev= 30
       0 1264.71    41.7 1262.21    83.2 1247.23   124.7 1236.73  230.95 1224.82
  289.861222.402   348.9  1221.6     367 1224.22  427.36 1222.08   490.1 1221.44
   539.9 1215.31  722.961213.722   759.3 1213.83   786.1 1207.21   811.7 1203.89
   925.2 1203.82   964.4 1204.74   977.1  1207.7   986.2 1210.19 1025.531212.764
  1259.7 1216.71  1291.7 1222.51 1311.471228.466  1328.11230.478  1426.6 1236.39
  1500.4  1241.8  1512.7 1244.07 1622.131248.172  1795.6 1257.06  1893.2 1258.71
#Mann= 12 ,-1 , 0
       0      .1       0  230.95     .06       0  289.86      .1       0
  427.36     .05       0  722.96     .06       0   786.1    .045       0
   977.1      .1       0 1025.53     .06       0 1311.47     .05       0
  1328.1      .1       0  1426.6     .05       0 1622.13     .06       0
#XS Ineff= 2 , 0
          733.84 1219.68 1038.34         1219.68
Permanent Ineff=
       F       F
Bank Sta=786.1,977.1
XS Rating Curve= 0 ,0
Exp/Cntr(USF)=0,0
Exp/Cntr=0.5,0.3

Type RM Length L Ch R = 1 ,693     ,340,362.1,389.6
XS GIS Cut Line= 4
2508140.90875323660987.8035175592507865.49514572660257.957457653
2507677.29584725659872.3784071362507461.55518803659197.615068732
#Sta/Elev= 30
       0 1263.52    86.5 1238.56  157.361227.533  204.161225.978   287.4 1219.71
   300.2 1216.13   381.5 1216.03  403.481222.336   484.1  1213.1  656.951212.076
   710.1 1214.91     762 1213.38   787.9 1218.17  802.671216.169   819.1 1208.24
   854.7 1203.69  1019.4 1203.86  1032.7 1208.43 1038.881209.888  1077.3 1219.97
 1108.971217.602 1211.011213.853  1370.3 1215.86  1409.6 1229.28 1547.08  1240.4
 1605.921247.089 1803.381279.401  1865.8 1287.19 1902.11 1287.52  1917.6 1287.32
#Mann= 15 ,-1 , 0
       0     .05       0  157.36     .06       0  204.16    .055       0
  403.48     .05       0  656.95     .06       0  802.67    .055       0
   819.1    .045       0  1032.7      .1       0 1038.88    .055       0
 1108.97     .06       0 1211.01     .05       0 1547.08    .055       0
 1605.92     .06       0 1803.38      .1       0 1902.11      .1       0
#XS Ineff= 2 , 0
          709.75 1224.88 1086.53         1225.35
Permanent Ineff=
       F       F
Bank Sta=819.1,1032.7
XS Rating Curve= 0 ,0
Exp/Cntr(USF)=0,0
Exp/Cntr=0.5,0.3

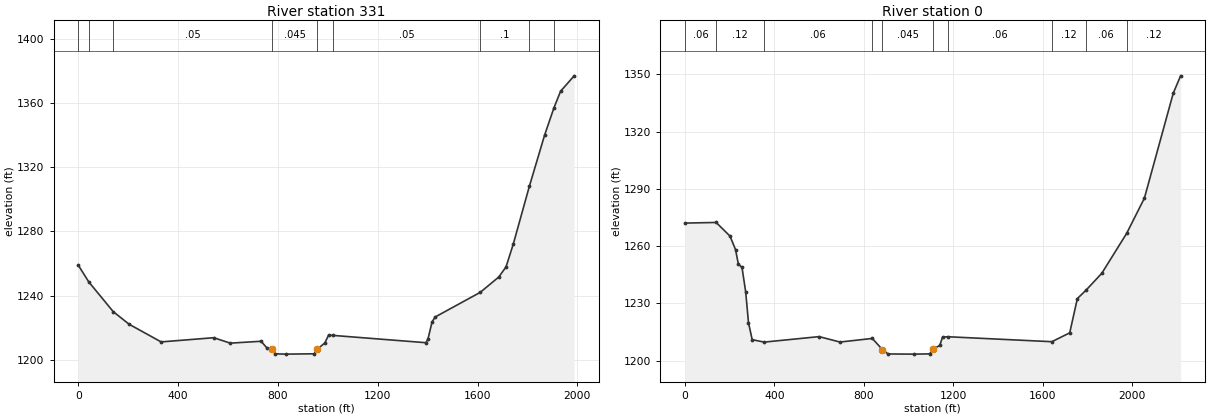
Type RM Length L Ch R = 1 ,331     ,336.6,330.6,328
XS GIS Cut Line= 4
 2508379.6005464660987.803517559 2508214.3523819660358.942447074
2508104.18693889659872.3784071362507865.49514572 659069.08871856
#Sta/Elev= 30
       0 1258.92   41.571248.624  139.621230.095   203.6  1222.2   331.8 1211.21
   542.7 1213.82   608.9 1210.44   732.3 1211.61   756.8 1207.29   777.4 1206.57
   789.7 1203.78   830.5  1203.6   945.6 1203.81   957.9 1206.75   987.7 1210.51
    1003 1215.45 1021.04 1215.25  1392.7 1210.72    1401 1212.82  1417.7  1223.7
  1430.2 1226.74 1610.761242.068  1684.8 1251.59    1714 1257.89  1742.9 1271.99
 1807.63 1308.12  1868.8 1340.03 1906.061356.925  1932.8  1367.3  1987.1 1376.88
#Mann= 9 ,-1 , 0
       0     .05       0   41.57      .1       0  139.62     .05       0
   777.4    .045       0   957.9      .1       0 1021.04     .05       0
 1610.76      .1       0 1807.63     .12       0 1906.06      .1       0
Bank Sta=777.4,957.9
XS Rating Curve= 0 ,0
Exp/Cntr(USF)=0,0
Exp/Cntr=0.3,0.1

Type RM Length L Ch R = 1 ,0       ,0,0,0
XS GIS Cut Line= 3
2508732.58873631661129.1068770572508442.95456915659919.515444313
2508145.28067568658994.537305689
#Sta/Elev= 30
       0 1272.09   140.1 1272.42     202 1265.27   226.8 1258.16   239.2 1250.66
   255.7 1248.83   272.2 1235.93   284.6 1219.94   301.1 1211.02   354.8 1209.74
   600.3 1212.61   693.4 1209.77   837.9 1211.66882.7998 1205.84   908.1 1203.53
  1023.8 1203.44    1094 1203.571108.6991205.873  1139.4 1208.05  1151.8 1212.39
  1175.4 1212.55  1640.3 1209.95    1720 1214.59  1754.2 1232.57  1791.7 1236.78
  1863.6 1245.82  1974.6 1266.73  2053.7 1285.14  2182.7 1340.16  2215.6 1349.24
#Mann= 10 ,-1 , 0
       0     .06       0   140.1     .12       0   354.8     .06       0
   837.9     .12       0882.7998    .045       01108.699     .12       0
  1175.4     .06       0  1640.3     .12       0  1791.7     .06       0
  1974.6     .12       0
Bank Sta=882.7998,1108.699
XS Rating Curve= 0 ,0
Exp/Cntr(USF)=0,0
Exp/Cntr=0.3,0.1
LCMann Table=0

Chan Stop Cuts=-1
Use User Specified Reach Order=0
Composite Channel Slope=5